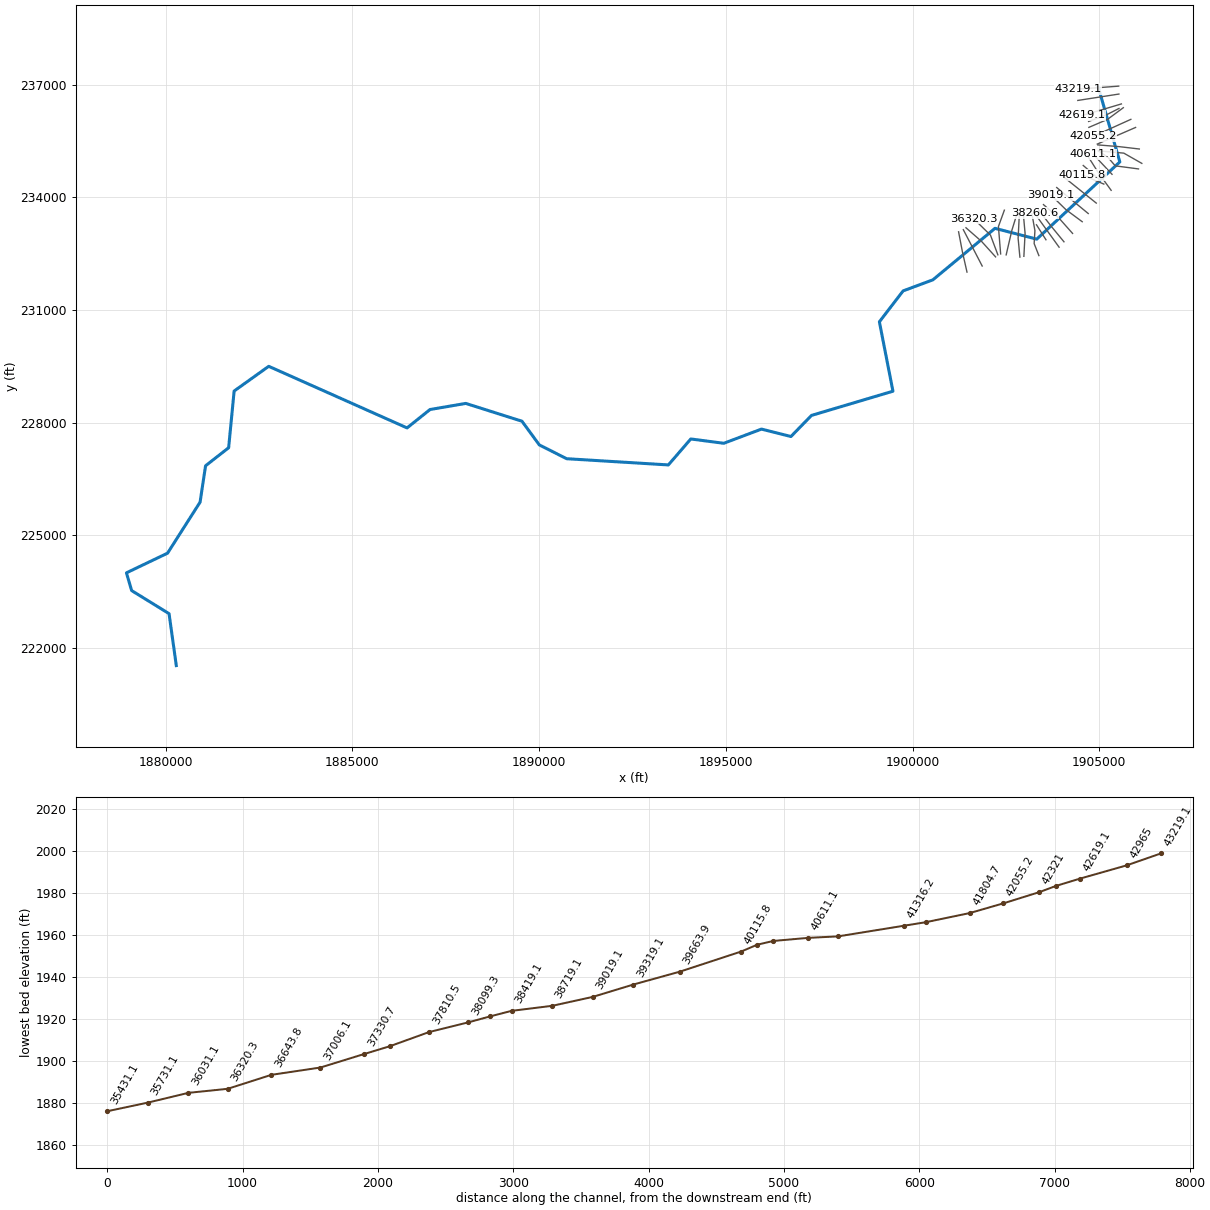
--- StnclCrk.prj (project) ---

Proj Title=StnclCrk
Current Plan=p01
Default Exp/Contr=0,0
English Units
Geom File=g01
Flow File=f01
Plan File=p01
BEGIN DESCRIPTION:
END DESCRIPTION:
DSS Export Rating Curves= 0
DSS Export Rating Curve Sorted= 0
DSS Export Volume Flow Curves= 0
DXF OffsetX= 0
DXF OffsetY= 0
DXF ScaleX= 0
DXF ScaleY= 0

--- StnclCrk.p01 (plan) ---

Plan Title=Floodplain
Program Version=4.00
Geom File=g01
Flow File=f01
K Sum by GR=0
Std Step Tol=0.01
Critical Tol=0.01
Num of Std Step Trials=20
Max Error Tol=0.3
Flow Tol Ratio=0.001
Split Flow NTrial=30
Split Flow Tol=0.02
Split Flow Ratio=0.02
Log Output Level=0
Friction Slope Method=1
Unsteady Friction Slope Method=2
Unsteady Bridges Friction Slope Method=1
Global Log Level=0
CheckData=False
Run HTab=0
Run UNet=0
Run PostProcess=0
UNET Theta=0
UNET Theta Warmup=0
UNET ZTol=0
UNET ZSATol=0
UNET MxIter=0
UNET MaxInSteps=0
UNET DtIC=0
UNET DtMin=0
UNET MaxCRTS=0
UNET WFStab=0
UNET SFStab=0
UNET WFX=0
UNET SFX=0
UNET DSS MLevel=0
UNET DZMax Abort=0
UNET Convert EG Bridges=0
UNET Use Existing IB Tables=0
UNET Froude Limit=0
UNET Froude Power=0
Write IC File=0
Echo Input=False
Echo Output=False
Write Detailed=0

--- StnclCrk.f01 (steady flow) ---

Flow Title=NFF Regression Equation
Program Version=4.00
Number of Profiles=1
Profile Names=P100yr
River Rch & RM=StnclCrk,Main      ,43219.1
861.5325
River Rch & RM=StnclCrk,Main      ,41804.7
897.6510
River Rch & RM=StnclCrk,Main      ,41481.5
1016.146
River Rch & RM=StnclCrk,Main      ,41316.2
1018.951
River Rch & RM=StnclCrk,Main      ,40611.1
1273.303
River Rch & RM=StnclCrk,Main      ,39019.1
1303.333
River Rch & RM=StnclCrk,Main      ,37519.1
1444.058
River Rch & RM=StnclCrk,Main      ,36643.8
1544.226
River Rch & RM=StnclCrk,Main      ,32772
1692.160
River Rch & RM=StnclCrk,Main      ,29952.3
1787.382
River Rch & RM=StnclCrk,Main      ,29457.2
2369.650
River Rch & RM=StnclCrk,Main      ,25794.5
2443.640
River Rch & RM=StnclCrk,Main      ,16550.5
2701.575
River Rch & RM=StnclCrk,Main      ,16226.2
3041.287
River Rch & RM=StnclCrk,Main      ,11002.9
3121.711
River Rch & RM=StnclCrk,Main      ,10692
3629.115
River Rch & RM=StnclCrk,Main      ,248.3
3881.209
Boundary for River Rch & Prof#=StnclCrk,Main      ,1
Up Type=0
Dn Type=3
Dn Slope=0.001151

--- StnclCrk.g01 (geometry) ---

Geom Title=USGS 3m DEM
Program Version=4.10

River Reach=StnclCrk        ,Main
Reach XY= 30
     1904974.588      236935.924     1905550.108      234947.643
     1903325.302      232890.276     1902207.714      233178.175
     1900543.937      231805.947     1899747.126      231511.405
     1899111.453      230687.776     1899474.809      228838.129
       1897294.3      228193.431     1896743.298      227630.743
     1895955.255      227828.759      1894944.74      227450.696
     1894061.322      227565.706     1893460.817      226874.067
     1890738.305      227039.404     1890005.142      227406.938
     1889540.152      228038.696     1888035.713      228512.883
     1887078.326      228350.099     1886463.499       227860.36
     1882759.087      229501.727     1881832.943       228842.67
     1881685.693      227331.709     1881067.833      226851.247
     1880921.032      225881.992     1880049.564      224522.156
     1878948.879      223998.574     1879088.233      223525.739
     1880090.164      222911.141     1880284.007      221527.444

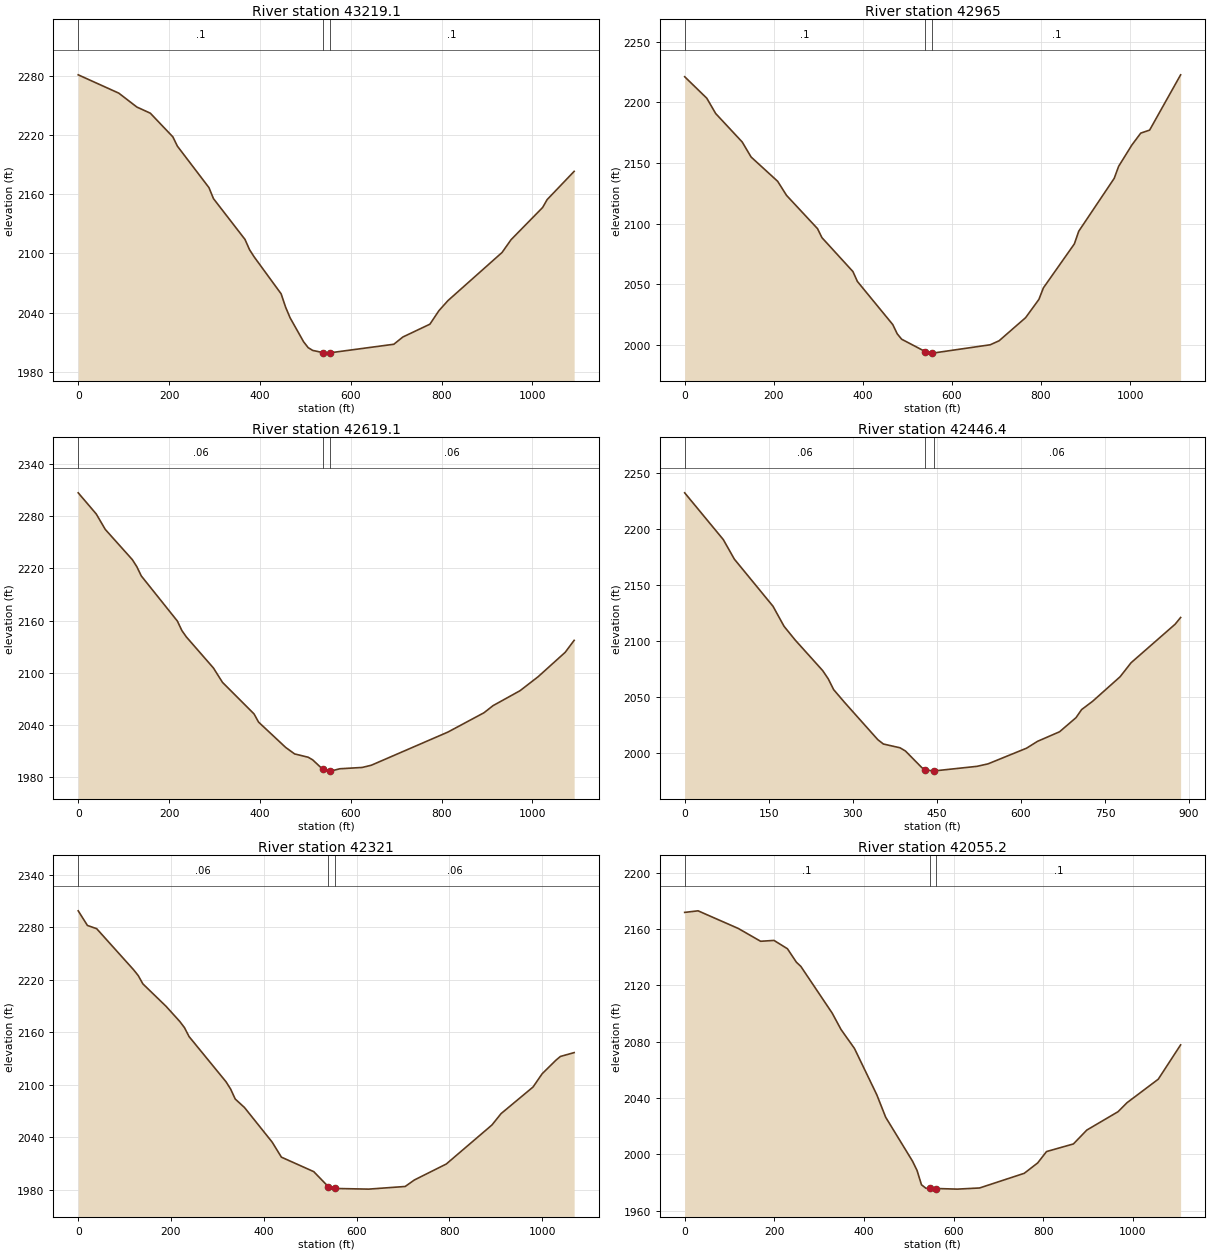
Type RM Length L Ch R = 1 ,43219.1 ,252.2,254,256
XS GIS Cut Line= 3
     1905519.707      236967.291     1904975.231      236925.944
     1904430.372       236890.79
#Sta/Elev= 30
       0 2280.76    89.4  2262.2   129.1 2248.16   158.8 2241.91   208.5  2217.9
   218.4 2208.54   287.9 2166.58   297.8 2155.45   367.3 2114.09   377.3 2103.69
   387.2  2096.6   446.8 2059.06   456.7 2045.51   466.6 2034.74   496.4 2010.43
   506.3 2004.58   516.3 2001.77   538.5 1999.59     546 1999.02   553.5  1999.3
     695 2008.01   714.8 2015.33   774.4 2028.33   794.2 2041.96   814.1 2052.17
   933.2 2100.89   953.1 2113.86  1022.6 2146.46  1032.5 2154.43    1092 2183.04
#Mann= 3 , 0 , 0
       0      .1       0   538.5    .045       0   553.5      .1       0
Bank Sta=538.5,553.5
XS Rating Curve= 0 ,0
Exp/Cntr=0.3,0.1

Type RM Length L Ch R = 1 ,42965   ,342.9,345.9,348.9
XS GIS Cut Line= 2
     1905525.851       236756.33     1904425.316      236586.189
#Sta/Elev= 30
       0 2221.22    49.7 2203.48    69.6 2190.89   129.3 2167.35   149.1 2155.04
   208.8 2134.99   228.7  2123.4   298.3 2095.95   308.2 2088.54   377.8 2060.57
   387.8 2052.43   467.3 2016.84   477.3 2009.22   487.2 2004.79   540.4 1994.55
   555.4 1993.35   556.8 1993.32   686.1 2000.21     706  2003.5   765.6 2022.58
   795.4 2037.62   805.4 2047.08     875 2083.38   884.9 2093.86   964.5 2137.44
   974.4 2147.33  1004.2 2164.96  1024.1 2174.73    1044 2177.21  1113.6 2222.79
#Mann= 3 , 0 , 0
       0      .1       0   540.4    .045       0   555.4      .1       0
Bank Sta=540.4,555.4
XS Rating Curve= 0 ,0
Exp/Cntr=0.3,0.1

Type RM Length L Ch R = 1 ,42619.1 ,171.4,172.8,174.3
XS GIS Cut Line= 3
     1905592.593      236493.379      1905069.09      236338.211
     1904544.576      236186.559
#Sta/Elev= 30
       0 2306.68    39.7 2282.41    59.6 2264.64   119.1 2229.97   129.1  2221.8
     139 2211.14   218.4 2159.34   228.3 2148.42   238.3 2141.04   297.8 2105.42
   317.7 2088.92   387.2 2052.67   397.1 2043.32   456.7 2014.25   476.5 2006.74
   506.3 2002.95   516.2 1999.95   538.5  1989.1   553.5 1986.99   555.9 1986.98
   575.8 1989.68   625.4 1991.21   645.3 1993.73     814 2031.83   893.5 2054.05
   913.3 2062.17   972.9 2079.39  1012.6  2095.4  1072.2 2123.42    1092 2137.21
#Mann= 3 , 0 , 0
       0     .06       0   538.5    .045       0   553.5     .06       0
Bank Sta=538.5,553.5
XS Rating Curve= 0 ,0
Exp/Cntr=0.3,0.1

Type RM Length L Ch R = 1 ,42446.4 ,123.1,125.2,126.3
XS GIS Cut Line= 3
     1905527.354      236372.606     1905176.016      236194.409
     1904714.727      236026.323
#Sta/Elev= 30
       0 2231.96    68.9 2190.24    88.6  2172.8   157.6 2130.74   177.3 2112.86
     197 2100.69   246.2 2073.34   256.1 2066.02   265.9 2056.28   285.6 2044.76
   344.7 2011.62   354.6 2007.79   384.1 2004.45   393.9 2001.57   423.4  1986.6
   429.2 1985.05     443  1983.6   444.2 1983.72   521.6 1987.88   541.2 1990.07
     610 2004.07   629.6 2010.19   668.9 2018.72   698.3 2031.33   708.2  2038.5
   727.8  2045.9   776.9 2067.81   796.5 2080.33   875.1  2114.7   884.9 2120.71
#Mann= 3 , 0 , 0
       0     .06       0   429.2    .045       0   444.2     .06       0
Bank Sta=429.2,444.2
XS Rating Curve= 0 ,0
Exp/Cntr=0.3,0.1

Type RM Length L Ch R = 1 ,42321   ,266.6,266.2,266.8
XS GIS Cut Line= 3
     1905644.288       236392.94     1905218.985      236080.667
     1904721.046      235868.347
#Sta/Elev= 30
       0 2298.66    19.9 2281.93    39.8 2278.25   119.5 2231.23   129.4 2224.66
   139.4 2215.16   189.2 2189.63     219 2172.18     229 2165.19   238.9    2155
   318.6  2103.3   328.5 2094.99   338.5 2083.54   358.4 2073.88   418.1  2034.3
     438 2017.13   507.7 2000.59     539 1983.47     554 1981.34     626  1980.6
   704.8 1983.63   724.5 1991.03   793.4 2009.31   891.8  2053.9   911.5 2066.92
   980.4 2097.31    1000 2112.45  1029.6 2127.88  1039.4 2132.24    1069 2136.62
#Mann= 3 , 0 , 0
       0     .06       0     539    .045       0     554     .06       0
Bank Sta=539,554
XS Rating Curve= 0 ,0
Exp/Cntr=0.3,0.1

Type RM Length L Ch R = 1 ,42055.2 ,250.4,250.1,249.8
XS GIS Cut Line= 2
     1905845.628      236082.234     1904836.379      235627.653
#Sta/Elev= 30
       0  2171.9    29.9 2173.02   119.7 2160.48   169.5 2151.38   199.4 2151.99
   229.4 2146.06   249.3 2136.52   259.3 2133.52   329.1 2100.39     349 2088.67
   378.9 2075.24   428.8  2042.3   448.7 2026.28   508.6 1995.07   518.6 1988.54
   528.5 1978.34   538.5 1975.85   546.8 1975.88   561.8 1975.68   608.3 1975.24
   658.2 1976.06   757.9 1986.48   787.8 1993.84   807.7 2001.95   867.6 2007.35
   897.5  2017.2   967.3 2030.27   987.2 2036.64    1057 2053.36  1106.9 2077.76
#Mann= 3 , 0 , 0
       0      .1       0   546.8    .045       0   561.8      .1       0
Bank Sta=546.8,561.8
XS Rating Curve= 0 ,0
Exp/Cntr=0.3,0.1

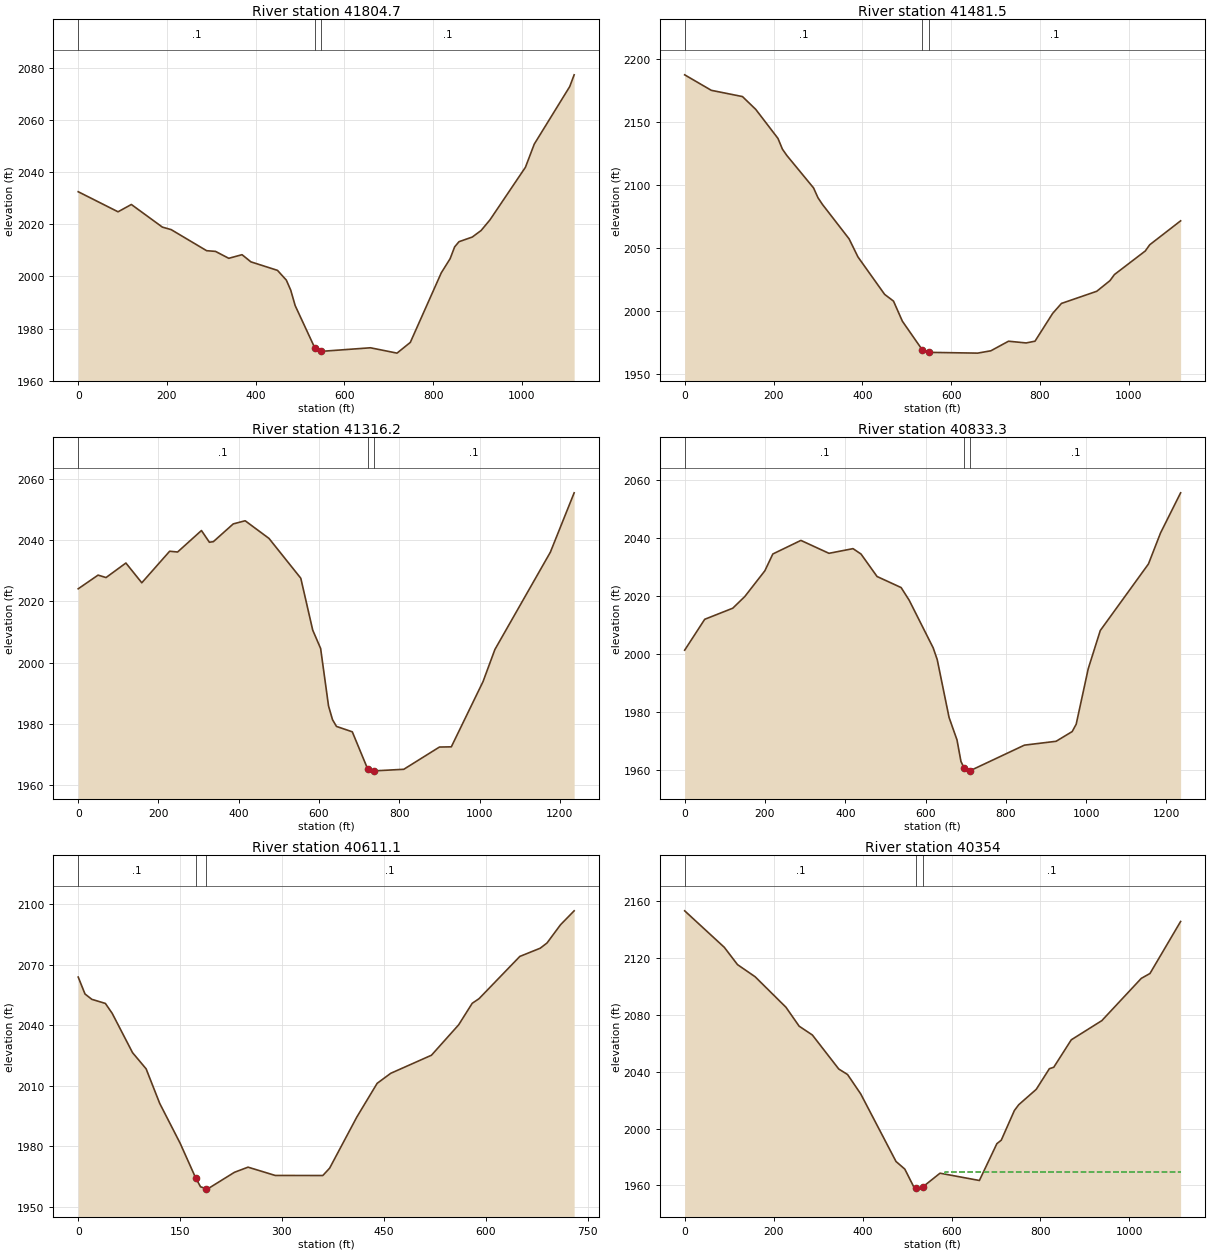
Type RM Length L Ch R = 1 ,41804.7 ,335.3,323.2,311.6
XS GIS Cut Line= 2
     1905972.366      235866.679     1904946.162      235423.074
#Sta/Elev= 30
       0  2032.5    89.8  2024.8   119.8 2027.61   189.7 2018.93   209.6 2017.96
   289.5 2009.88   309.4 2009.62   339.4 2006.96   369.3 2008.35   389.3  2005.6
   449.2 2002.34   469.2 1998.59   479.1 1994.74   489.1 1988.82   533.2 1972.65
   548.2 1971.27   658.8 1972.64   718.7 1970.59   748.6 1974.69   818.5  2001.4
   838.5 2006.84   848.5 2011.32   858.4 2013.33   888.4 2015.12   908.4 2017.65
   928.3 2021.72  1008.2 2041.89  1028.1 2050.77    1108 2072.82    1118 2077.34
#Mann= 3 , 0 , 0
       0      .1       0   533.2    .045       0   548.2      .1       0
Bank Sta=533.2,548.2
XS Rating Curve= 0 ,0
Exp/Cntr=0.3,0.1

Type RM Length L Ch R = 1 ,41481.5 ,164.2,165.2,165.7
XS GIS Cut Line= 3
     1906072.024      235292.018      1905525.47      235355.952
     1904960.884      235401.282
#Sta/Elev= 30
       0 2187.57      60 2175.24   130.1 2170.28   160.1 2160.06   210.1 2136.99
   220.1 2128.44   230.1 2123.42   290.2 2097.63   300.2 2089.79   310.2 2084.52
   370.2 2057.13   390.2 2042.74   450.2 2012.99   470.2 2007.63   490.2 1991.64
   534.9 1968.93   549.9 1966.88   659.6 1966.26   689.4 1968.11   729.2 1975.73
   768.9 1974.36   788.8 1975.75   828.5 1997.81   848.4 2005.78   927.9 2015.45
   957.7 2023.93   967.6 2028.72  1037.2 2047.51  1047.1 2052.42  1116.7 2071.46
#Mann= 3 , 0 , 0
       0      .1       0   534.9    .045       0   549.9      .1       0
Bank Sta=534.9,549.9
XS Rating Curve= 0 ,0
Exp/Cntr=0.3,0.1

Type RM Length L Ch R = 1 ,41316.2 ,501.8,482.8,453.5
XS GIS Cut Line= 3
     1906139.035      234909.119     1905656.382      235182.178
     1904978.186      235243.018
#Sta/Elev= 30
       0 2024.13    49.5  2028.6    69.3  2027.8   118.8 2032.55   158.4 2026.09
   227.8  2036.4   247.6 2036.15     307 2043.17   326.8 2039.34   336.7 2039.53
   386.2 2045.33   415.9 2046.36   475.3 2040.59   554.5 2027.58   584.2 2010.63
   603.9 2004.63   623.6 1985.85   633.5 1981.36   643.4 1979.15   682.8 1977.39
   720.7 1965.38   732.2 1964.54   735.7 1964.61   811.1 1965.14   899.9 1972.41
   929.5 1972.48  1008.5  1993.8  1038.1  2004.3  1176.2 2036.08  1235.5 2055.49
#Mann= 3 , 0 , 0
       0      .1       0   720.7    .045       0   735.7      .1       0
Bank Sta=720.7,735.7
XS Rating Curve= 0 ,0
Exp/Cntr=0.3,0.1

Type RM Length L Ch R = 1 ,40833.3 ,221.4,222.1,222.9
XS GIS Cut Line= 4
     1906050.569      234761.254      1905426.95        234843.1
     1905234.249      235068.005     1904978.186      235243.018
#Sta/Elev= 30
       0 2001.23    49.9 2011.87   119.8  2015.7   149.8 2019.73   199.7  2028.6
   219.6  2034.4   289.5 2039.08   359.4 2034.63   419.3 2036.24   439.3 2034.37
   479.2 2026.63   539.1 2022.82   559.1 2018.48     619 2002.02     629    1998
   658.6    1978   678.3 1970.28   688.2 1962.83   696.5 1960.45   707.9 1959.51
   711.5 1959.69   846.2 1968.47   925.1  1969.8   965.2 1973.15   975.2 1975.69
  1005.2 1994.83  1035.2    2008  1155.2 2030.96  1185.3 2041.66  1235.3 2055.49
#Mann= 3 , 0 , 0
       0      .1       0   696.5    .045       0   711.5      .1       0
Bank Sta=696.5,711.5
XS Rating Curve= 0 ,0
Exp/Cntr=0.3,0.1

Type RM Length L Ch R = 1 ,40611.1 ,259.6,257.1,254.7
XS GIS Cut Line= 2
     1905341.574      234618.444      1904839.69      235148.967
#Sta/Elev= 30
       0 2063.93      10 2055.54      20  2052.9      40 2050.86      50 2045.97
      80 2026.46     100 2018.43     120  2001.3   150.1 1981.54   172.9  1964.4
   180.1 1959.96   187.9 1959.05   190.1 1958.79   230.1 1967.14   250.1 1969.68
   290.1 1965.57   360.2 1965.54   370.2 1969.17   410.2 1994.49   440.2 2011.24
   460.2 2016.21   520.2 2025.18   560.2 2040.24   580.2 2050.93   590.2  2053.2
   650.3 2074.16   680.3 2078.23   690.3 2080.81   710.3 2089.89   730.3 2096.77
#Mann= 3 , 0 , 0
       0      .1       0   172.9    .045       0   187.9      .1       0
#XS Ineff= 2 , 0
                          251.36         1969.45
Permanent Ineff=
       F       F
Bank Sta=172.9,187.9
XS Rating Curve= 0 ,0
Exp/Cntr=0.3,0.1

Type RM Length L Ch R = 1 ,40354   ,114.6,119.4,124.2
XS GIS Cut Line= 3
     1905317.987      234190.696     1904978.953      234654.083
     1904688.503      235110.537
#Sta/Elev= 30
       0 2153.35    89.1 2127.65   118.8 2115.46   158.4 2106.92   227.7 2085.45
   257.4  2072.1   287.1  2065.9   346.5 2041.92   366.3 2038.04     396 2024.31
   475.2  1976.8     495 1971.43   514.8 1959.14   519.8 1958.22   524.7 1957.32
   534.8 1958.71   574.2 1968.54   662.7 1963.41     702 1989.33   711.9 1991.79
   741.4 2012.69   751.2 2016.78   790.6 2027.63   820.1 2042.16   829.9 2043.15
   869.3 2062.48   938.1 2076.02  1026.7 2105.76  1046.3 2109.22  1115.2 2145.85
#Mann= 3 , 0 , 0
       0      .1       0   519.8    .045       0   534.8      .1       0
#XS Ineff= 2 , 0
                          584.64         1969.17
Permanent Ineff=
       F       F
Bank Sta=519.8,534.8
XS Rating Curve= 0 ,0
Exp/Cntr=0.3,0.1

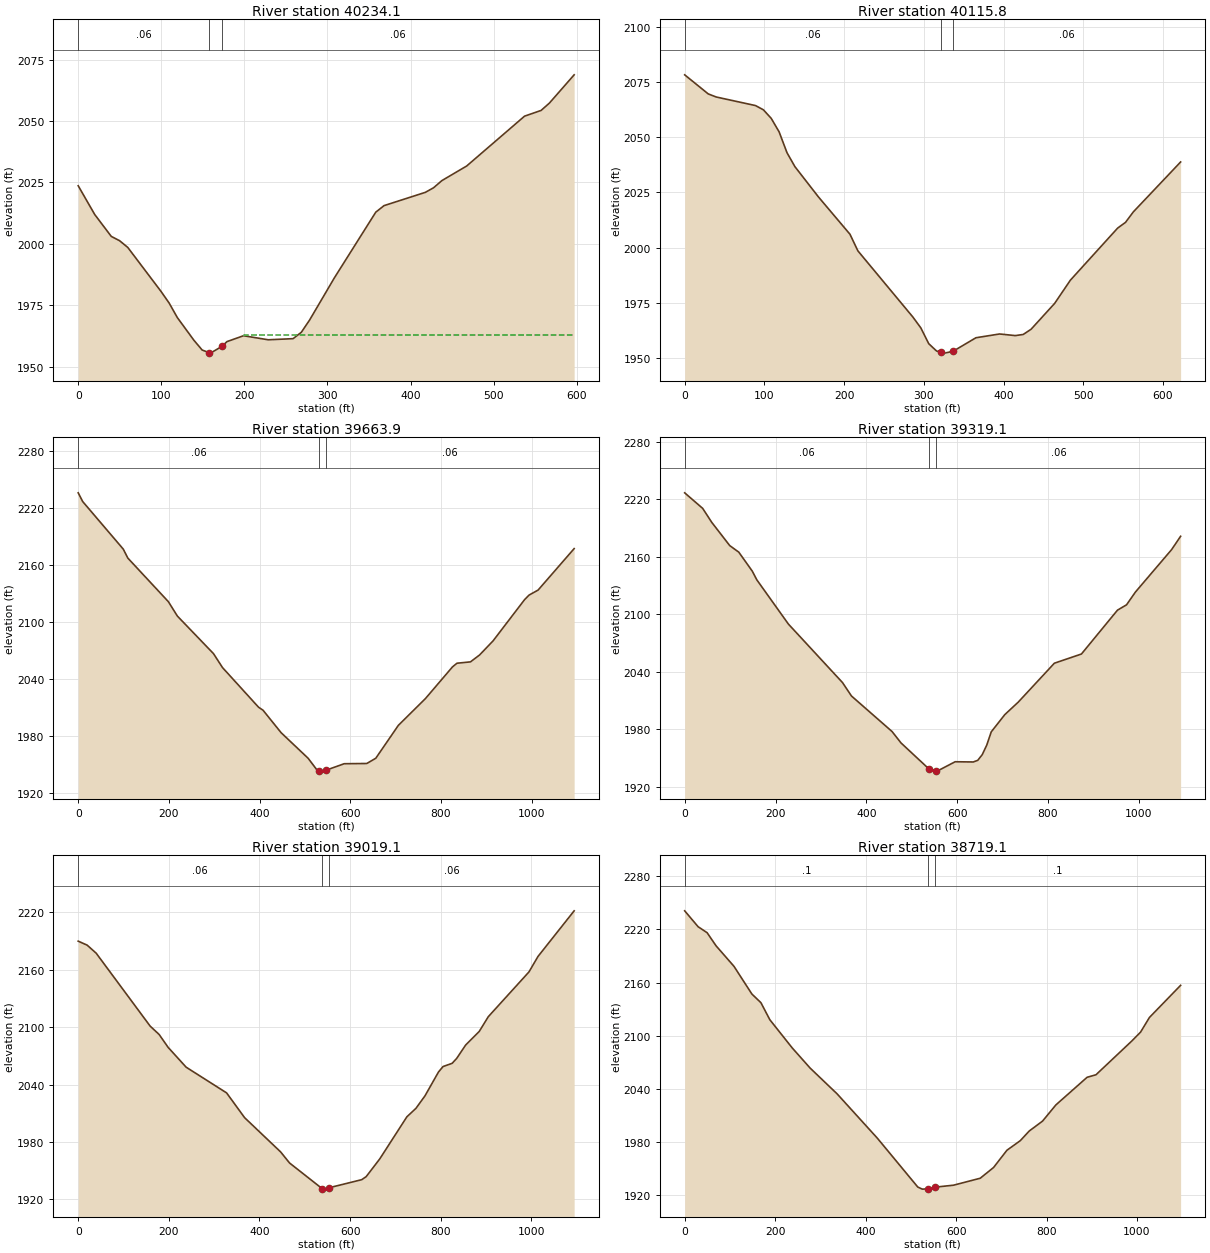
Type RM Length L Ch R = 1 ,40234.1 ,111.4,118.3,125.2
XS GIS Cut Line= 2
     1905022.094      234462.948     1904570.392      234853.308
#Sta/Elev= 30
       0 2023.63    19.9 2011.93    39.8 2003.03    49.8 2001.28    59.7 1998.53
    99.5 1980.73   109.4 1975.94   119.4 1969.96   139.3 1960.76   149.2 1956.79
     158 1955.68   159.2 1955.53     173 1958.27   179.1 1960.22     199 1962.61
   228.8 1960.96   258.7 1961.42   268.6 1964.02   278.6 1969.03   308.4 1986.18
   358.2 2012.89   368.2 2015.56   417.9 2020.96   427.8 2022.83   437.8 2025.74
   467.6 2031.67   537.3 2051.96   557.2 2054.29   567.2 2057.28     597 2068.78
#Mann= 3 , 0 , 0
       0     .06       0     158    .045       0     173     .06       0
#XS Ineff= 2 , 0
                          199.22         1962.76
Permanent Ineff=
       F       F
Bank Sta=158,173
XS Rating Curve= 0 ,0
Exp/Cntr=0.3,0.1

Type RM Length L Ch R = 1 ,40115.8 ,457.8,451.9,445.9
XS GIS Cut Line= 2
     1905121.672      234357.468     1904548.747      234600.119
#Sta/Elev= 30
       0 2078.16    29.6 2069.52    39.5 2068.14    88.9 2064.25    98.8 2062.33
   108.6 2058.46   118.5 2052.35   128.4 2042.91   138.3 2036.63   167.9  2022.9
   207.4 2006.04   217.3 1998.54   286.4 1968.56   296.3 1963.68   306.2 1956.55
     316 1953.24   321.5 1952.71   325.9 1952.28   336.5 1953.07   365.4 1959.23
     395 1960.94   414.8 1960.21   424.7 1960.72   434.6 1963.08   464.2 1974.79
   483.9 1985.28   543.2 2008.83   553.1 2011.44   562.9 2016.17   622.2 2038.74
#Mann= 3 , 0 , 0
       0     .06       0   321.5    .045       0   336.5     .06       0
Bank Sta=321.5,336.5
XS Rating Curve= 0 ,0
Exp/Cntr=0.3,0.1

Type RM Length L Ch R = 1 ,39663.9 ,345.1,344.8,344.5
XS GIS Cut Line= 2
     1904919.404      233850.919      1904064.46      234532.927
#Sta/Elev= 30
       0 2235.57     9.9 2226.39    99.4 2176.31   109.4 2166.92   198.8 2121.04
   218.7 2105.87   298.3 2066.36   318.2 2051.69   397.7 2009.96   407.6  2006.8
   447.4 1983.18     507 1956.26   526.9  1943.7   531.8 1943.22   536.9 1942.72
   546.8 1943.75   586.6 1950.51   636.3 1950.75   656.2 1956.28   705.9 1990.85
   765.6 2019.03   825.2 2052.34   835.2 2056.26     865  2057.7   884.9 2064.88
   914.7 2079.72   984.3 2123.18   994.2 2127.98  1014.1 2133.24  1093.6 2176.87
#Mann= 3 , 0 , 0
       0     .06       0   531.8    .045       0   546.8     .06       0
Bank Sta=531.8,546.8
XS Rating Curve= 0 ,0
Exp/Cntr=0.3,0.1

Type RM Length L Ch R = 1 ,39319.1 ,298.9,300,298.1
XS GIS Cut Line= 3
     1904704.134      233572.871     1904281.941      233919.091
     1903859.747      234265.311
#Sta/Elev= 30
       0 2226.81    39.7 2210.56    59.6 2196.02    99.3 2171.73   119.1 2164.96
   148.9  2145.1   158.8  2136.1   228.3 2089.98   347.4 2028.98   367.3 2014.91
   456.6 1977.87   476.5 1965.89   538.5 1938.55   553.5 1936.67   555.9 1936.56
   595.6 1946.34   635.4 1946.11   645.3 1947.82   655.2 1953.74   665.1 1963.68
     675 1977.48   704.8 1995.45   734.6 2008.58     814 2049.11   873.6  2058.7
     953 2104.45   972.9 2110.01   992.7 2123.45  1072.2 2167.61    1092  2181.5
#Mann= 3 , 0 , 0
       0     .06       0   538.5    .045       0   553.5     .06       0
Bank Sta=538.5,553.5
XS Rating Curve= 0 ,0
Exp/Cntr=0.3,0.1

Type RM Length L Ch R = 1 ,39019.1 ,304.7,300.1,301.4
XS GIS Cut Line= 3
     1904543.081      233354.389     1904104.003      233678.563
     1903710.465      234061.011
#Sta/Elev= 30
       0 2189.97    19.8 2185.79    39.7 2177.37   158.8 2101.12   178.6 2092.39
   198.5 2078.89   238.2 2058.19   327.5 2031.31   367.2 2005.42   446.6 1969.66
   466.4 1958.03   538.3 1931.23   545.8 1930.68   553.3 1932.07   625.6 1940.55
   635.6 1943.78   665.5 1962.29   725.4 2006.33   745.3 2015.13   765.3 2028.23
   795.2 2053.22   805.2 2058.86   825.2 2062.22   835.1 2067.25   855.1 2081.39
     885 2095.54     905 2110.96   994.8 2157.81  1014.7 2173.97  1094.5 2221.69
#Mann= 3 , 0 , 0
       0     .06       0   538.3    .045       0   553.3     .06       0
Bank Sta=538.3,553.3
XS Rating Curve= 0 ,0
Exp/Cntr=0.3,0.1

Type RM Length L Ch R = 1 ,38719.1 ,300.9,299.8,295.3
XS GIS Cut Line= 3
     1904285.135      233042.355      1903922.13      233448.945
     1903505.531      233810.078
#Sta/Elev= 30
       0 2241.03    29.7 2223.06    49.6 2216.29    69.4 2201.47     109 2178.29
   148.6 2146.96   168.5 2137.22   188.3 2117.91   237.8 2086.01   277.5 2063.18
     337 2034.12   426.1 1983.93   515.3  1928.8   525.2 1926.42   537.6 1926.66
   552.6  1928.6   594.3 1930.86   653.4 1938.73   682.9 1950.88   712.4 1970.36
     742 1981.22   761.6 1992.06   791.2 2003.34   820.7 2021.64   889.6 2052.83
   909.3 2055.71   988.1 2093.68  1007.8 2103.88  1027.5 2120.49  1096.4 2156.82
#Mann= 3 , 0 , 0
       0      .1       0   537.6    .045       0   552.6      .1       0
Bank Sta=537.6,552.6
XS Rating Curve= 0 ,0
Exp/Cntr=0.3,0.1

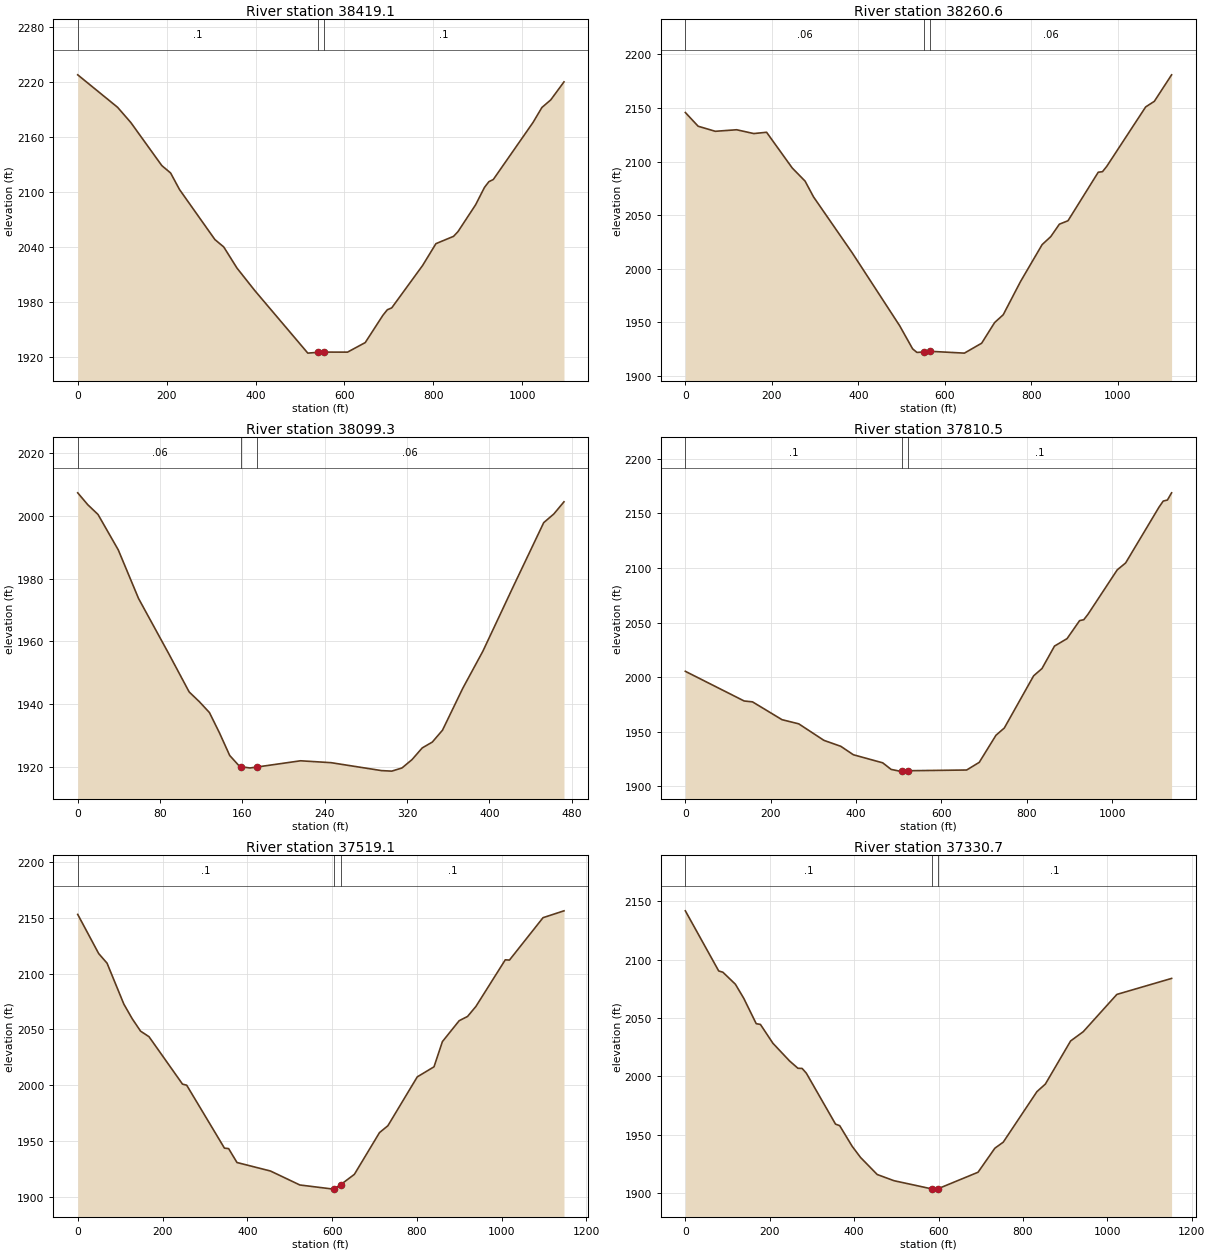
Type RM Length L Ch R = 1 ,38419.1 ,159.9,158.5,157.7
XS GIS Cut Line= 3
     1904054.138      232819.409     1903705.939      233241.835
     1903370.717      233673.371
#Sta/Elev= 30
       0 2227.58    89.6 2192.19   119.4 2175.58   189.1 2128.62     209 2120.48
   228.9 2102.53   308.6  2047.9   328.5 2039.82   358.3 2016.78   398.1 1992.39
   517.6 1924.03   539.9 1924.89   554.9 1925.17     607 1925.11   646.8 1935.54
   686.5 1965.28   696.5 1971.33   706.4  1973.4     776 2019.73   805.8 2043.43
   845.5 2051.43   855.4 2056.52   895.2 2085.91     915 2104.76     925 2111.04
   934.9 2113.41  1024.3 2175.66  1044.2 2191.95  1064.1 2200.23  1093.9  2219.9
#Mann= 3 , 0 , 0
       0      .1       0   539.9    .045       0   554.9      .1       0
Bank Sta=539.9,554.9
XS Rating Curve= 0 ,0
Exp/Cntr=0.3,0.1

Type RM Length L Ch R = 1 ,38260.6 ,162.6,161.3,159.9
XS GIS Cut Line= 3
     1903923.585      232675.765      1903709.58      232972.338
     1903263.187      233585.433
#Sta/Elev= 30
       0 2145.67    29.6 2132.88    69.2 2128.15   118.6 2129.59   158.2 2126.04
   187.8 2127.26   247.1 2093.96   276.8 2081.73   296.5 2066.92   385.7 2014.92
   495.4 1946.97   525.4 1925.39   535.4 1922.05   551.4 1922.47   566.4 1923.08
   645.1 1921.39     685 1930.63     715 1949.88   734.9 1957.17   774.8 1988.08
   824.8 2022.53   844.7 2029.94   864.7 2041.58   884.6 2044.78   954.5 2089.99
   964.4 2090.53   974.4  2095.6  1064.2 2150.89  1084.2 2156.09  1124.1 2180.79
#Mann= 3 , 0 , 0
       0     .06       0   551.4    .045       0   566.4     .06       0
Bank Sta=551.4,566.4
XS Rating Curve= 0 ,0
Exp/Cntr=0.3,0.1

Type RM Length L Ch R = 1 ,38099.3 ,292.7,288.8,280.5
XS GIS Cut Line= 2
     1903572.185      232873.624     1903318.451      233272.349
#Sta/Elev= 30
       0 2007.39     9.8 2003.58    19.7 2000.49    39.4 1989.18    59.1 1973.67
    88.6 1955.96   108.3 1943.83   118.2 1940.72     128 1937.25   137.8 1930.74
   147.7 1923.55   157.5    1920   158.8 1919.94   167.4 1919.56   173.8 1919.84
   216.6 1921.85   246.2 1921.25   295.4 1918.71   305.2 1918.55   315.1 1919.55
   324.9 1922.22   334.8 1925.95   344.6 1927.82   354.5  1931.6   374.2 1944.97
   393.8 1956.85   423.4 1977.54   452.9 1997.87   462.8 2000.66   472.6 2004.53
#Mann= 3 , 0 , 0
       0     .06       0   158.8    .045       0   173.8     .06       0
Bank Sta=158.8,173.8
XS Rating Curve= 0 ,0
Exp/Cntr=0.3,0.1

Type RM Length L Ch R = 1 ,37810.5 ,303.5,291.4,286.4
XS GIS Cut Line= 4
     1903382.676       232451.65     1903255.754       232772.05
     1903276.517      233115.569     1903197.512      233559.405
#Sta/Elev= 30
       0 2005.33   137.8 1978.17   157.5 1977.35   226.5 1961.06   265.8 1957.24
   324.9  1942.1   364.3 1936.68   393.8 1928.94   462.6 1921.54   482.3 1915.52
     502 1913.95   507.4 1913.97   522.4 1914.31   659.3 1914.97   688.8 1921.98
     728 1946.79   747.6 1953.45   816.2 2001.17   835.8 2007.85   865.2 2028.44
   894.6 2035.24     924 2051.73   933.8 2052.58   943.6 2057.52  1012.2 2098.21
  1031.8 2104.49  1110.2 2155.67    1120 2161.18  1129.8 2162.13  1139.6 2168.73
#Mann= 3 , 0 , 0
       0      .1       0   507.4    .045       0   522.4      .1       0
Bank Sta=507.4,522.4
XS Rating Curve= 0 ,0
Exp/Cntr=0.3,0.1

Type RM Length L Ch R = 1 ,37519.1 ,189.8,188.4,184.1
XS GIS Cut Line= 3
      1902980.99       232432.61      1903013.04      233044.803
     1902964.649      233576.698
#Sta/Elev= 30
       0 2152.85    49.4 2117.87    69.2 2109.22   108.8 2072.64   128.5 2059.58
   148.3 2048.44   168.1 2043.52   247.2 2001.07   257.1  2000.1   346.1 1943.84
     356 1943.39   375.7 1930.97   454.8 1923.36     524 1910.88   603.1 1907.17
   605.5  1907.5   620.5 1911.21   652.6 1920.38   711.9 1957.72   731.7 1963.87
     801 2007.56   840.5 2016.57   860.3  2039.1   899.9 2057.81   919.6 2061.59
   939.4 2070.58  1008.6 2112.24  1018.5 2112.02  1097.7 2149.93  1147.1 2156.06
#Mann= 3 , 0 , 0
       0      .1       0   605.5    .045       0   620.5      .1       0
Bank Sta=605.5,620.5
XS Rating Curve= 0 ,0
Exp/Cntr=0.3,0.1

Type RM Length L Ch R = 1 ,37330.7 ,327,324.6,239.1
XS GIS Cut Line= 3
     1902874.061      232411.452     1902826.602       232913.36
     1902859.722      233560.647
#Sta/Elev= 30
       0 2141.83    79.1 2090.32      89 2089.24   118.6 2078.98   138.4 2066.94
     168 2045.17   177.9 2044.56   207.6 2028.38   247.1 2013.22   266.9 2006.99
   276.8 2006.83   286.7 2002.81   355.9 1959.17   365.8 1957.84   395.4 1940.14
   415.2 1930.61   454.7 1916.01   494.3 1910.72   584.3 1903.67   593.9 1903.49
   599.3 1903.91   693.6 1917.94   733.5 1938.54   753.4 1943.72   833.2    1987
   853.1 1993.44     913 2030.38   942.9  2038.3  1022.6 2070.24  1152.3 2083.94
#Mann= 3 , 0 , 0
       0      .1       0   584.3    .045       0   599.3      .1       0
Bank Sta=584.3,599.3
XS Rating Curve= 0 ,0
Exp/Cntr=0.3,0.1

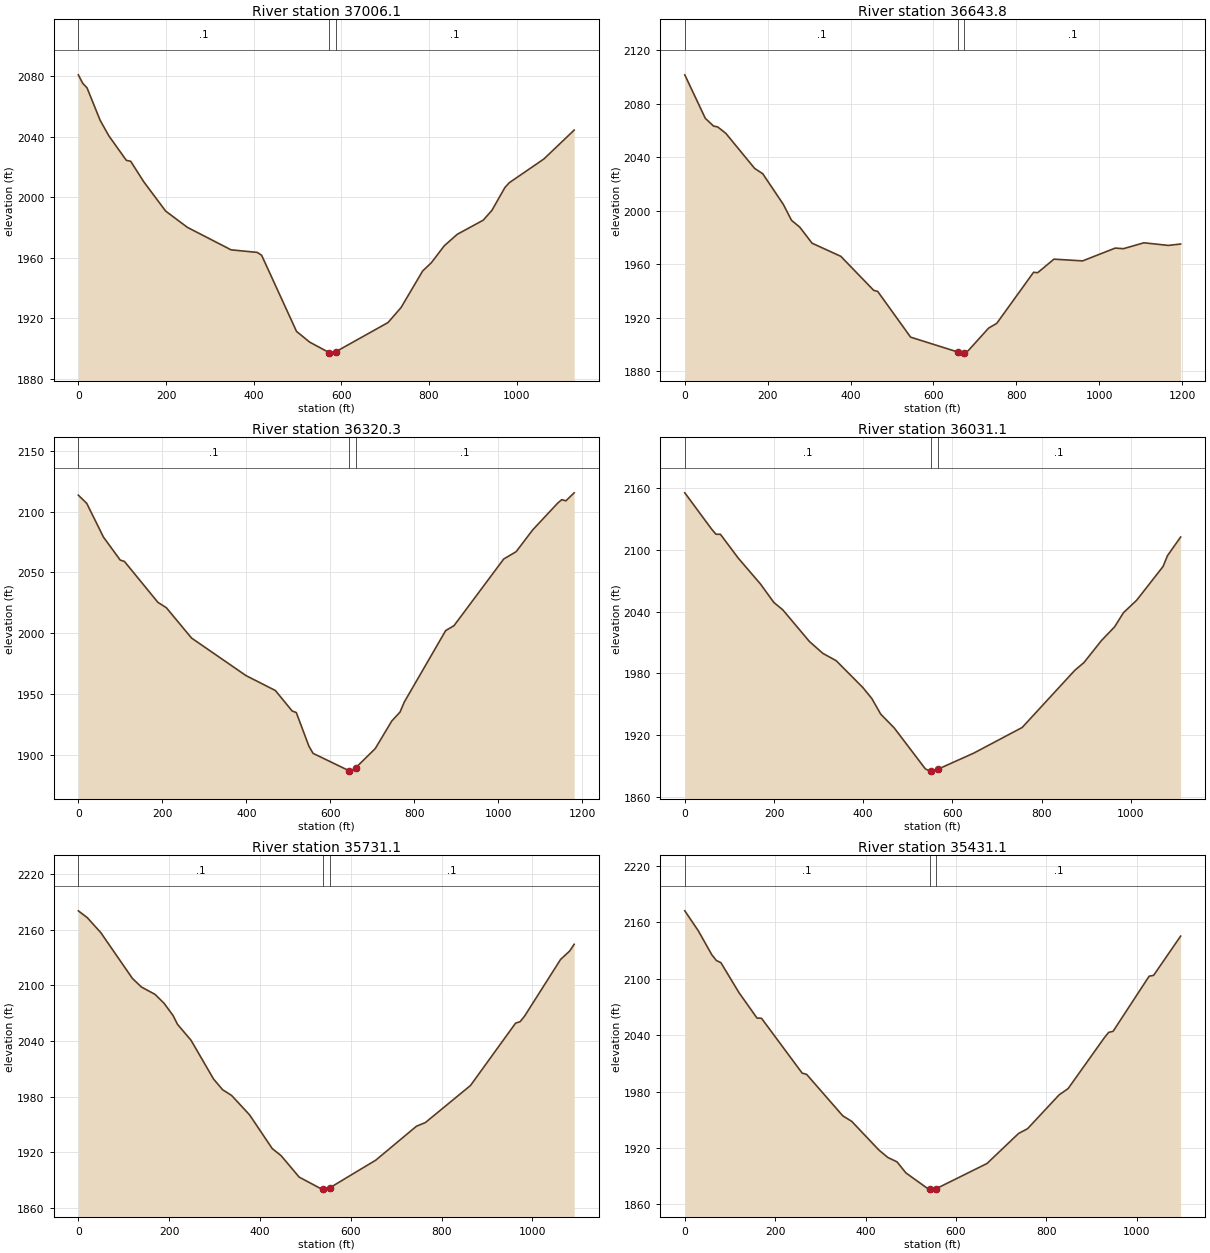
Type RM Length L Ch R = 1 ,37006.1 ,354.3,361.7,369.2
XS GIS Cut Line= 3
     1902506.603      232471.135     1902658.095      233120.624
     1902795.466      233563.908
#Sta/Elev= 30
       0 2080.96      10 2075.38    19.9 2072.33    49.8 2050.88    69.7 2040.61
   109.5 2024.44   119.4 2023.84   149.3 2010.27   199.1 1990.94   248.8 1980.15
   348.4  1965.3   408.1  1963.6   418.1 1961.72   497.7 1911.41   527.6 1904.32
   572.8 1897.28   577.3 1897.03   587.8 1898.04   706.4 1917.24     736 1927.09
   785.4 1951.31   805.2 1956.76   834.8 1968.01   864.4 1975.57   923.6  1984.9
   943.4 1991.39     973 2006.46   982.9 2009.63  1061.9 2025.33    1131 2044.43
#Mann= 3 , 0 , 0
       0      .1       0   572.8    .045       0   587.8      .1       0
Bank Sta=572.8,587.8
XS Rating Curve= 0 ,0
Exp/Cntr=0.3,0.1

Type RM Length L Ch R = 1 ,36643.8 ,307.9,323.8,339.7
XS GIS Cut Line= 3
     1902358.776      232496.079     1902299.174      233226.784
     1902458.131      233661.937
#Sta/Elev= 30
       0 2101.59    49.5 2069.08    69.4 2063.28    79.3 2062.67    99.1 2057.83
   168.4 2031.68   188.2 2027.62   237.8 2004.72   257.6  1992.8   277.4 1987.75
   307.1 1975.73   376.5 1965.92   455.7 1940.53   465.6 1939.64   544.9  1905.5
   659.7 1894.31   673.7 1893.56   674.7 1893.74   683.6  1895.3   733.1 1912.27
   752.8 1915.83   841.6 1954.01   851.4 1953.67   890.8 1963.81   959.8  1962.5
  1038.7 1972.08  1058.4 1971.62  1107.7 1976.04  1166.8 1974.07  1196.4 1975.12
#Mann= 3 , 0 , 0
       0      .1       0   659.7    .045       0   674.7      .1       0
Bank Sta=659.7,674.7
XS Rating Curve= 0 ,0
Exp/Cntr=0.3,0.1

Type RM Length L Ch R = 1 ,36320.3 ,290.9,289.2,290.4
XS GIS Cut Line= 3
     1902284.123      232472.737     1902086.855      232995.929
     1901641.718      233430.204
#Sta/Elev= 30
       0 2113.42      20 2106.72    59.9 2078.98    99.8 2060.12   109.8 2059.04
   189.7 2025.39   209.7 2021.02   269.6 1996.15   399.4 1965.31   469.3 1953.08
   509.2 1936.29   519.2 1934.95   549.2 1907.37   559.2 1901.47   645.2 1887.15
     648 1886.89   660.2 1889.48   707.2 1905.38   746.7  1928.1   766.4 1935.44
   776.3 1943.54     875 2002.26   894.8 2006.29  1013.2 2061.01  1042.8 2067.03
  1082.3 2084.93  1141.6 2106.82  1151.4 2109.75  1161.3 2108.78    1181 2115.34
#Mann= 3 , 0 , 0
       0      .1       0   645.2    .045       0   660.2      .1       0
Bank Sta=645.2,660.2
XS Rating Curve= 0 ,0
Exp/Cntr=0.3,0.1

Type RM Length L Ch R = 1 ,36031.1 ,305.6,300,291.5
XS GIS Cut Line= 3
     1902223.645      232417.152     1901847.197      232830.492
     1901430.401       233193.26
#Sta/Elev= 30
       0 2155.74    59.9 2120.57    69.9 2115.46    79.9 2115.39   119.8 2092.26
   169.7 2067.01   199.7 2049.06   219.6 2041.97   279.5 2011.06   309.5 1999.55
   339.4 1992.44   399.3 1966.25   419.3 1955.61   439.3  1940.4   469.2 1927.18
   539.1  1887.3   549.1 1884.98   551.6 1885.09   566.6 1886.67   647.9 1902.52
   756.4 1927.45   874.8 1983.26   894.6 1990.46     934 2011.96   963.6 2025.36
   983.4 2039.08    1013 2051.22  1072.2 2084.05    1082 2094.49  1111.6 2112.73
#Mann= 3 , 0 , 0
       0      .1       0   551.6    .045       0   566.6      .1       0
Bank Sta=551.6,566.6
XS Rating Curve= 0 ,0
Exp/Cntr=0.3,0.1

Type RM Length L Ch R = 1 ,35731.1 ,305.8,300,293.4
XS GIS Cut Line= 3
     1901864.476      232174.241     1901611.929      232658.324
     1901359.083      233142.251
#Sta/Elev= 30
       0 2180.42    19.8 2173.02    49.6 2156.83   119.1 2107.55     139 2098.24
   168.8  2090.4   188.6 2080.88   208.5 2067.64   218.4 2058.05   248.2 2040.87
   297.8 1999.07   317.7 1987.55   337.5 1981.37   377.2 1960.38   426.9 1924.16
   446.7 1916.37   486.4 1893.28   536.1 1880.33   538.5 1880.35   553.5 1881.66
   655.2 1911.61   744.6 1948.13   764.4 1952.14   863.7 1992.08     963 2059.31
   972.9 2060.89   982.8 2066.88  1062.2 2128.07  1082.1 2137.06    1092 2144.34
#Mann= 3 , 0 , 0
       0      .1       0   538.5    .045       0   553.5      .1       0
Bank Sta=538.5,553.5
XS Rating Curve= 0 ,0
Exp/Cntr=0.3,0.1

Type RM Length L Ch R = 1 ,35431.1 ,291.6,300,312.8
XS GIS Cut Line= 3
     1901457.731      232012.002     1901335.765      232547.775
     1901232.309      233085.933
#Sta/Elev= 30
       0 2172.41      30 2151.12    59.9 2125.59    69.9 2119.56    79.9 2117.25
   119.9 2085.38   159.8 2058.33   169.8 2058.06   259.8 1999.68   269.7 1998.35
   349.7 1954.24   369.6 1948.31   429.6 1917.86   449.6 1909.85   469.6  1905.3
   489.5 1893.46   539.5 1876.22     542 1876.36     557 1876.81     669 1903.52
   738.8 1935.46   758.7 1940.53   828.5 1976.52   848.4 1983.19   928.1 2036.98
   938.1 2043.01     948 2044.17  1027.8 2102.83  1037.7 2103.74  1097.5 2145.48
#Mann= 3 , 0 , 0
       0      .1       0     542    .045       0     557      .1       0
Bank Sta=542,557
XS Rating Curve= 0 ,0
Exp/Cntr=0.3,0.1