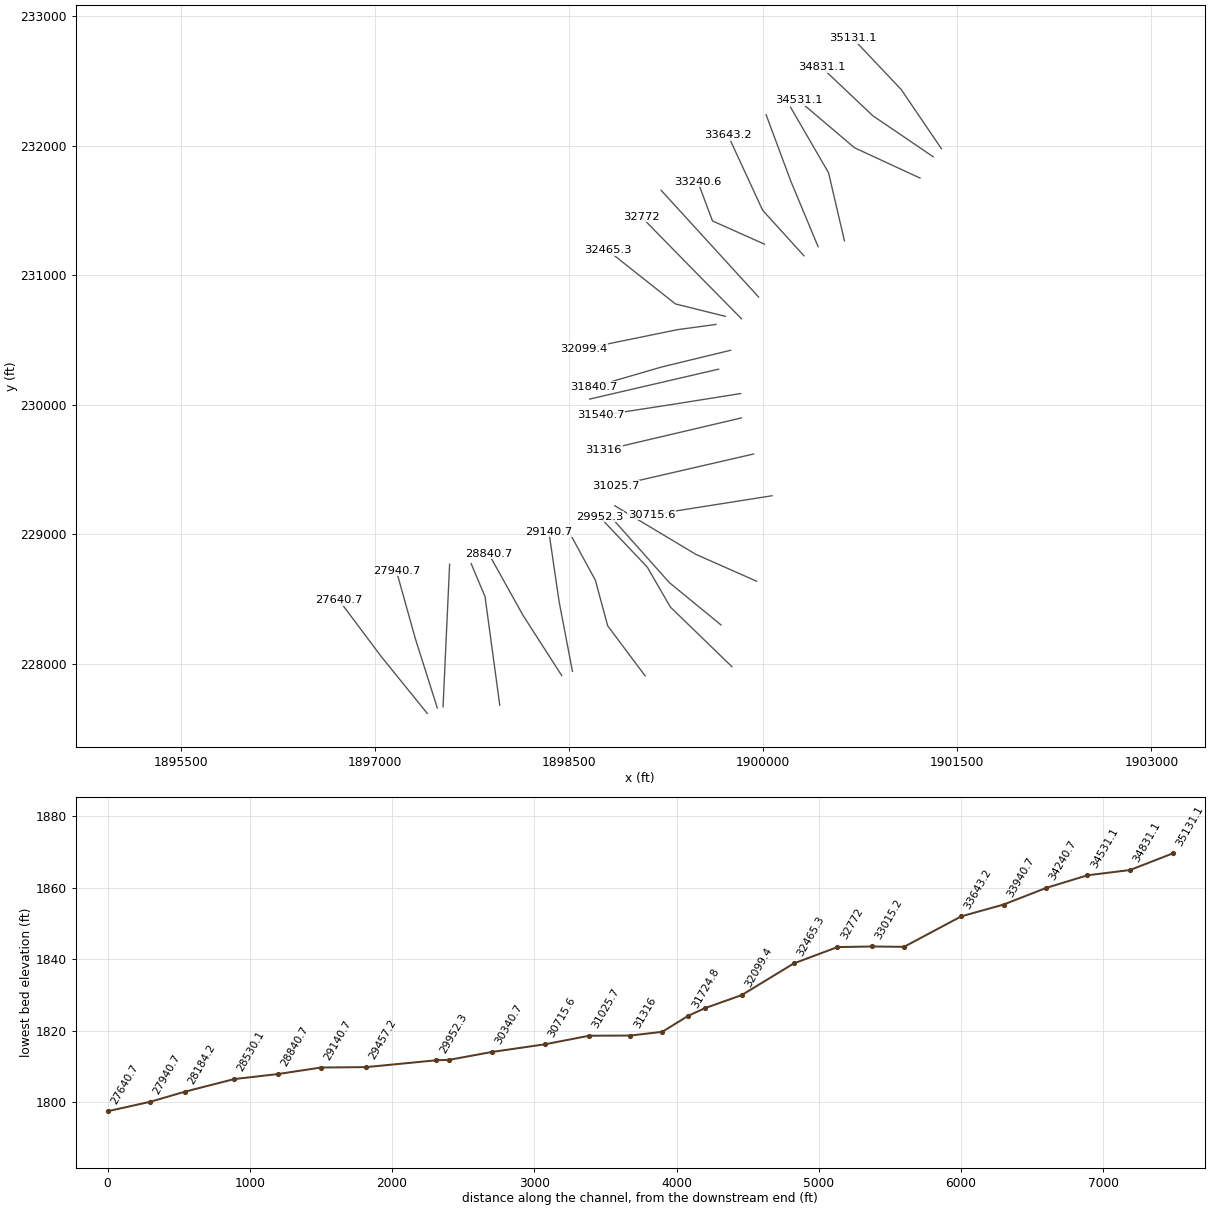
HEC-RAS study StnclCrk.prj: StnclCrk

--- StnclCrk.g01 (geometry) --- (continued)

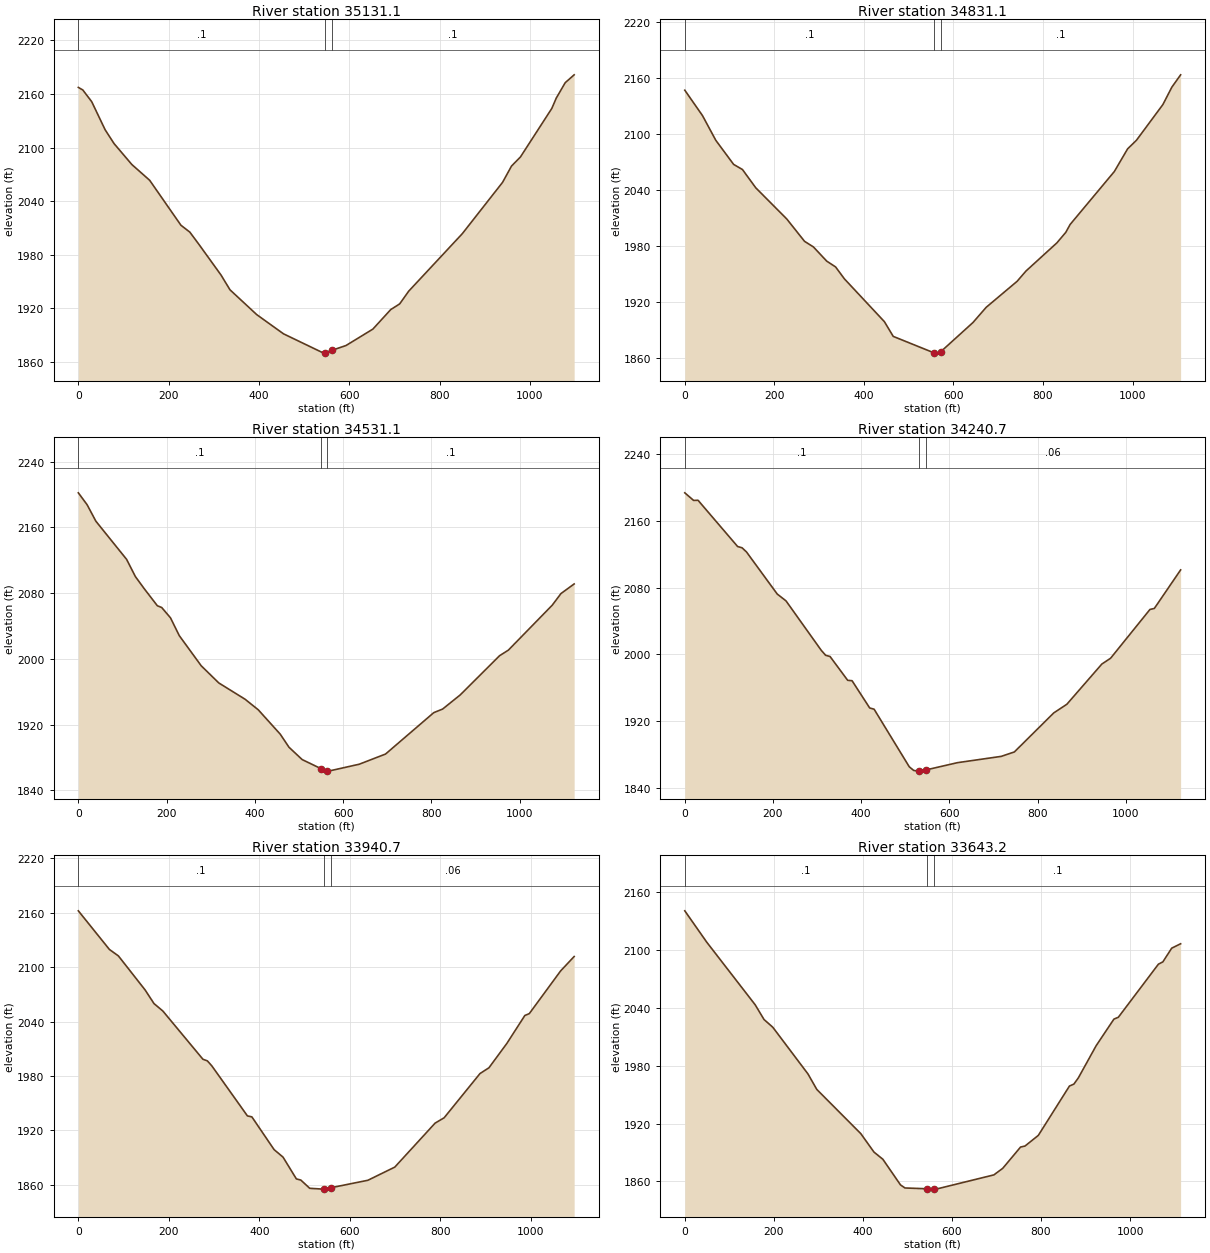
Type RM Length L Ch R = 1 ,35131.1 ,291.4,300,301.3
XS GIS Cut Line= 3
     1901377.649      231977.239     1901066.636      232434.644
     1900692.204      232830.324
#Sta/Elev= 30
       0 2167.37     9.9  2164.5    29.6 2151.38    59.3 2119.95      79 2104.47
   118.5 2080.96     158 2063.27   227.2 2012.91   246.9 2005.19   266.7 1991.71
   316.1 1957.02   335.8 1940.57   395.1 1912.73   454.4 1891.21   543.2 1869.61
   545.6 1869.85   560.6 1872.63   592.7 1878.13   652.2 1896.52   691.8 1918.43
   711.6 1924.79   731.4 1938.94   850.3 2003.49   939.4 2060.99   959.2 2079.23
     979 2089.44  1048.4 2143.78  1058.3  2155.4  1078.1 2172.64  1097.9 2181.46
#Mann= 3 , 0 , 0
       0      .1       0   545.6    .045       0   560.6      .1       0
Bank Sta=545.6,560.6
XS Rating Curve= 0 ,0
Exp/Cntr=0.3,0.1

Type RM Length L Ch R = 1 ,34831.1 ,297.2,299.7,299.3
XS GIS Cut Line= 3
     1901313.605      231915.949      1900846.46      232233.026
     1900452.203      232605.994
#Sta/Elev= 30
       0 2146.78    39.6 2119.49    69.3 2093.03     109 2067.27   128.8 2061.74
   158.5 2042.16   227.8 2008.72   267.4  1984.8   287.2  1978.8     317 1963.56
   336.8 1957.33   356.6 1944.48   445.7 1898.72   465.5  1882.9   557.1 1865.14
   564.6 1864.96   572.1 1866.68   643.5 1897.73   673.1 1914.07   742.2 1941.96
   761.9 1952.94     831 1983.15   850.8 1994.38   860.6  2002.9   959.3 2059.63
   988.9  2083.9  1008.6 2093.09  1067.8 2131.46  1087.6 2149.95  1107.3 2163.26
#Mann= 3 , 0 , 0
       0      .1       0   557.1    .045       0   572.1      .1       0
Bank Sta=557.1,572.1
XS Rating Curve= 0 ,0
Exp/Cntr=0.3,0.1

Type RM Length L Ch R = 1 ,34531.1 ,310,290.3,284.1
XS GIS Cut Line= 3
     1901211.458      231751.761     1900705.965      231985.236
      1900273.82      232351.552
#Sta/Elev= 30
       0 2202.18    19.9  2187.7    39.8 2167.61   109.4 2121.18   129.3 2100.22
   149.1 2085.65     179 2064.75   188.9  2062.6   208.8 2050.04   228.7 2028.37
   278.4  1991.7   318.2 1970.81   377.8 1950.96   407.7 1938.09   457.4 1908.48
   477.3 1892.52   507.1 1877.54   549.3 1866.61   564.3 1863.86   566.7 1863.48
   636.3 1871.87     696 1884.27   805.3 1934.67   825.2 1938.98   864.9 1956.09
   954.4 2003.98   974.2  2010.7  1073.6 2065.42  1093.5 2079.63  1123.3 2091.28
#Mann= 3 , 0 , 0
       0      .1       0   549.3    .045       0   564.3      .1       0
Bank Sta=549.3,564.3
XS Rating Curve= 0 ,0
Exp/Cntr=0.3,0.1

Type RM Length L Ch R = 1 ,34240.7 ,296.3,300,296
XS GIS Cut Line= 3
     1900627.569      231267.666     1900504.904      231792.591
     1900211.132      232298.814
#Sta/Elev= 30
       0 2193.55      20 2184.44      30 2184.64   119.8 2129.19   129.8 2127.68
   139.8 2122.75   209.6 2072.25   229.6 2063.97   309.5 2004.72   319.4  1998.8
   329.4 1997.37   369.4 1968.79   379.3 1968.34   419.3 1935.67   429.3 1934.19
   509.1 1865.11   519.1 1860.78   529.1 1859.95   531.6 1860.08   546.6 1861.35
   618.4 1870.09   717.6 1877.63   747.4 1882.95   836.7 1929.73   866.4  1940.1
   945.8 1988.33   965.6 1995.27  1054.9 2053.76  1064.8 2054.96  1124.4 2101.15
#Mann= 3 , 0 , 0
       0      .1       0   531.6    .045       0   546.6     .06       0
Bank Sta=531.6,546.6
XS Rating Curve= 0 ,0
Exp/Cntr=0.3,0.1

Type RM Length L Ch R = 1 ,33940.7 ,296.6,297.5,299.3
XS GIS Cut Line= 3
     1900424.278      231221.537     1900212.389      231729.854
     1900022.398      232240.733
#Sta/Elev= 30
       0 2161.99    68.8 2119.36    88.5 2112.33   147.5 2074.85   167.2 2059.79
   186.8 2051.57   275.4 1998.39   285.2 1996.62     295 1991.15   373.7 1935.98
   383.5 1934.92   432.7  1898.8   452.4 1890.56   481.9 1866.53   491.7 1865.28
   511.4 1856.19   540.9 1855.28   543.2  1855.4   558.2 1856.81   639.9 1865.03
   699.4 1879.55   788.6 1928.07   808.4 1933.88   887.7 1982.64   907.5 1989.03
   947.1 2015.88   986.8 2046.63   996.7 2048.73    1066 2095.83  1095.8 2111.62
#Mann= 3 , 0 , 0
       0      .1       0   543.2    .045       0   558.2     .06       0
Bank Sta=543.2,558.2
XS Rating Curve= 0 ,0
Exp/Cntr=0.3,0.1

Type RM Length L Ch R = 1 ,33643.2 ,386.5,402,413.1
XS GIS Cut Line= 3
      1900314.56      231151.687     1899995.678      231502.954
     1899727.338      232083.105
#Sta/Elev= 30
       0 2140.58    49.4 2108.01   158.1 2043.13   177.9  2027.9   197.7 2019.83
   276.7 1971.39   296.5 1955.35   395.4 1909.47     425 1890.34   444.8 1882.98
   484.4  1856.4   494.4 1853.18   544.6 1852.33   559.6 1852.01   564.3 1851.98
   694.2 1866.74   714.1 1873.56   754.1 1895.61   764.1 1896.66     794  1907.7
   863.9 1958.87   873.9 1960.91   883.9 1967.35   923.9 2000.72   963.8 2028.28
   973.8 2030.24  1063.7 2085.25  1073.7 2087.63  1093.6 2101.86  1113.6 2106.42
#Mann= 3 , 0 , 0
       0      .1       0   544.6    .045       0   559.6      .1       0
Bank Sta=544.6,559.6
XS Rating Curve= 0 ,0
Exp/Cntr=0.3,0.1

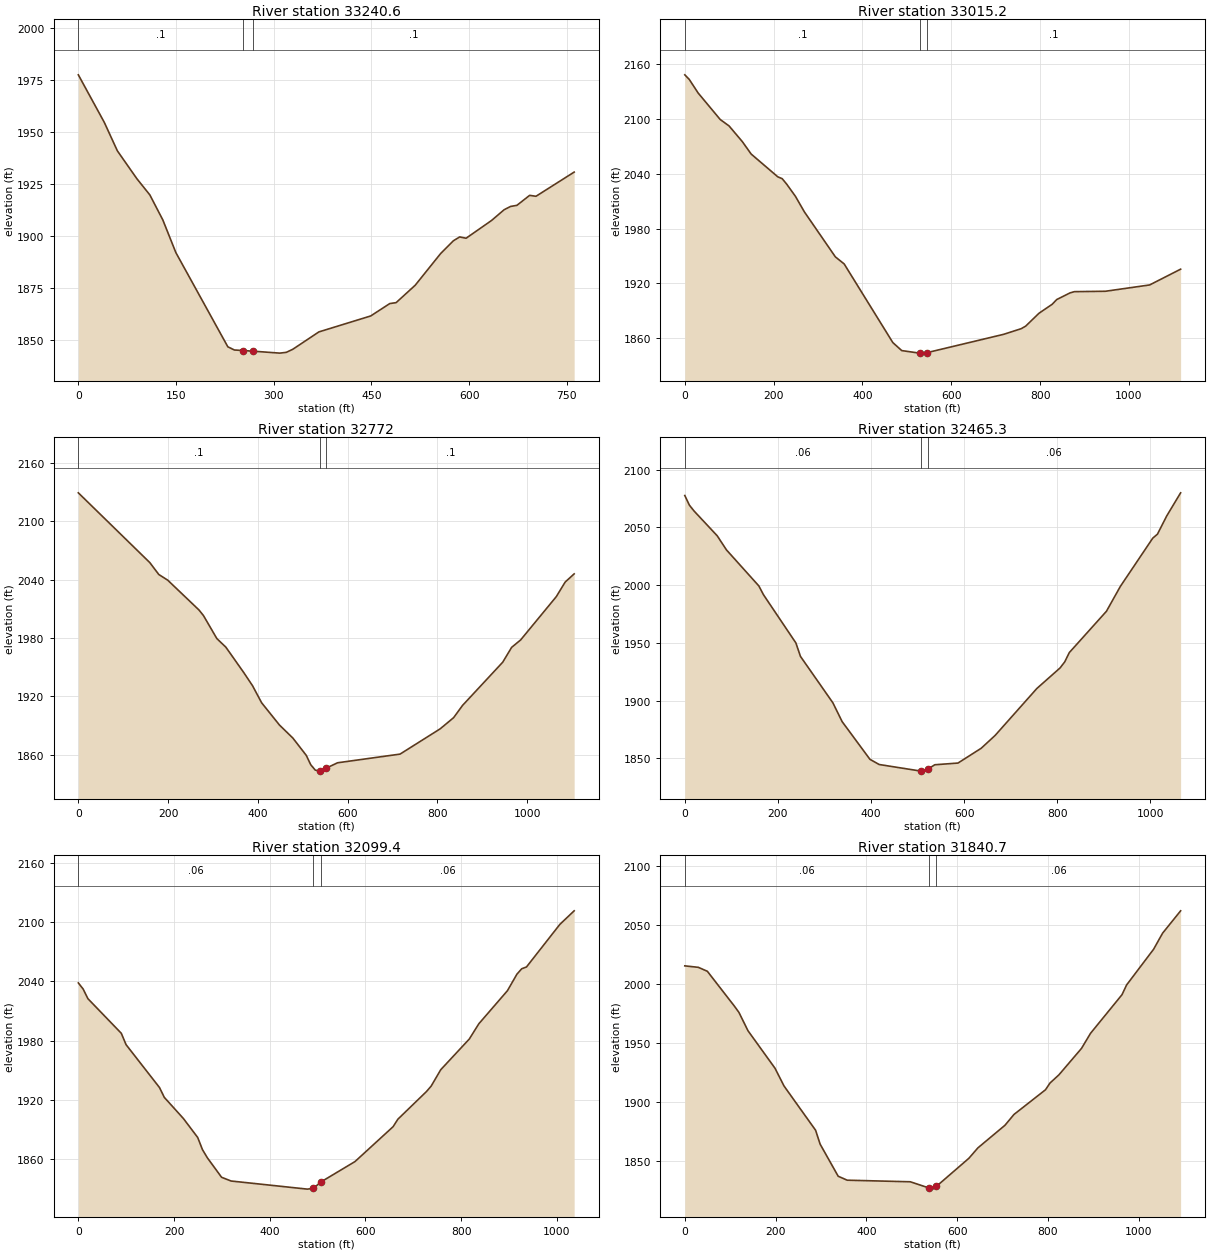
Type RM Length L Ch R = 1 ,33240.6 ,233.7,225.6,222
XS GIS Cut Line= 3
     1900009.159      231241.767     1899608.111      231420.385
     1899495.211      231722.013
#Sta/Elev= 30
       0 1977.31    39.9 1954.42    59.9 1940.76    89.8 1927.37   109.8 1919.54
   129.7 1907.52   149.7 1891.81   229.5 1846.49   239.5 1844.96   253.3 1844.69
   268.3 1844.39   309.3 1843.45   319.3 1843.83   329.3 1845.32   369.2 1853.65
   448.8 1861.33   478.1 1867.29   487.8 1867.73   517.1  1876.1   556.1 1891.33
   575.7 1897.49   585.4 1899.34   595.2 1898.71   634.2 1907.23   653.7 1912.44
   663.5    1914   673.2 1914.53   692.8 1919.34   702.5 1918.89   761.1 1930.52
#Mann= 3 , 0 , 0
       0      .1       0   253.3    .045       0   268.3      .1       0
Bank Sta=253.3,268.3
XS Rating Curve= 0 ,0
Exp/Cntr=0.3,0.1

Type RM Length L Ch R = 1 ,33015.2 ,242.2,242.8,243.3
XS GIS Cut Line= 2
     1899964.671      230832.896     1899211.311      231656.966
#Sta/Elev= 30
       0 2148.51      10 2143.52    29.9 2128.69    79.8 2099.52    99.7  2092.5
   129.6 2075.28   149.5 2061.68   209.4 2036.75   219.3 2034.71   229.3 2028.82
   249.2 2015.33   269.2  1998.4     339 1949.07   358.9 1941.27   468.5 1855.08
   488.5 1846.34   528.4 1843.55     530 1843.55     545 1844.03   717.8 1864.12
   757.6 1870.35   767.6 1873.13   797.5 1887.22   827.4 1897.13   837.4 1902.22
   867.3 1909.52   877.3 1910.91   947.1 1911.34  1046.8 1918.27  1116.5 1935.54
#Mann= 3 , 0 , 0
       0      .1       0     530    .045       0     545      .1       0
Bank Sta=530,545
XS Rating Curve= 0 ,0
Exp/Cntr=0.3,0.1

Type RM Length L Ch R = 1 ,32772   ,303.8,306.7,309.7
XS GIS Cut Line= 3
     1899832.027      230665.649      1899447.45      231055.456
     1899057.562      231453.159
#Sta/Elev= 30
       0 2129.08   159.3 2057.42   179.2 2045.25   199.1 2039.44   268.8 2008.79
   278.8 2003.03   308.6 1979.44   328.6 1970.66   368.4 1944.63   388.3 1930.88
   408.2 1913.63     448 1890.74   477.9 1877.32   507.8 1859.53   517.7 1849.98
   527.7 1844.46   537.6 1843.38   537.8 1843.42   552.8 1846.57   577.4 1851.94
   716.7 1860.86   806.2 1886.84     836 1898.27   855.9 1910.84   945.4 1955.21
   965.3 1970.47   985.2 1978.01  1064.7  2022.5  1084.6 2037.54  1104.5 2045.86
#Mann= 3 , 0 , 0
       0      .1       0   537.8    .045       0   552.8      .1       0
Bank Sta=537.8,552.8
XS Rating Curve= 0 ,0
Exp/Cntr=0.3,0.1

Type RM Length L Ch R = 1 ,32465.3 ,345.9,366,386
XS GIS Cut Line= 3
     1899707.531      230684.008     1899321.649      230780.057
     1898798.063      231193.996
#Sta/Elev= 30
       0 2077.64     9.9 2069.28    19.9 2064.21    69.6 2042.76    89.5 2030.52
   159.1 1999.27     169 1991.67   238.6 1949.91   248.5  1938.2   318.1 1898.02
     338 1881.69   397.7 1849.04   417.6 1844.53   506.5 1838.87   507.2  1838.8
   521.5 1840.44   537.1 1844.32   586.9  1845.8   636.7 1858.61   666.6 1869.72
   756.3 1910.43   806.1  1928.2   816.1 1933.44     826 1941.54   905.7  1977.3
   935.6 1998.85  1005.3 2040.72  1015.3 2044.13  1035.2 2059.91  1065.1 2079.97
#Mann= 3 , 0 , 0
       0     .06       0   506.5    .045       0   521.5     .06       0
Bank Sta=506.5,521.5
XS Rating Curve= 0 ,0
Exp/Cntr=0.3,0.1

Type RM Length L Ch R = 1 ,32099.4 ,257.8,258.7,260.5
XS GIS Cut Line= 3
     1899635.073       230621.66       1899338.5      230581.218
     1898616.707      230433.965
#Sta/Elev= 30
       0 2038.51      10 2032.38      20 2022.58    89.8 1987.54    99.8 1976.03
   169.6 1932.69   179.6 1922.77   219.5 1901.38   249.4  1882.2   259.4 1869.86
   269.4 1861.76   299.3 1841.93   319.2 1838.14   478.5 1829.94   491.3 1830.66
   506.3 1837.02     578 1857.79   657.7 1893.09   667.6 1900.62   727.4 1928.63
   737.3 1934.22   757.2 1950.69     817 1981.81   836.9 1997.23   896.6 2030.65
   916.5 2047.42   926.5 2052.84   936.4 2054.65  1006.1  2097.7    1036 2111.43
#Mann= 3 , 0 , 0
       0     .06       0   491.3    .045       0   506.3     .06       0
Bank Sta=491.3,506.3
XS Rating Curve= 0 ,0
Exp/Cntr=0.3,0.1

Type RM Length L Ch R = 1 ,31840.7 ,116.1,115.9,114.7
XS GIS Cut Line= 3
     1899747.122      230421.824     1899215.803      230293.123
     1898691.648      230140.659
#Sta/Elev= 30
       0  2015.4    29.8 2014.16    49.7 2010.81   109.3 1981.29   119.3 1975.98
   139.2 1960.47   198.8 1928.68   218.7 1913.61   288.2 1876.19   298.2  1864.4
     338  1837.2   357.8 1833.85     497  1832.5   539.2 1827.12   546.7 1826.28
   554.2 1828.54   626.1 1852.44   645.9 1861.23   705.5 1880.36   725.3  1889.5
   794.8 1910.43   804.7 1916.11   824.6 1923.16   874.2 1945.49   894.1 1958.27
   963.5 1991.02   973.5 1999.19    1033 2029.45  1052.9  2043.1  1092.6 2062.02
#Mann= 3 , 0 , 0
       0     .06       0   539.2    .045       0   554.2     .06       0
Bank Sta=539.2,554.2
XS Rating Curve= 0 ,0
Exp/Cntr=0.3,0.1

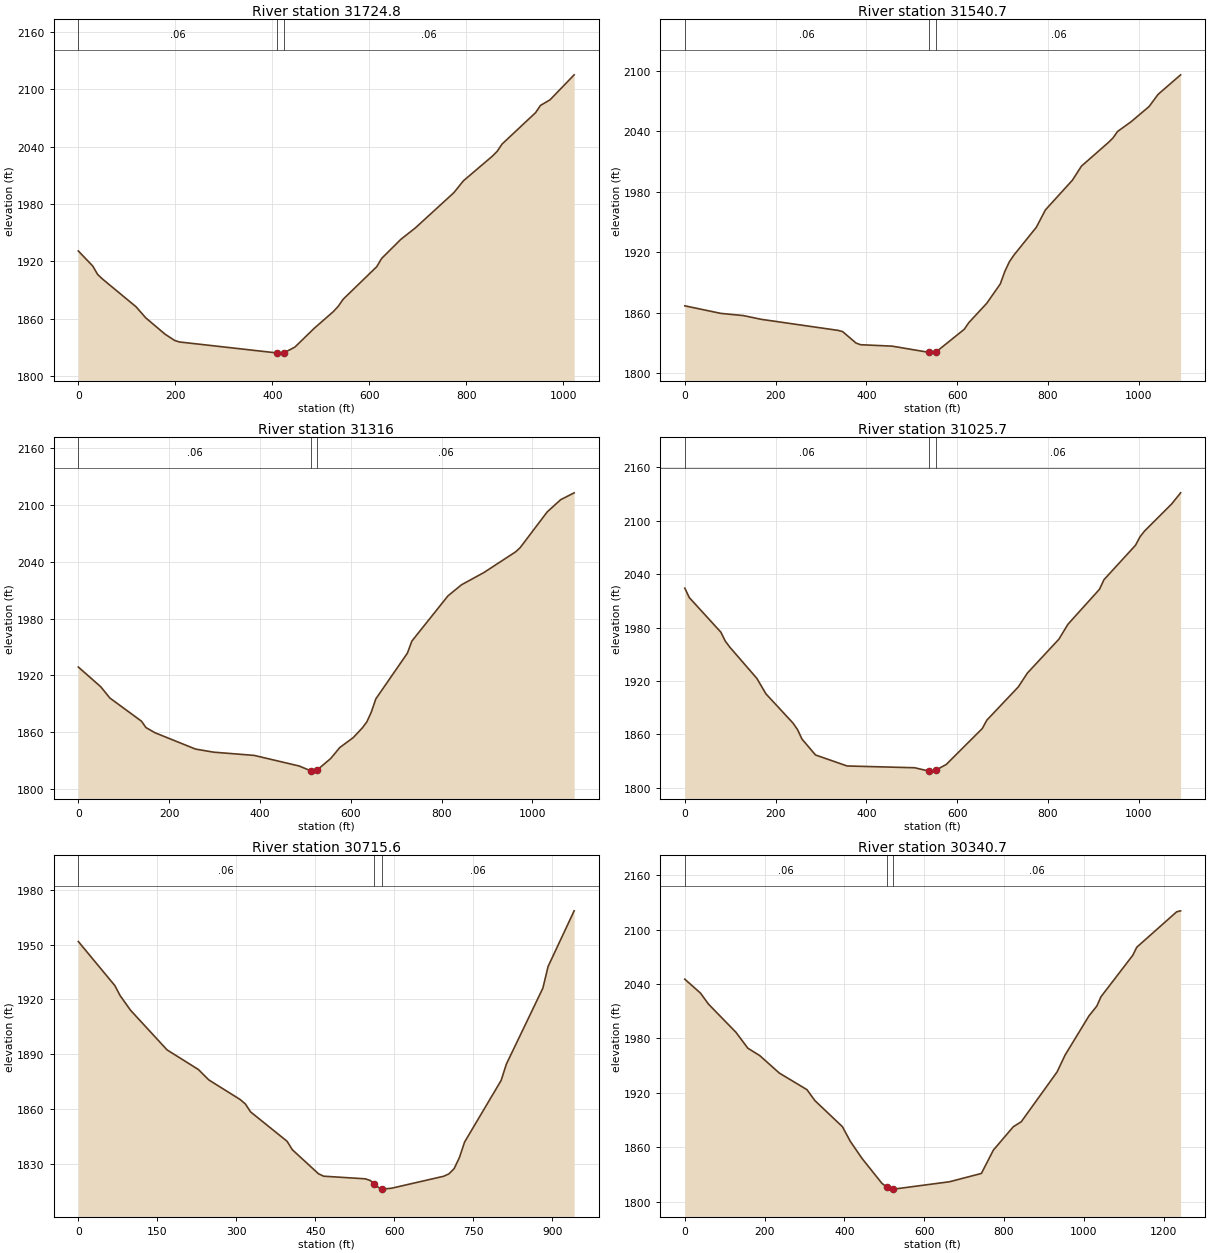
Type RM Length L Ch R = 1 ,31724.8 ,185.6,184,182.3
XS GIS Cut Line= 2
     1899655.293       230276.22     1898659.415      230045.365
#Sta/Elev= 30
       0 1930.97    29.8 1915.21    39.7 1906.52    49.6 1901.74   119.1  1872.6
     139 1861.06   178.6 1844.06   198.5 1837.45   208.4 1835.84     410 1824.34
   416.8 1824.17     425 1824.74   446.6 1830.52   486.3 1850.11     526 1867.68
     536 1873.16   545.9 1880.47   615.4 1914.63   625.3 1923.15     665 1943.16
   694.8 1955.05   774.2  1991.9     794 2004.35   853.6 2030.09   863.5 2035.11
   873.4 2042.62   942.9 2075.68   952.8 2083.13   972.7 2089.08  1022.3 2115.15
#Mann= 3 , 0 , 0
       0     .06       0     410    .045       0     425     .06       0
Bank Sta=410,425
XS Rating Curve= 0 ,0
Exp/Cntr=0.3,0.1

Type RM Length L Ch R = 1 ,31540.7 ,223,224.6,226.4
XS GIS Cut Line= 3
     1899825.531      230087.873     1899286.345      230002.234
      1898746.66      229919.033
#Sta/Elev= 30
       0 1866.64    79.4 1859.13     129 1856.95   168.8  1853.2   337.5 1842.26
   347.4  1841.1   377.2 1829.64   387.1 1828.02   456.6  1826.6   538.4 1820.36
     546 1819.66   553.4 1820.86   615.4  1843.3   625.4 1849.87   665.1 1869.21
   694.9 1888.44   704.8 1900.78   714.7  1910.3   724.7 1916.95   774.3 1944.72
   794.2 1961.92   853.7 1991.45   873.6 2005.42   933.2    2029   943.1 2033.42
     953 2039.77   982.8 2049.45  1022.5 2064.58  1042.4 2076.69    1092 2096.09
#Mann= 3 , 0 , 0
       0     .06       0   538.4    .045       0   553.4     .06       0
Bank Sta=538.4,553.4
XS Rating Curve= 0 ,0
Exp/Cntr=0.3,0.1

Type RM Length L Ch R = 1 ,31316   ,290.4,290.3,290.2
XS GIS Cut Line= 2
     1899831.242       229899.68      1898768.12      229650.207
#Sta/Elev= 30
       0 1928.71    49.6 1907.76    69.5 1895.93     139 1871.47   148.9 1864.73
   168.8  1859.2   258.1 1841.94   297.8 1838.68   387.2 1835.25   486.4 1824.03
   511.5 1819.03   516.2 1818.61   526.5    1820   555.9 1832.01   575.8 1843.56
   605.6 1854.14   625.4  1864.3   635.4 1870.71   645.3 1881.11   655.2 1895.01
   724.7 1943.38   734.6 1956.18     814 2003.96   843.8 2015.69   893.4 2028.72
     963 2050.53   972.9 2054.88  1032.4 2092.67  1062.2  2105.7    1092 2112.99
#Mann= 3 , 0 , 0
       0     .06       0   511.5    .045       0   526.5     .06       0
Bank Sta=511.5,526.5
XS Rating Curve= 0 ,0
Exp/Cntr=0.3,0.1

Type RM Length L Ch R = 1 ,31025.7 ,311.7,310.1,308.5
XS GIS Cut Line= 2
     1899925.771      229621.303     1898861.029      229376.342
#Sta/Elev= 30
       0 2024.26     9.9 2013.66    79.5 1974.74    89.4 1964.59    99.3 1957.85
   158.9 1922.76   178.8 1905.44   238.4  1872.6   248.3 1865.36   258.2 1854.65
     288 1836.72   357.6 1824.36   506.6 1822.36   537.7 1818.62   546.3 1818.56
   552.7 1819.53   576.1 1826.04   655.5 1866.42   665.5 1875.82     735 1913.27
   754.9 1928.78   824.4  1966.9   844.2  1983.6   913.8 2022.97   923.7 2033.76
   993.2 2072.49  1003.2 2082.02  1013.1 2088.46  1072.7 2118.81  1092.6  2131.4
#Mann= 3 , 0 , 0
       0     .06       0   537.7    .045       0   552.7     .06       0
Bank Sta=537.7,552.7
XS Rating Curve= 0 ,0
Exp/Cntr=0.3,0.1

Type RM Length L Ch R = 1 ,30715.6 ,387.8,374.9,359.1
XS GIS Cut Line= 2
     1900068.136      229298.877     1899137.976      229152.276
#Sta/Elev= 30
       0 1951.68    69.4 1927.55    79.3 1922.11    99.1 1914.09   168.5 1892.37
     228 1881.63   247.8 1875.94   307.3 1865.21   317.2 1862.78   327.1 1858.44
   396.5 1842.34   406.4 1837.73     456 1824.58   465.9 1823.24   545.2 1821.79
   555.1  1820.8   561.8 1818.74   574.9 1816.16   576.8 1816.17   594.7 1816.64
   693.8  1823.2   703.8  1824.5   713.7  1827.4   723.6 1833.36   733.5 1841.92
   802.9 1875.64   812.8 1884.54   882.2 1926.17   892.1 1938.02   941.6 1968.48
#Mann= 3 , 0 , 0
       0     .06       0   561.8    .045       0   576.8     .06       0
Bank Sta=561.8,576.8
XS Rating Curve= 0 ,0
Exp/Cntr=0.3,0.1

Type RM Length L Ch R = 1 ,30340.7 ,306.2,300,293
XS GIS Cut Line= 3
     1899948.567      228639.323     1899478.713      228846.963
     1898853.266      229221.642
#Sta/Elev= 30
       0 2045.29    39.5 2029.89    59.3 2017.87   128.4 1986.69   158.1 1969.21
   187.7 1961.17   237.1 1941.82   306.2 1923.58     326 1911.59   395.2 1882.73
   414.9 1866.62   444.5 1847.66   493.9 1820.49   506.2 1816.18   521.2 1814.12
   523.7    1814   663.5 1822.12   743.4 1831.28   773.4 1856.95   823.3 1882.69
   843.3  1888.2   933.2 1943.13   953.1 1961.63  1013.1 2004.88    1033 2015.83
    1043 2025.84  1122.9 2071.64  1132.9 2080.52  1232.8  2119.5  1242.8  2120.6
#Mann= 3 , 0 , 0
       0     .06       0   506.2    .045       0   521.2     .06       0
Bank Sta=506.2,521.2
XS Rating Curve= 0 ,0
Exp/Cntr=0.3,0.1

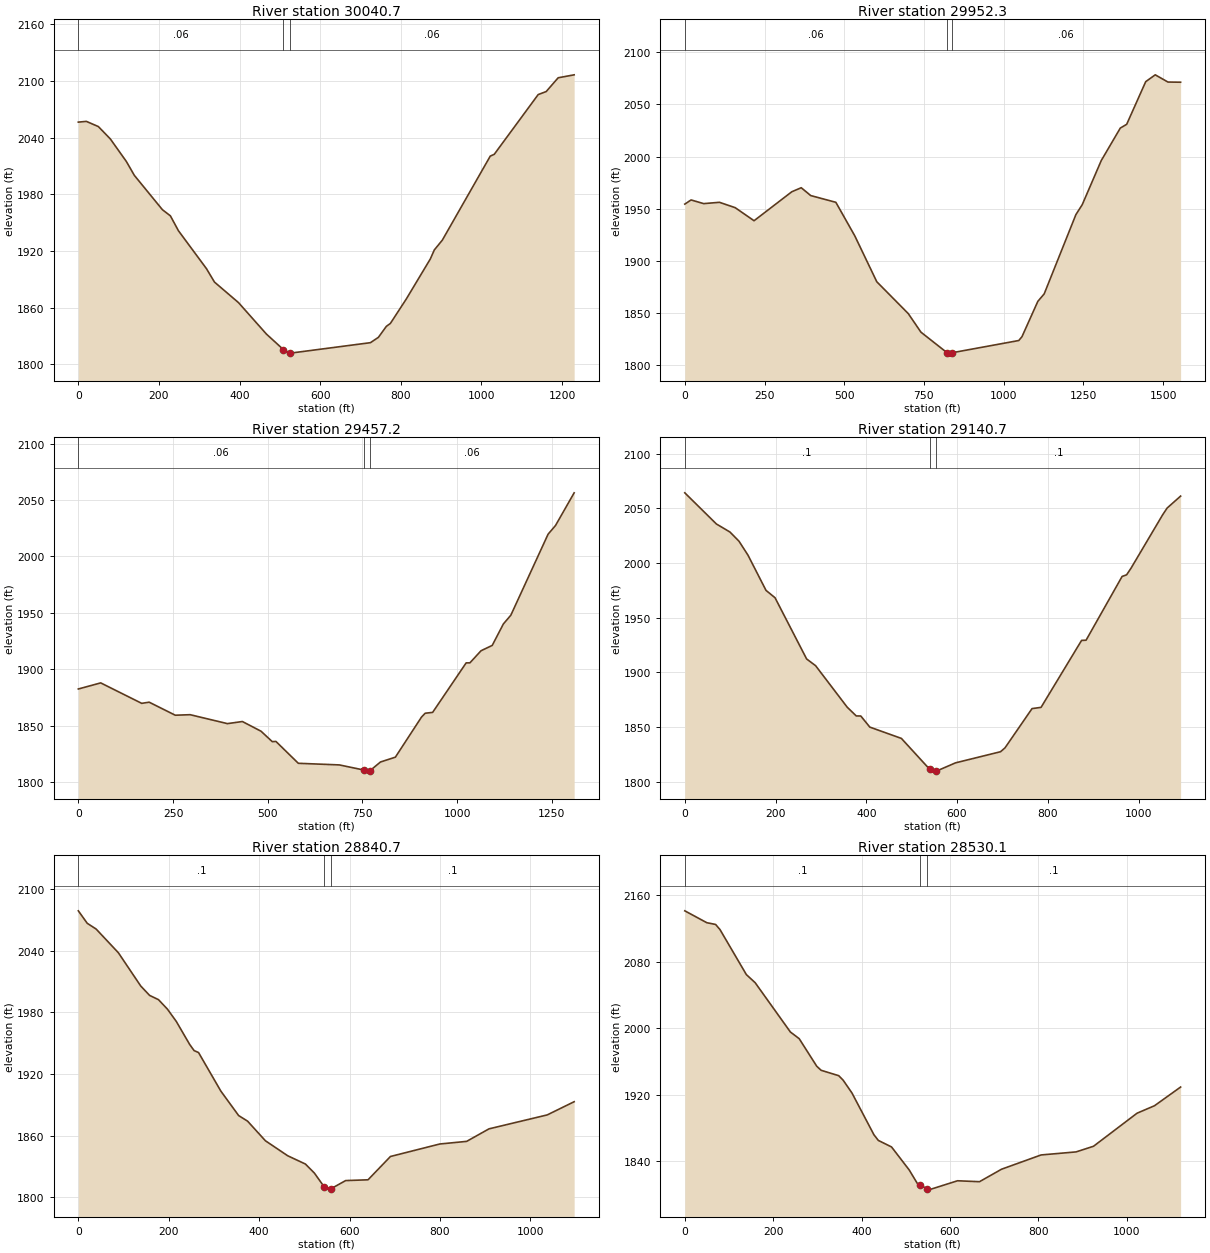
Type RM Length L Ch R = 1 ,30040.7 ,96.5,88.4,83.8
XS GIS Cut Line= 3
     1899674.114      228301.518     1899274.434      228628.554
     1898800.038      229161.606
#Sta/Elev= 30
       0 2056.51    19.9 2057.31    49.7  2051.8    79.4 2038.71   119.2 2014.78
     139 2000.08   208.6 1963.73   228.4 1957.23   248.3 1941.48   317.8 1901.32
   337.7 1887.08   397.2 1865.36   466.8  1831.9   508.9 1815.51   523.9  1812.1
   526.3  1811.8   724.6 1822.87   744.4 1828.52   764.2 1840.21   774.1 1843.25
   813.8 1869.29   873.2 1911.56   883.1 1921.11     903 1931.52  1021.9 2020.52
  1031.8 2022.42  1140.8 2085.71  1160.6 2088.89  1190.4  2103.5    1230 2106.62
#Mann= 3 , 0 , 0
       0     .06       0   508.9    .045       0   523.9     .06       0
Bank Sta=508.9,523.9
XS Rating Curve= 0 ,0
Exp/Cntr=0.3,0.1

Type RM Length L Ch R = 1 ,29952.3 ,501.2,495.1,489.1
XS GIS Cut Line= 4
     1899758.083      227979.465     1899282.892       228439.49
     1899104.274      228747.858     1898734.424      229137.624
#Sta/Elev= 30
       0 1954.51    19.7 1958.51    59.2 1954.99   108.6 1956.25   157.9 1951.14
   217.2 1938.58   335.6 1966.36   365.2 1970.23   394.9 1962.72   473.8 1956.24
   533.1 1924.13   602.2 1880.09     701 1849.56   740.6  1831.8   822.6 1812.07
   829.7 1811.69   837.6 1812.01  1047.6 1823.78  1057.6  1827.5  1107.3 1861.32
  1127.2 1868.46  1226.7 1944.48  1246.6 1954.02  1306.3 1996.34    1366 2027.43
  1385.9 2030.99  1445.6 2071.88  1475.5 2078.44  1515.3 2071.52  1555.1 2071.37
#Mann= 3 , 0 , 0
       0     .06       0   822.6    .045       0   837.6     .06       0
Bank Sta=822.6,837.6
XS Rating Curve= 0 ,0
Exp/Cntr=0.3,0.1

Type RM Length L Ch R = 1 ,29457.2 ,318,316.4,313.8
XS GIS Cut Line= 4
     1899087.424      227908.692     1898798.373      228294.785
     1898703.227      228646.754     1898482.088      229052.459
#Sta/Elev= 30
       0 1882.56    59.1 1887.96   167.3 1869.83     187 1870.87   255.9 1859.32
   295.3 1859.77   393.7 1851.86   433.1 1853.73   482.3 1845.15   511.9 1835.92
   521.7 1836.08   580.8 1816.71   689.2 1815.27   754.2  1810.7   768.1 1809.77
   769.2 1809.95   797.6 1817.85     837 1822.14   905.9 1857.61   915.7 1861.07
   935.4 1861.83  1023.9  1905.7  1033.7 1905.71  1063.2 1916.46  1092.7 1921.17
  1122.2 1940.23  1141.8 1947.92  1240.2 2019.73  1259.8 2027.45    1309 2056.39
#Mann= 3 , 0 , 0
       0     .06       0   754.2    .045       0   769.2     .06       0
Bank Sta=754.2,769.2
XS Rating Curve= 0 ,0
Exp/Cntr=0.3,0.1

Type RM Length L Ch R = 1 ,29140.7 ,291.4,300.1,308.2
XS GIS Cut Line= 3
     1898526.227      227942.878     1898423.176        228480.1
     1898343.987      229020.145
#Sta/Elev= 30
       0 2064.11    69.6 2035.64    99.5 2028.28   119.4 2019.91   139.2 2007.17
     179 1974.92   198.9 1968.18   268.5 1912.22   288.4 1906.01     358  1868.1
   377.9 1860.12   387.9 1860.07   407.8 1849.91   477.4 1839.57   539.5 1811.43
     547 1809.66   554.5 1809.66   596.6 1817.22   695.9  1827.4   705.8 1830.97
   765.3 1866.82   785.2 1867.96   874.5 1929.18   884.4 1929.35   963.8 1987.64
   973.8 1989.17   983.7 1995.34  1053.1 2043.95  1063.1 2050.22  1092.8 2061.13
#Mann= 3 , 0 , 0
       0      .1       0   539.5    .045       0   554.5      .1       0
Bank Sta=539.5,554.5
XS Rating Curve= 0 ,0
Exp/Cntr=0.3,0.1

Type RM Length L Ch R = 1 ,28840.7 ,321.4,310.6,301.3
XS GIS Cut Line= 3
     1898443.245      227910.531     1898144.916      228374.439
     1897879.396      228850.408
#Sta/Elev= 30
       0 2079.09    19.7 2066.94    39.4 2061.32    88.6 2038.22   137.9 2005.89
   157.6 1996.67   177.3  1992.5     197 1983.31   216.7 1971.25   246.2  1948.9
   256.1 1942.84   265.9 1940.95   315.2 1903.38   354.6 1879.53   374.3  1874.1
   413.7    1855   462.9 1840.41   502.3 1832.27     522 1823.51   544.1 1809.86
   551.6 1807.84   559.1  1808.3   591.2 1816.17   640.7 1816.93   690.3 1839.65
   799.3 1851.82   858.8 1854.38   908.3 1866.59  1037.1 1880.18  1096.6 1893.04
#Mann= 3 , 0 , 0
       0      .1       0   544.1    .045       0   559.1      .1       0
Bank Sta=544.1,559.1
XS Rating Curve= 0 ,0
Exp/Cntr=0.3,0.1

Type RM Length L Ch R = 1 ,28530.1 ,349.8,345.9,341.9
XS GIS Cut Line= 3
      1897964.49      227682.103      1897850.58      228520.373
     1897743.447       228774.63
#Sta/Elev= 30
       0 2141.04    49.8 2126.76    69.7 2124.66    79.6 2118.53   139.3 2064.36
   159.2 2054.63   238.9 1995.36   258.8 1987.35   298.6 1954.15   308.5  1949.3
   348.3 1942.82   358.3 1937.42   378.2 1922.07     428 1871.75   437.9 1864.99
   467.8 1857.13   507.6  1829.6   527.5 1812.07     533 1811.73     548  1806.5
   557.4 1806.42   617.1 1816.47   666.8 1815.35   716.6 1830.34   806.2 1847.51
   885.4 1851.18   924.8 1857.96  1023.3  1897.7  1062.8 1906.69  1121.9 1929.17
#Mann= 3 , 0 , 0
       0      .1       0     533    .045       0     548      .1       0
Bank Sta=533,548
XS Rating Curve= 0 ,0
Exp/Cntr=0.3,0.1

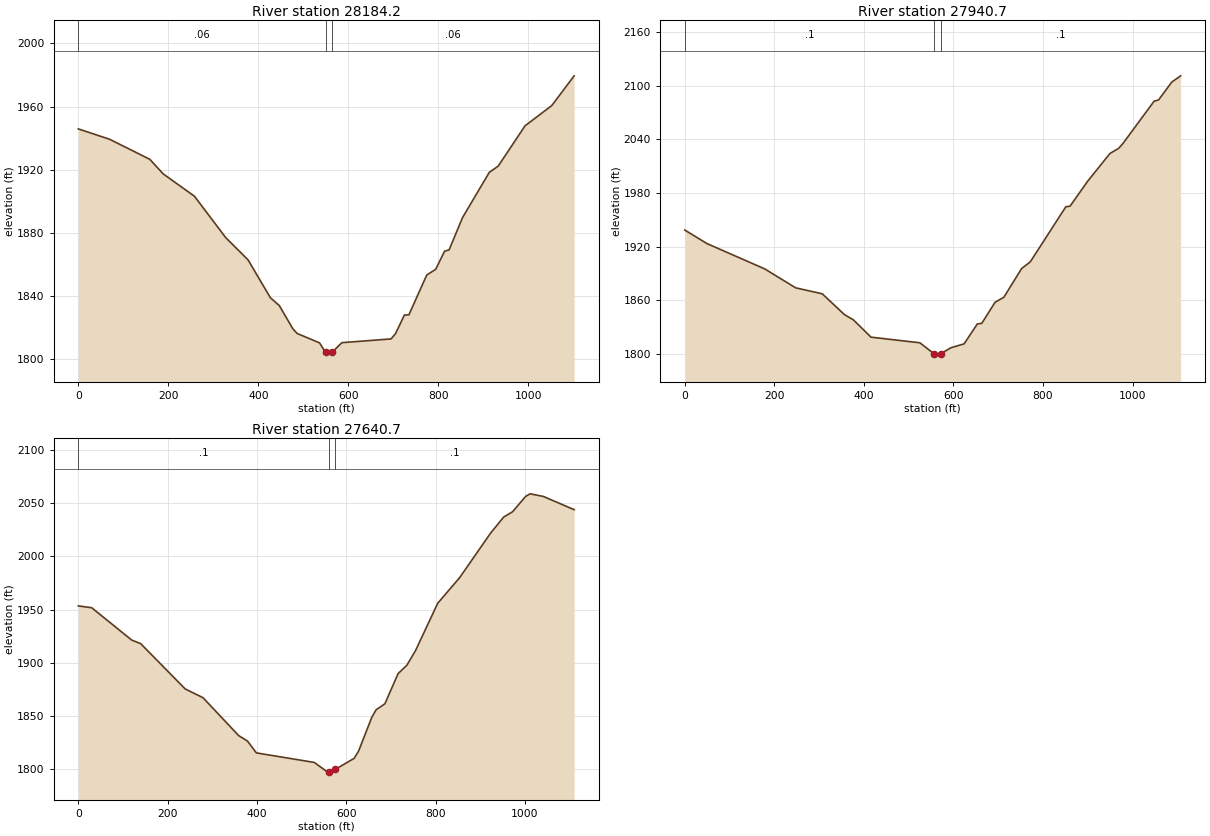
Type RM Length L Ch R = 1 ,28184.2 ,235.4,243.4,250.5
XS GIS Cut Line= 2
      1897526.14      227669.619     1897576.963      228770.467
#Sta/Elev= 30
       0 1945.81    69.5 1939.22   158.8 1926.52   188.6 1917.26   258.1 1903.08
   327.6 1876.82   377.3 1862.68   426.9 1838.66   446.8 1833.65   476.6 1819.05
   486.5 1815.97   536.1 1810.04   549.4 1804.01     556 1802.89   564.4 1804.21
   585.8 1810.16     695 1812.54   704.9 1815.86   724.8 1827.71   734.7 1827.82
   774.4 1853.09   794.2  1856.7   814.1 1868.22     824    1869   853.8 1889.46
   913.4 1918.23   933.2 1922.19   992.8 1947.75  1052.4 1960.66    1102 1979.48
#Mann= 3 , 0 , 0
       0     .06       0   549.4    .045       0   564.4     .06       0
Bank Sta=549.4,564.4
XS Rating Curve= 0 ,0
Exp/Cntr=0.3,0.1

Type RM Length L Ch R = 1 ,27940.7 ,291.5,299.9,308.3
XS GIS Cut Line= 3
     1897481.988       227660.12     1897311.282      228198.175
     1897165.245      228720.897
#Sta/Elev= 30
       0 1938.67    49.5 1923.54   178.3 1895.32   247.6 1874.11     307 1867.45
   356.5 1844.19   376.3 1838.44   415.9 1819.01   524.9 1812.74     557 1800.27
   564.5 1800.07     572  1800.7   594.1 1807.15   623.7 1811.54   653.3 1833.79
   663.2 1834.47   692.8 1857.96   712.5 1863.62     752 1895.55   771.7 1903.28
   850.7 1964.53   860.5 1965.45     900 1993.45   949.3 2024.12   969.1    2030
   978.9  2035.7    1048 2082.58  1057.9 2083.94  1087.5 2103.97  1107.2 2110.91
#Mann= 3 , 0 , 0
       0      .1       0     557    .045       0     572      .1       0
Bank Sta=557,572
XS Rating Curve= 0 ,0
Exp/Cntr=0.3,0.1

Type RM Length L Ch R = 1 ,27640.7 ,245.9,246.3,247.5
XS GIS Cut Line= 3
     1897403.958      227618.837      1897046.22      228060.383
     1896721.392      228494.347
#Sta/Elev= 30
       0 1953.41    29.9 1951.69   119.6 1921.32   139.6 1918.01   239.3 1875.48
   279.2 1867.26   358.9 1831.78   378.8 1826.56   398.8 1815.46   528.4 1806.52
   558.3 1797.42   560.8 1797.52   575.8 1800.05   617.6 1810.34   627.4 1816.94
     657 1848.63   666.8 1855.88   686.6 1861.58   716.1 1889.86   735.8 1897.77
   755.5 1911.73   804.8 1955.86   854.1 1979.99   923.1 2021.62   952.6 2036.76
   972.4 2041.73  1001.9 2056.21  1011.8 2058.57  1041.4 2056.12  1110.4 2043.71
#Mann= 3 , 0 , 0
       0      .1       0   560.8    .045       0   575.8      .1       0
Bank Sta=560.8,575.8
XS Rating Curve= 0 ,0
Exp/Cntr=0.3,0.1