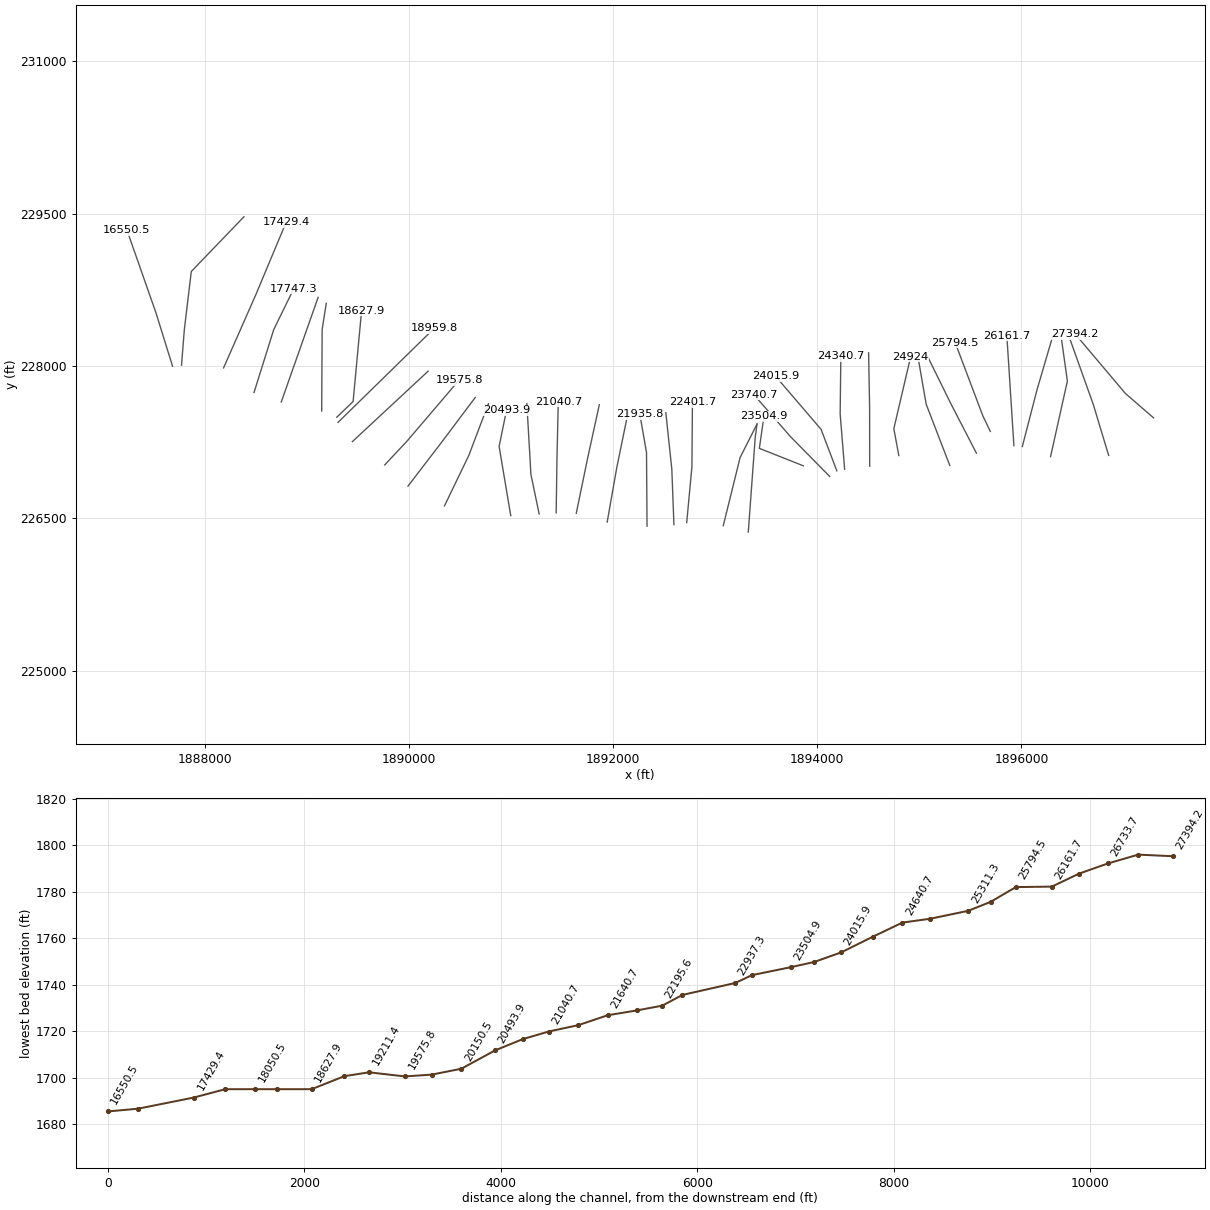
HEC-RAS study StnclCrk.prj: StnclCrk

--- StnclCrk.g01 (geometry) --- (continued)

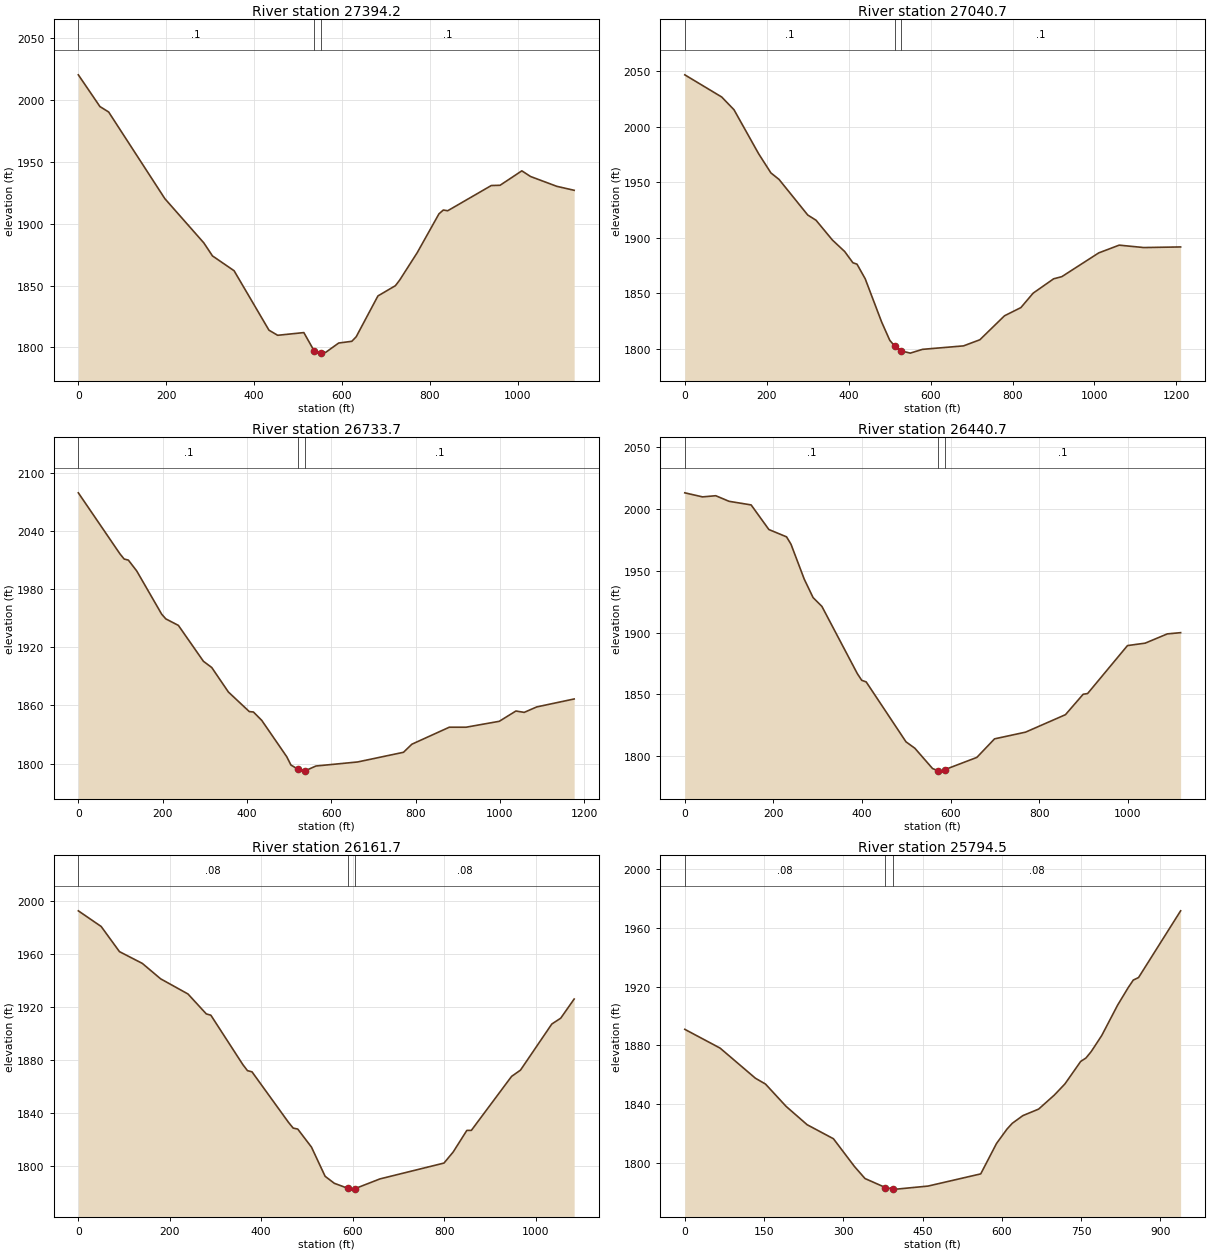
Type RM Length L Ch R = 1 ,27394.2 ,362.7,353.5,345.4
XS GIS Cut Line= 3
     1897294.943      227489.298     1897019.838      227728.389
     1896527.847      228313.309
#Sta/Elev= 30
       0 2020.47    49.2 1994.79      69  1990.4     197 1920.26   285.7 1884.48
   305.4 1873.95   354.6 1861.95     434 1813.85   453.8 1809.71   513.4  1811.9
   536.8 1797.16   543.2 1795.28   551.8 1795.33     563 1795.87   592.8 1803.46
   622.6 1804.84   632.5 1808.47   682.1 1841.56   721.8 1849.84   731.8 1854.49
   771.5 1876.55   821.1 1908.02     831 1911.07   840.9 1910.48   940.2  1930.9
   960.1 1931.09  1009.7 1942.78  1029.5  1938.2  1089.1 1930.27  1128.8 1927.04
#Mann= 3 , 0 , 0
       0      .1       0   536.8    .045       0   551.8      .1       0
Bank Sta=536.8,551.8
XS Rating Curve= 0 ,0
Exp/Cntr=0.3,0.1

Type RM Length L Ch R = 1 ,27040.7 ,318.5,307,294.4
XS GIS Cut Line= 3
     1896854.876      227119.593     1896705.179      227618.038
     1896474.264       228268.18
#Sta/Elev= 30
       0 2046.94    90.1 2026.94   120.1 2015.46   180.2 1975.81   210.2 1958.49
   230.2 1952.56   300.2 1920.49   320.3 1915.83   360.3 1897.97   390.3 1887.59
   410.4 1877.45   420.4 1876.18   440.4 1863.02   480.4 1824.14   500.4 1807.51
   512.9 1802.14   527.9 1798.04   550.4 1795.96   580.4 1799.37   680.4 1802.49
   720.4 1808.03   780.4 1829.62   820.4 1837.01   850.4 1850.05   900.4 1862.98
   920.4 1864.92  1010.4 1886.33  1060.4 1893.34  1120.4 1891.17  1210.4 1891.72
#Mann= 3 , 0 , 0
       0      .1       0   512.9    .045       0   527.9      .1       0
Bank Sta=512.9,527.9
XS Rating Curve= 0 ,0
Exp/Cntr=0.3,0.1

Type RM Length L Ch R = 1 ,26733.7 ,293.8,292.9,291.3
XS GIS Cut Line= 3
     1896285.668      227107.747     1896450.283      227851.399
     1896392.951      228262.212
#Sta/Elev= 30
       0 2079.76    98.9  2016.6   108.8 2011.32   118.7 2010.24   138.5 1999.06
   197.8 1954.32   207.7 1949.47   237.4 1942.77   296.8 1905.68   316.5 1899.27
   356.1 1873.91   405.6 1853.72   415.4 1853.27   435.2 1844.62   494.6    1807
   504.5 1798.45   522.1    1794   534.2 1792.18   537.1  1792.3   563.8 1797.47
   662.7 1801.65   771.5 1811.65   791.3 1819.98   880.2 1837.56   919.7 1837.54
   998.7 1843.66  1038.2  1854.3  1057.9  1852.9  1087.6 1858.52  1176.4 1866.74
#Mann= 3 , 0 , 0
       0      .1       0   522.1    .045       0   537.1      .1       0
Bank Sta=522.1,537.1
XS Rating Curve= 0 ,0
Exp/Cntr=0.3,0.1

Type RM Length L Ch R = 1 ,26440.7 ,273.3,279.3,286.1
XS GIS Cut Line= 3
     1896008.978       227207.32     1896153.658      227768.279
     1896304.907       228286.79
#Sta/Elev= 30
       0 2013.22      40 2009.94    69.9 2010.87    99.9 2006.35   149.8 2003.42
   189.8  1983.5   229.7 1977.57   239.7 1971.64   269.7 1943.28   289.7 1928.33
   309.6 1921.19   389.5  1866.8   399.5 1861.35   409.5 1860.09   499.4 1811.55
   519.4 1806.35   559.3 1789.93   571.8 1788.16   579.3 1787.82   586.8 1788.99
   659.3 1798.92   699.3 1813.95   769.4  1819.4   859.4 1833.53   899.4 1850.09
   909.4 1850.65   999.4  1889.5  1039.4 1891.47  1089.4 1898.97  1119.4 1899.96
#Mann= 3 , 0 , 0
       0      .1       0   571.8    .045       0   586.8      .1       0
Bank Sta=571.8,586.8
XS Rating Curve= 0 ,0
Exp/Cntr=0.3,0.1

Type RM Length L Ch R = 1 ,26161.7 ,358.3,366.6,374.9
XS GIS Cut Line= 3
     1895926.419      227215.677     1895872.303      228063.718
     1895857.138      228297.944
#Sta/Elev= 30
       0 1992.88      50 1981.01      90 1961.98     140 1953.07     180 1941.41
   239.9 1929.91   279.9 1914.84   289.9 1913.85   359.9 1876.44   369.9 1871.91
   379.9 1870.98   459.9 1832.65   469.9 1828.42   479.9 1827.66   509.9 1814.03
   539.8 1791.91   559.8 1786.63   589.1 1782.86   599.8  1782.2   604.1 1782.43
   659.8 1789.94   799.8 1801.93   819.8 1810.27   849.8 1826.66   859.6 1826.66
   947.6 1867.53   967.1 1872.29  1035.6 1907.18  1055.1  1911.6  1084.5 1926.11
#Mann= 3 , 0 , 0
       0     .08       0   589.1    .045       0   604.1     .08       0
Bank Sta=589.1,604.1
XS Rating Curve= 0 ,0
Exp/Cntr=0.3,0.1

Type RM Length L Ch R = 1 ,25794.5 ,251.4,253.7,255.6
XS GIS Cut Line= 3
     1895695.371      227355.987     1895621.227      227511.014
     1895351.615      228228.856
#Sta/Elev= 30
       0 1890.92    66.8 1878.12   133.7 1857.58   152.8  1853.6   191.8 1838.38
   231.6 1825.89   281.4 1816.33   321.2  1797.4   341.1 1789.22   379.9 1783.05
   394.9 1782.12   400.9 1781.99   460.6 1784.08   560.2 1792.38   590.1 1813.11
     610 1822.95     620 1826.88   639.9 1832.09   669.8 1836.54   699.6 1846.13
   719.6 1853.71   749.4 1869.02   759.4 1871.37   769.4 1875.78   789.3 1886.72
   819.2 1907.32   839.1 1919.19     849 1924.49     859 1926.23   938.6 1971.69
#Mann= 3 , 0 , 0
       0     .08       0   379.9    .045       0   394.9     .08       0
Bank Sta=379.9,394.9
XS Rating Curve= 0 ,0
Exp/Cntr=0.3,0.1

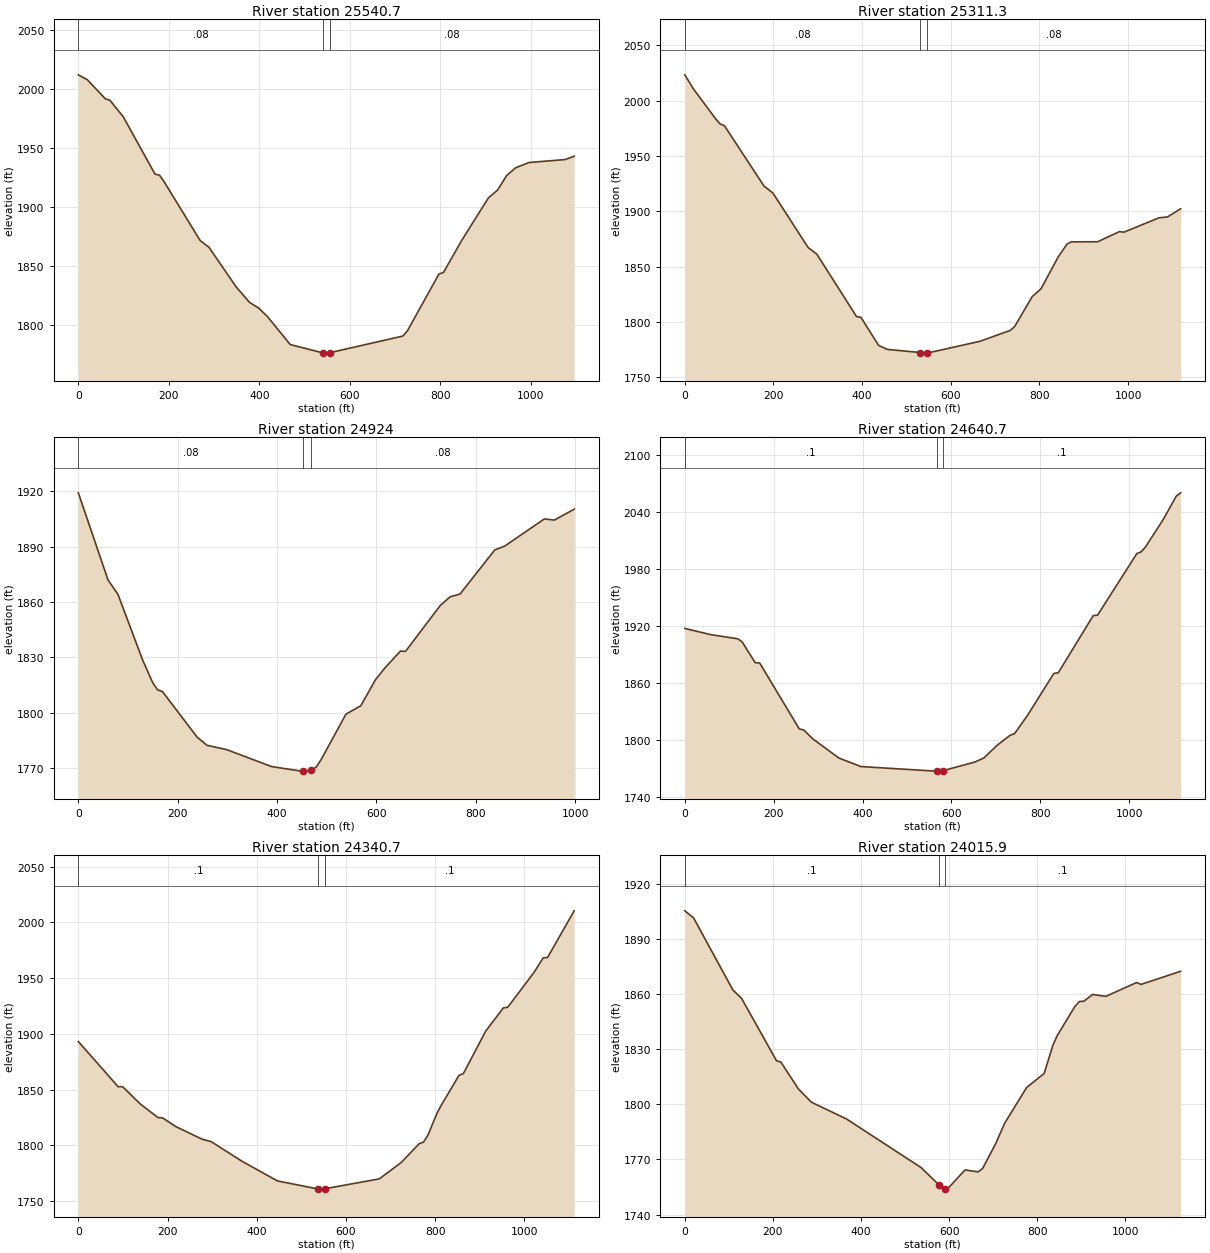
Type RM Length L Ch R = 1 ,25540.7 ,231.9,229.5,227.5
XS GIS Cut Line= 3
     1895559.064       227142.07     1895308.391      227629.472
     1895067.055      228121.359
#Sta/Elev= 30
       0 2012.12    19.9 2007.96    59.8 1991.72    69.8 1990.57    99.6  1976.3
   169.4  1927.8   179.4 1926.86   189.3 1921.52   269.1 1871.44     289 1865.51
   348.8    1832   378.7 1818.73   398.6 1813.98   418.5 1806.56   468.4 1782.97
   540.6 1775.91   548.1 1775.69   555.6 1776.02   717.4  1790.2   727.4 1794.62
   797.1 1842.88   807.1 1844.18   846.9  1871.1   906.7 1907.72   926.6 1914.16
   946.6 1926.49   966.5 1933.12   996.4 1937.64  1076.1 1940.13    1096 1942.99
#Mann= 3 , 0 , 0
       0     .08       0   540.6    .045       0   555.6     .08       0
Bank Sta=540.6,555.6
XS Rating Curve= 0 ,0
Exp/Cntr=0.3,0.1

Type RM Length L Ch R = 1 ,25311.3 ,400.8,387.2,373.6
XS GIS Cut Line= 3
     1895298.056      227020.947     1895066.838      227623.914
     1894986.288      228089.753
#Sta/Elev= 30
       0 2023.28    19.9  2010.3    69.6 1983.55    79.5 1978.97    89.4  1977.3
   178.8 1922.72   198.7 1916.52   278.2 1867.23     298 1861.14   387.5  1804.8
   397.4 1804.11   437.1 1778.84     457 1775.17   531.7 1772.31   546.4 1771.79
   546.7 1771.82   665.5 1782.46   734.4 1792.36   744.3 1795.94   783.7 1822.86
   803.4 1829.82   842.8 1859.06   862.5 1870.41   872.3 1872.34   931.4 1872.44
   980.6 1881.64   990.5 1881.08  1069.3 1894.01    1089 1894.89  1118.5  1902.2
#Mann= 3 , 0 , 0
       0     .08       0   531.7    .045       0   546.7     .08       0
Bank Sta=531.7,546.7
XS Rating Curve= 0 ,0
Exp/Cntr=0.3,0.1

Type RM Length L Ch R = 1 ,24924   ,278.2,283.3,288.7
XS GIS Cut Line= 3
     1894798.911      227118.392     1894750.044      227382.949
     1894915.393       228093.12
#Sta/Elev= 30
       0 1919.18    59.8 1871.95    79.7 1864.22   129.5 1828.56   149.5 1816.43
   159.4 1812.46   169.4 1811.48   239.1 1786.81   259.1 1782.34     299 1779.99
   388.9 1770.85   448.8 1768.37   452.9 1768.38   467.9 1768.76   478.8 1770.54
   488.8 1774.62   538.7 1799.22   568.7 1803.79   598.6 1818.07   618.6 1824.72
   648.6 1833.46   658.6 1833.23   728.5 1858.08   748.5 1862.83   768.5 1864.36
   838.4 1888.23   858.4 1890.32   938.3 1905.04   958.2 1904.41   998.2 1910.32
#Mann= 3 , 0 , 0
       0     .08       0   452.9    .045       0   467.9     .08       0
Bank Sta=452.9,467.9
XS Rating Curve= 0 ,0
Exp/Cntr=0.3,0.1

Type RM Length L Ch R = 1 ,24640.7 ,298.1,300,299.4
XS GIS Cut Line= 3
     1894513.372      227014.115     1894512.657      227588.651
     1894502.844      228129.526
#Sta/Elev= 30
       0 1916.93    59.4 1910.35   118.9 1906.08   128.8    1903   158.5 1880.83
   168.4 1880.61   257.6 1811.11   267.5 1810.11   287.3 1800.95   346.7 1780.51
   396.2 1771.53   564.6 1766.72     567 1766.76     582 1767.34   653.2 1776.38
   672.9  1780.6   702.4 1793.83   731.9 1804.49   741.7  1806.1   771.2  1825.5
   830.3 1869.63   840.1 1870.15   918.8 1930.44   928.6 1930.92  1017.1 1995.84
    1027 1997.64  1036.8    2003  1076.2  2031.5  1105.7 2056.27  1115.5 2059.75
#Mann= 3 , 0 , 0
       0      .1       0     567    .045       0     582      .1       0
Bank Sta=567,582
XS Rating Curve= 0 ,0
Exp/Cntr=0.3,0.1

Type RM Length L Ch R = 1 ,24340.7 ,311.4,324.7,340
XS GIS Cut Line= 3
     1894268.036      226984.027     1894224.158      227527.925
     1894230.811      228093.713
#Sta/Elev= 30
       0 1893.09    89.3 1852.53    99.2 1852.58   138.9 1837.06   178.6 1824.84
   188.5 1824.67   218.3 1816.83   277.8 1805.41   297.6 1803.32   367.1 1785.62
   446.4 1768.01   538.2 1760.72   545.7 1760.65   553.2 1761.04   674.7 1769.84
   724.4 1784.72     764  1801.4     774  1802.9   783.9 1809.27   803.8 1828.51
   813.7 1836.02   853.4 1862.72   863.3 1864.37     913  1902.3   952.7 1923.22
   962.6 1923.86  1022.2 1955.46    1042 1968.15  1051.9 1968.49  1111.5 2010.36
#Mann= 3 , 0 , 0
       0      .1       0   538.2    .045       0   553.2      .1       0
Bank Sta=538.2,553.2
XS Rating Curve= 0 ,0
Exp/Cntr=0.3,0.1

Type RM Length L Ch R = 1 ,24015.9 ,273.6,275.2,275.4
XS GIS Cut Line= 3
     1894191.411      226968.126     1894037.258      227376.208
     1893589.879      227900.543
#Sta/Elev= 30
       0 1905.35    19.8 1901.56   109.1  1862.3   128.9 1857.72   208.2 1823.75
   218.1 1823.03   257.8 1808.43   287.5 1801.16   366.8  1792.1   536.1 1765.66
   576.6 1756.26   591.6 1753.94     596 1753.87     636 1764.32     666 1763.27
     676  1765.1   705.9 1778.71   725.9 1789.67   775.9 1809.16   815.8 1816.86
   835.8 1832.36   845.8 1837.61   885.7 1853.35   895.7 1855.98   905.7 1856.13
   925.7 1859.82   955.7 1858.79  1025.6 1866.33  1035.6  1865.3  1125.5 1872.44
#Mann= 3 , 0 , 0
       0      .1       0   576.6    .045       0   591.6      .1       0
Bank Sta=576.6,591.6
XS Rating Curve= 0 ,0
Exp/Cntr=0.3,0.1

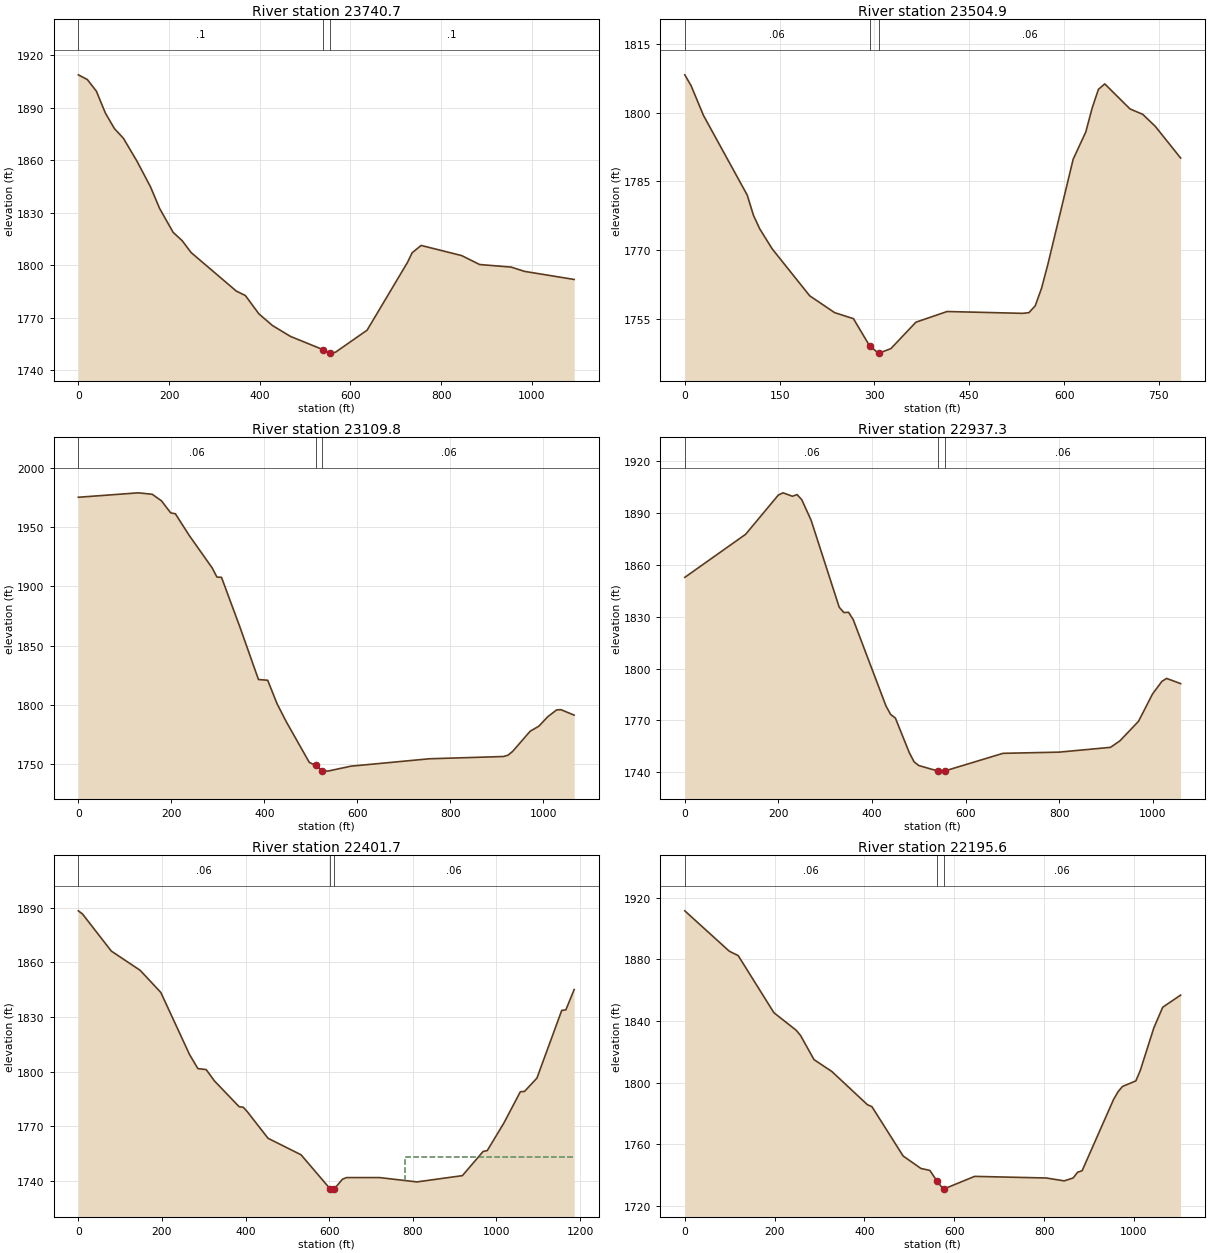
Type RM Length L Ch R = 1 ,23740.7 ,226.4,235.8,246.6
XS GIS Cut Line= 3
     1894121.662      226912.573      1893738.38       227303.44
     1893380.601      227715.542
#Sta/Elev= 30
       0  1908.7    19.9    1906    39.8 1899.35    59.7 1886.84    79.6 1877.98
    99.5 1872.42   129.4 1859.33   159.2 1844.69   179.2 1832.38     209 1818.74
   228.9 1813.98   248.8 1807.15   348.4 1785.15   368.3 1782.63   398.1 1772.17
     428 1765.51   467.8 1759.27   539.9 1751.68   554.9 1749.88   557.4 1749.73
   567.3  1750.3   636.7 1762.85     726 1801.68     736 1807.08   755.8 1811.24
   845.1 1805.46   884.8 1800.34   954.3 1798.87     984 1796.42  1093.2 1791.81
#Mann= 3 , 0 , 0
       0      .1       0   539.9    .045       0   554.9      .1       0
Bank Sta=539.9,554.9
XS Rating Curve= 0 ,0
Exp/Cntr=0.3,0.1

Type RM Length L Ch R = 1 ,23504.9 ,424,395.2,366.4
XS GIS Cut Line= 3
     1893863.696      227017.288     1893432.317      227189.165
     1893477.814      227505.959
#Sta/Elev= 30
       0 1808.25     9.9  1805.9    29.6 1799.38    98.8    1782   108.7 1777.58
   118.6 1774.64   138.3 1770.27   197.6 1760.04   237.1 1756.36   266.8 1755.05
   292.4 1749.11   306.3 1747.53   307.4 1747.55     326 1748.51   365.6 1754.28
     415 1756.61   534.4 1756.21   544.4 1756.36   554.4 1757.86   564.4 1761.69
   574.4 1766.91   614.4 1789.84   634.4 1795.78   644.4 1800.98   654.4 1805.09
   664.4 1806.27   704.4  1800.8   724.4 1799.64   744.4    1797   784.4  1790.1
#Mann= 3 , 0 , 0
       0     .06       0   292.4    .045       0   307.4     .06       0
Bank Sta=292.4,307.4
XS Rating Curve= 0 ,0
Exp/Cntr=0.3,0.1

Type RM Length L Ch R = 1 ,23109.8 ,176.2,172.5,168.8
XS GIS Cut Line= 3
     1893324.015      226365.447     1893391.875       227297.01
     1893409.506      227428.441
#Sta/Elev= 30
       0 1975.21   129.2 1978.95     159 1977.72   178.9 1972.18   198.7 1962.03
   208.7  1961.3   238.5 1943.03   288.2 1915.43   298.1 1907.88     308 1907.62
   347.8 1865.48   387.5 1821.42   407.4 1820.77   427.3 1801.15   447.1 1785.94
   496.8 1751.52   510.2 1748.85   525.2 1744.55   536.6  1744.1   586.2 1748.27
   755.2 1754.52   914.2 1756.43   924.1 1757.48     934 1760.65   971.9 1777.74
   990.9  1782.1  1009.8    1790  1028.8 1795.73  1038.2 1795.97  1066.6 1791.36
#Mann= 3 , 0 , 0
       0     .06       0   510.2    .045       0   525.2     .06       0
Bank Sta=510.2,525.2
XS Rating Curve= 0 ,0
Exp/Cntr=0.3,0.1

Type RM Length L Ch R = 1 ,22937.3 ,528.8,535.5,541.7
XS GIS Cut Line= 3
     1893078.891      226428.343     1893243.588      227098.171
     1893409.506      227428.441
#Sta/Elev= 30
       0 1852.83     130 1877.76   199.9 1900.48   209.9 1901.75   229.9 1899.77
   239.9 1900.72   249.9 1897.79   269.9 1885.88   329.9 1835.57   339.9 1832.47
   349.9 1832.62   359.9 1828.37   429.9 1778.37   439.9 1773.46   449.9 1771.45
   479.8 1751.31   489.8 1746.13   499.8 1743.95   541.3 1740.72   549.8  1740.7
   556.3 1740.86   679.8    1751   799.7 1751.69   909.5 1754.46   929.5 1758.17
   969.5 1769.56   999.4 1785.35  1019.4 1792.64  1029.4 1794.35  1059.4 1791.36
#Mann= 3 , 0 , 0
       0     .06       0   541.3    .045       0   556.3     .06       0
Bank Sta=541.3,556.3
XS Rating Curve= 0 ,0
Exp/Cntr=0.3,0.1

Type RM Length L Ch R = 1 ,22401.7 ,203.3,206,208.6
XS GIS Cut Line= 3
      1892720.61      226458.839     1892771.768      227008.862
     1892776.823       227642.45
#Sta/Elev= 30
       0 1888.29     9.9 1886.59    78.9  1866.2     148 1855.63   197.3  1843.5
   266.3 1809.31   286.1 1801.69   305.8 1801.18   325.5 1794.98   384.7  1780.8
   394.6  1780.5   404.4 1778.03   453.8 1763.48   532.7 1754.43   601.9 1735.85
   611.8 1735.58   631.6 1740.98   641.5 1741.91   720.7 1741.91   809.8 1739.54
   918.7 1742.98   968.2 1756.24   978.1 1756.73  1017.7 1771.76  1057.3 1789.03
  1067.2 1789.19  1096.9 1796.48  1156.3 1833.65  1166.2 1833.95    1186 1845.09
#Mann= 3 , 0 , 0
       0     .06       0   601.9    .045       0   611.8     .06       0
#XS Ineff= 2 , 0
                          781.07          1753.4
Permanent Ineff=
       F       F
Bank Sta=601.9,611.8
XS Rating Curve= 0 ,0
Exp/Cntr=0.3,0.1

Type RM Length L Ch R = 1 ,22195.6 ,262.3,259.9,257.5
XS GIS Cut Line= 3
     1892595.464      226438.878      1892574.83      226984.071
     1892516.166      227539.319
#Sta/Elev= 30
       0 1911.46    99.2 1885.24     119 1882.39   198.4 1845.38     248    1834
   257.9 1830.52   287.7 1814.94   327.4 1807.25   406.7 1785.69   416.6 1784.45
   486.1 1752.44   525.7 1744.36   545.6  1743.1   561.7  1736.1   575.5 1730.95
   576.7 1731.04   645.3 1739.22   804.8 1738.17   844.7 1736.31   864.6 1738.19
   874.6  1741.9   884.6 1742.88   954.4 1788.99   964.3 1793.97   974.3 1797.52
  1004.2 1801.14  1014.2 1808.01  1044.1  1835.4    1064 1848.91  1103.9  1856.8
#Mann= 3 , 0 , 0
       0     .06       0   561.7    .045       0   576.7     .06       0
Bank Sta=561.7,576.7
XS Rating Curve= 0 ,0
Exp/Cntr=0.3,0.1

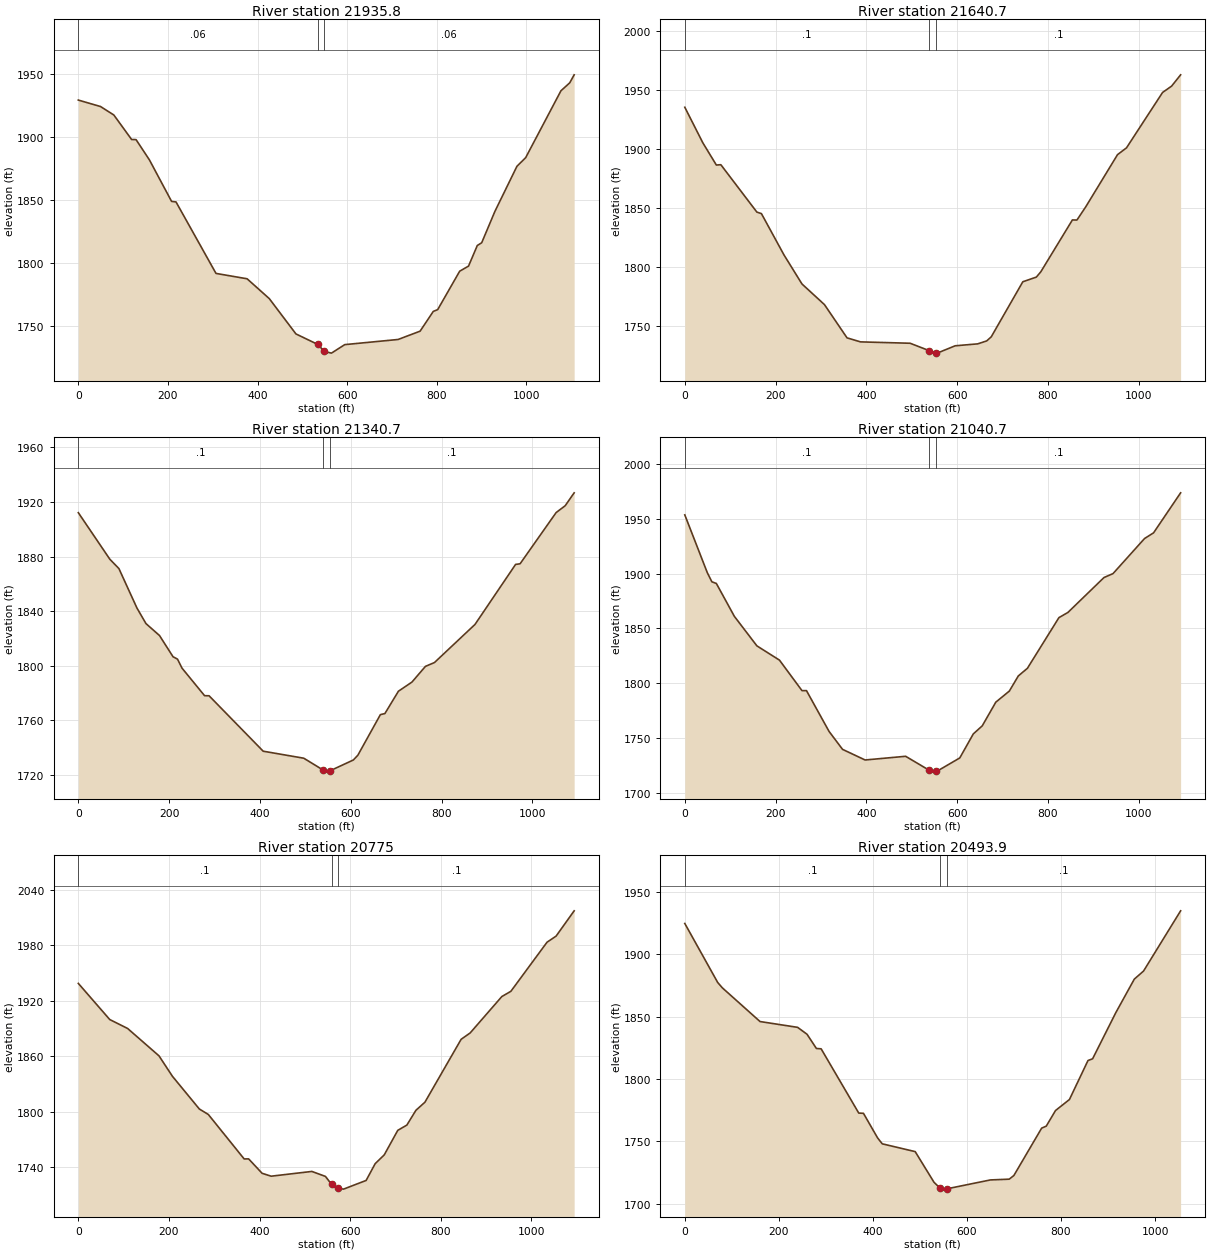
Type RM Length L Ch R = 1 ,21935.8 ,299.1,295,290.3
XS GIS Cut Line= 3
     1892331.951      226423.684     1892326.908      227147.038
     1892261.499      227524.389
#Sta/Elev= 30
       0 1929.38    49.6 1924.25    79.3 1917.53   118.9 1898.14   128.8 1898.06
   158.6 1882.01   208.1  1849.1     218 1848.67   307.2 1792.05   376.6  1787.8
   426.1 1772.09   485.6  1744.1   534.2 1735.81   549.2 1730.23   564.8  1728.9
   594.6 1735.64   713.5 1739.71   762.6 1746.29   792.1 1761.96   801.9 1763.38
     851 1793.82   870.7 1797.84   890.3 1814.18   900.1 1816.35   929.6 1841.21
   978.7  1876.9   998.3 1883.81  1076.9 1936.73  1096.5 1943.03  1106.4 1949.38
#Mann= 3 , 0 , 0
       0     .06       0   534.2    .045       0   549.2     .06       0
Bank Sta=534.2,549.2
XS Rating Curve= 0 ,0
Exp/Cntr=0.3,0.1

Type RM Length L Ch R = 1 ,21640.7 ,300.7,300,299.7
XS GIS Cut Line= 3
     1891941.581      226463.942     1892035.845      227001.696
     1892145.275      227536.886
#Sta/Elev= 30
       0 1935.18    39.7 1905.08    69.5 1886.21    79.4 1886.49   158.8 1846.32
   168.8 1845.05   218.4 1810.11   258.1 1785.44   307.7 1767.92   357.4 1739.76
   387.1 1736.36   496.3  1735.2   538.5 1728.92   553.5 1726.96   555.9 1726.83
   595.6 1733.04   645.3 1734.68   665.1 1737.19   675.1 1740.67   744.6  1787.3
   774.4 1791.26   784.3 1795.79   853.8 1839.68   863.8 1839.59   883.6 1851.04
   953.2 1895.01     973 1900.79  1052.5 1947.74  1072.4 1953.09  1092.2 1962.65
#Mann= 3 , 0 , 0
       0      .1       0   538.5    .045       0   553.5      .1       0
Bank Sta=538.5,553.5
XS Rating Curve= 0 ,0
Exp/Cntr=0.3,0.1

Type RM Length L Ch R = 1 ,21340.7 ,295.7,299.9,304.3
XS GIS Cut Line= 3
     1891638.709      226550.259     1891748.441      227085.377
     1891864.437      227618.867
#Sta/Elev= 30
       0 1912.16    69.5 1877.98    89.4 1871.17   129.1 1842.24     149  1830.8
   178.8 1822.05   208.6 1806.48   218.5 1804.71   228.4 1798.12   278.1  1777.9
     288 1777.84   407.2 1737.18   496.6 1732.04   538.8 1723.44   546.2 1722.56
   553.8  1722.7   605.8 1730.73   615.7 1734.21   665.4 1764.02   675.3 1764.79
   705.1 1781.18   734.9 1787.89   764.6 1799.41   784.5 1802.23   873.8 1830.19
   963.2 1874.22   973.1 1874.69  1052.5 1912.25  1072.4 1917.26  1092.2 1926.74
#Mann= 3 , 0 , 0
       0      .1       0   538.8    .045       0   553.8      .1       0
Bank Sta=538.8,553.8
XS Rating Curve= 0 ,0
Exp/Cntr=0.3,0.1

Type RM Length L Ch R = 1 ,21040.7 ,264.1,265.7,267.6
XS GIS Cut Line= 3
     1891441.699       226554.52     1891449.747      227100.457
     1891462.361      227646.334
#Sta/Elev= 30
       0 1953.67    49.6 1900.89    59.6 1892.62    69.5 1891.08   109.2 1861.06
   158.8 1834.14   208.5 1821.12   258.1 1793.29     268 1793.28   317.7 1756.08
   347.4  1739.7   397.1    1730   486.4 1733.37   538.5 1720.58   553.5 1719.85
   555.9 1719.83   605.6 1731.87   635.4 1753.79   655.2  1761.2     685 1782.78
   714.8 1792.89   734.6 1806.74   754.5 1813.62     824 1859.92   843.8 1864.64
   923.2 1896.49   943.1 1900.08  1012.6 1932.11  1032.4 1937.28    1092  1973.8
#Mann= 3 , 0 , 0
       0      .1       0   538.5    .045       0   553.5      .1       0
Bank Sta=538.5,553.5
XS Rating Curve= 0 ,0
Exp/Cntr=0.3,0.1

Type RM Length L Ch R = 1 ,20775   ,278.6,281,283.5
XS GIS Cut Line= 3
     1891274.964      226543.795     1891194.539      226931.349
     1891154.412       227629.12
#Sta/Elev= 30
       0 1938.84    69.3 1899.82   108.8 1890.15   178.1 1860.55   207.8 1838.45
   267.2  1803.1     287 1797.22   366.1 1749.16     376 1749.22   405.8 1733.63
   425.8 1730.52   515.6 1735.66   545.6 1730.27   559.3 1721.55   574.3 1717.74
   585.5 1716.54   635.4 1725.92   655.4 1744.06   675.4 1753.54   705.3 1780.07
   725.3 1785.73   745.3 1801.68   765.2 1810.45   845.1 1878.39   865.1  1885.3
     935 1924.62     955  1930.3  1034.8 1983.33  1054.8 1989.93  1094.7 2017.26
#Mann= 3 , 0 , 0
       0      .1       0   559.3    .045       0   574.3      .1       0
Bank Sta=559.3,574.3
XS Rating Curve= 0 ,0
Exp/Cntr=0.3,0.1

Type RM Length L Ch R = 1 ,20493.9 ,357.4,343.4,331.3
XS GIS Cut Line= 3
     1890996.704      226527.352       1890882.8      227207.701
     1890955.259      227564.937
#Sta/Elev= 30
       0 1924.68      70 1877.34      80 1873.01     160 1846.04   239.9 1841.39
   259.9 1835.86   279.9 1824.43   289.9 1824.18   369.9 1772.66   379.9 1772.48
   409.9 1752.78   419.9 1748.01   489.9 1741.76   529.9 1717.19   542.2 1712.69
   549.9 1711.69   557.2 1711.93   649.8 1719.06   689.8 1719.67   699.7 1722.59
   758.8 1760.58   768.6  1762.2   788.3 1774.71   817.9 1783.54   857.3 1814.77
   867.2 1816.21   916.4 1853.11   955.8 1880.04   975.5 1886.55  1054.3 1934.81
#Mann= 3 , 0 , 0
       0      .1       0   542.2    .045       0   557.2      .1       0
Bank Sta=542.2,557.2
XS Rating Curve= 0 ,0
Exp/Cntr=0.3,0.1

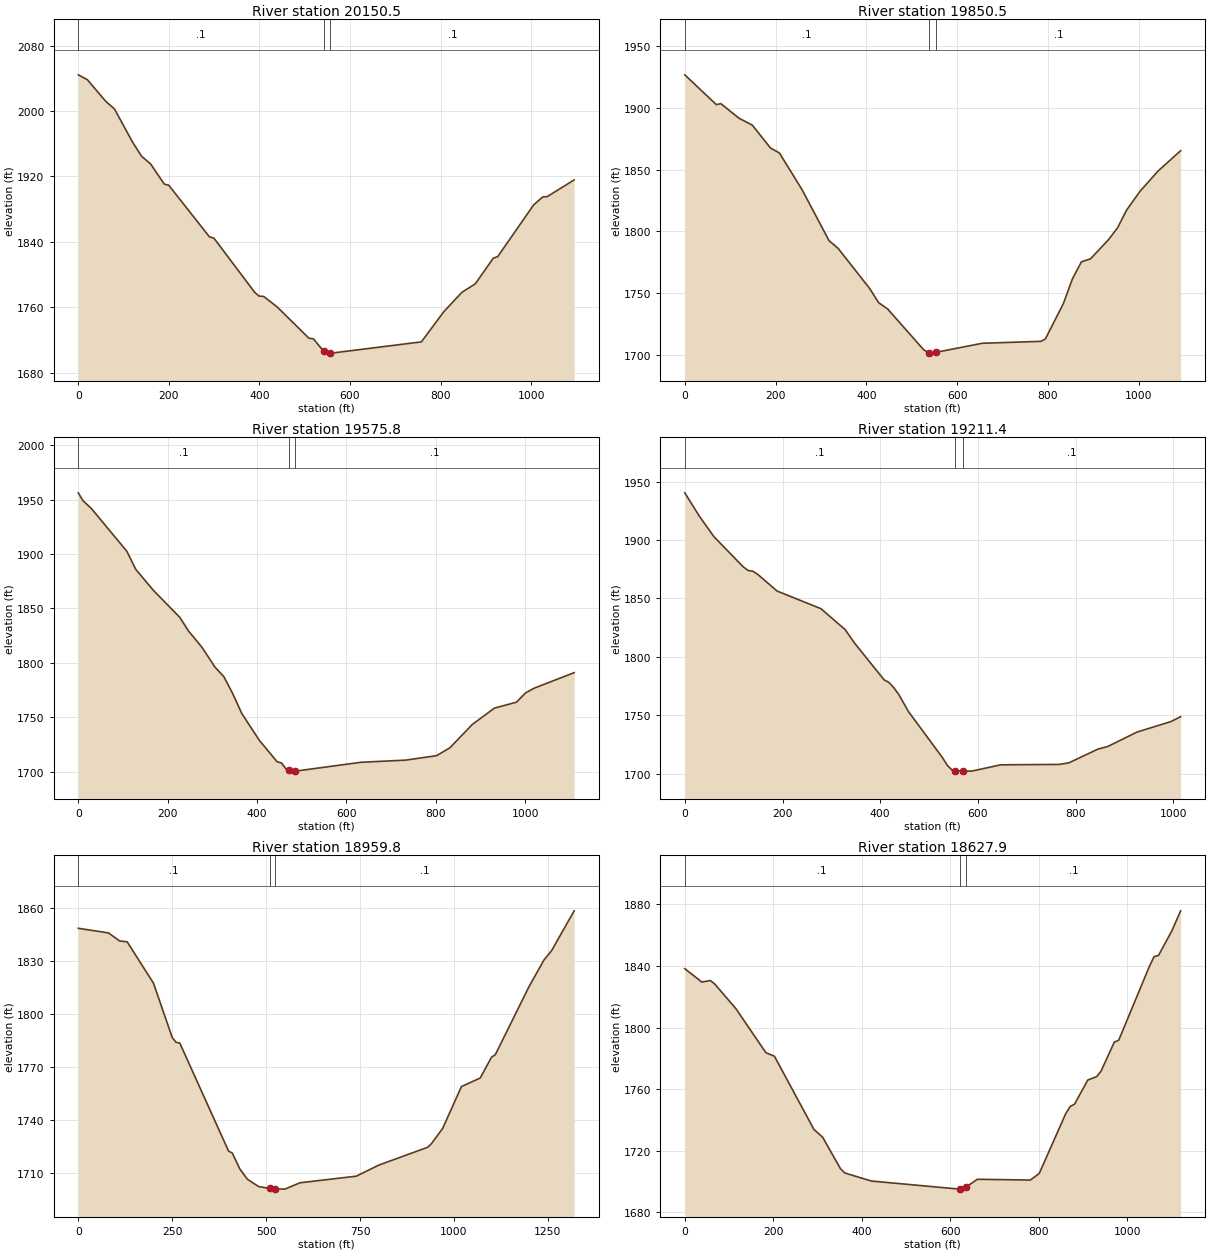
Type RM Length L Ch R = 1 ,20150.5 ,304.7,300,293.6
XS GIS Cut Line= 3
      1890347.38      226623.152     1890585.163      227118.131
     1890778.113      227628.789
#Sta/Elev= 30
       0 2044.38      20 2038.38    59.9 2012.35    79.9 2002.54   119.8 1961.96
   139.8 1944.68   159.8 1935.22   189.7 1910.72   199.7 1909.26   289.5 1846.17
   299.5  1844.5   389.4 1778.29   399.4 1773.54   409.4 1773.19   439.3 1760.25
   509.2 1722.08   519.2 1721.27   541.6 1706.26   556.6 1703.83   559.1 1703.81
   757.6 1717.58   807.2 1754.57   846.9 1778.15   876.7 1788.61   916.4 1820.02
   926.3 1821.98  1005.7 1885.34  1025.6 1894.91  1035.5 1895.35    1095  1915.8
#Mann= 3 , 0 , 0
       0      .1       0   541.6    .045       0   556.6      .1       0
Bank Sta=541.6,556.6
XS Rating Curve= 0 ,0
Exp/Cntr=0.3,0.1

Type RM Length L Ch R = 1 ,19850.5 ,277.2,274.6,271.8
XS GIS Cut Line= 3
      1889989.94      226817.592     1890321.233      227251.741
     1890648.356      227689.292
#Sta/Elev= 30
       0 1926.86    69.5 1902.69    79.4 1903.51   119.2 1891.76   148.9 1886.02
   188.7 1867.59   208.5  1863.5   258.2 1833.88   317.7 1792.52   337.6 1786.26
   407.1 1753.78     427 1742.21   446.8 1737.13   526.2 1704.03   538.6 1701.38
   546.1 1701.28   553.6 1701.95   655.4 1709.27   784.5 1710.83   794.4 1712.76
   834.2 1741.54     854 1761.45   873.9 1775.32   893.8 1777.67   933.5 1793.24
   953.4 1802.79   973.2 1817.13    1003 1832.48  1042.8 1848.92  1092.4 1865.35
#Mann= 3 , 0 , 0
       0      .1       0   538.6    .045       0   553.6      .1       0
Bank Sta=538.6,553.6
XS Rating Curve= 0 ,0
Exp/Cntr=0.3,0.1

Type RM Length L Ch R = 1 ,19575.8 ,365.6,364.4,363.2
XS GIS Cut Line= 3
     1889762.226      227026.556     1889977.916      227257.411
     1890491.863      227862.352
#Sta/Elev= 30
       0 1956.28     9.9 1949.33    29.6 1941.69   108.6 1902.56   128.4 1886.04
   167.8 1866.75   227.1 1841.82   246.8 1829.21   276.4 1814.47   306.1 1795.99
   325.9 1787.22   345.7 1771.61   365.6 1753.65   405.2 1728.75   444.9 1709.12
   454.8 1707.99   464.8 1702.49   470.7  1701.4   484.6  1700.5   485.7  1700.5
   633.4 1708.66   732.7  1710.6   802.1 1714.75   831.9 1722.05   881.5  1743.3
   931.1 1758.37   980.7  1763.9  1000.6 1772.26  1020.4 1776.76  1109.7 1791.01
#Mann= 3 , 0 , 0
       0      .1       0   470.7    .045       0   485.7      .1       0
Bank Sta=470.7,485.7
XS Rating Curve= 0 ,0
Exp/Cntr=0.3,0.1

Type RM Length L Ch R = 1 ,19211.4 ,251,251.6,252.2
XS GIS Cut Line= 2
     1889445.217      227255.606     1890186.865      227948.291
#Sta/Elev= 30
       0 1940.33    29.8 1920.37    59.7  1902.8   119.4 1877.09   129.3 1873.94
   139.3 1873.27   149.2 1870.61     189  1856.3   278.6 1841.25   328.3 1823.28
   348.2 1811.39   407.9 1780.38   417.9  1778.1   427.8 1773.62   437.8 1767.96
   457.7 1753.27   527.3 1713.84   537.3  1707.2   547.2  1703.1   553.6 1702.68
   568.6 1702.35     587 1702.27   646.7 1707.66   766.1 1708.01     786 1709.33
   845.7 1721.12   865.6 1723.33   925.3 1735.63   994.9 1744.66  1014.8 1748.82
#Mann= 3 , 0 , 0
       0      .1       0   553.6    .045       0   568.6      .1       0
Bank Sta=553.6,568.6
XS Rating Curve= 0 ,0
Exp/Cntr=0.3,0.1

Type RM Length L Ch R = 1 ,18959.8 ,315.3,331.9,348.6
XS GIS Cut Line= 2
     1889304.279      227444.724     1890245.843      228369.559
#Sta/Elev= 30
       0 1848.35      80 1845.76     110 1841.19     130 1840.69     200 1817.29
     250 1786.47     260 1783.78     270 1783.38   399.9 1722.16   409.9 1721.03
   429.9 1712.03   449.9 1706.23   479.9 1702.06   508.9 1700.96   523.9 1700.73
   549.9  1700.6   589.9 1704.19   739.9 1707.94   799.9 1714.22   929.9 1724.31
   939.8 1726.32   969.8 1734.98  1019.8 1758.71  1069.8 1763.55  1099.8 1775.34
  1109.8 1776.71  1199.8 1815.38  1239.8  1830.5  1259.8 1835.71  1319.8 1858.25
#Mann= 3 , 0 , 0
       0      .1       0   508.9    .045       0   523.9      .1       0
Bank Sta=508.9,523.9
XS Rating Curve= 0 ,0
Exp/Cntr=0.3,0.1

Type RM Length L Ch R = 1 ,18627.9 ,350.4,352.2,354
XS GIS Cut Line= 3
     1889292.653      227495.849     1889452.173      227650.033
     1889535.303      228545.088
#Sta/Elev= 30
       0 1838.26    38.6 1829.59    57.9 1830.56    67.5 1828.38   115.8 1812.19
   183.3 1783.69   202.6 1781.39   291.8 1733.87   311.8 1728.66   351.7 1708.38
   361.7 1705.52   421.6 1700.28   621.2 1695.02   636.2 1696.44   661.3 1701.42
   781.2 1700.92   801.2 1705.21   861.1 1744.08   871.1 1748.71     881 1750.24
     911 1765.93     931 1768.11     941 1771.73   970.9 1790.54   980.9 1791.81
  1050.8 1840.16  1060.8  1846.1  1070.8 1846.85  1100.8 1862.78  1120.8 1875.87
#Mann= 3 , 0 , 0
       0      .1       0   621.2    .045       0   636.2      .1       0
Bank Sta=621.2,636.2
XS Rating Curve= 0 ,0
Exp/Cntr=0.3,0.1

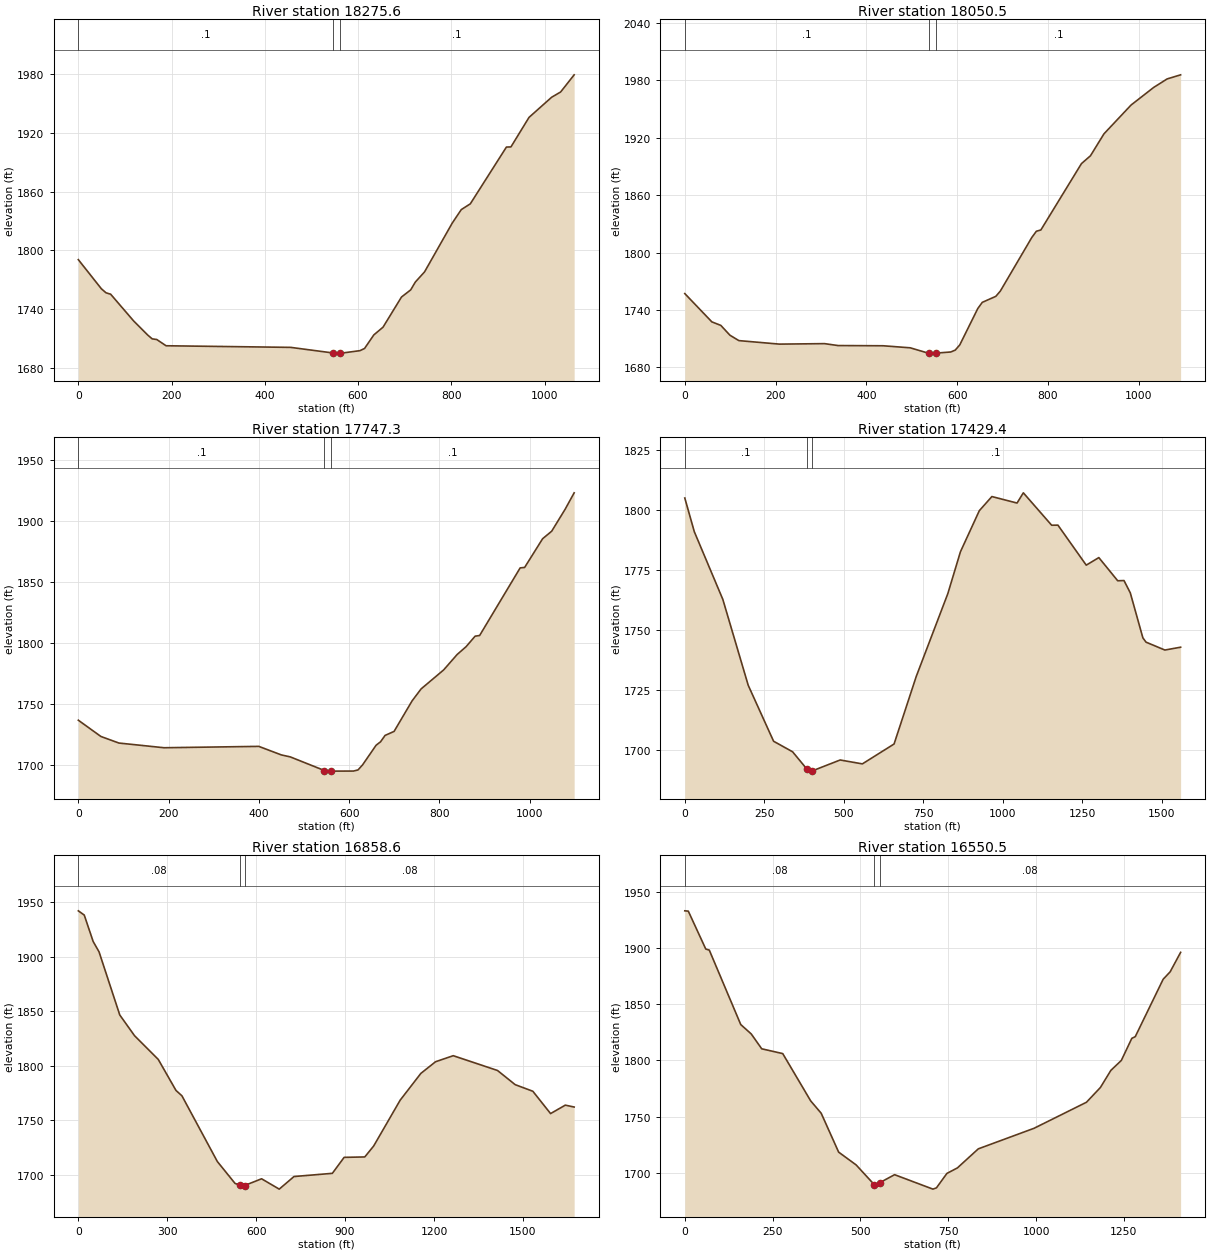
Type RM Length L Ch R = 1 ,18275.6 ,232.7,225.2,217.7
XS GIS Cut Line= 3
     1889144.366      227556.511      1889148.86      228358.606
     1889189.301      228616.984
#Sta/Elev= 30
       0 1790.54    49.5 1760.74    59.4 1756.65    69.3 1755.24   118.8 1727.81
   148.5 1713.62   158.4 1709.59   168.3 1708.89   188.2 1702.53   455.5 1700.88
     547 1695.12     562 1695.01   564.4    1695   604.1 1697.52     614 1699.76
   633.8 1713.58   653.6 1721.51   693.2 1752.32     713 1759.67   722.9 1767.65
   742.7 1778.04   802.1 1827.95   821.5 1841.71   840.8 1847.57   918.3 1905.62
     928 1905.77   966.8 1935.95  1015.2  1956.5  1034.6 1961.92  1063.6 1979.45
#Mann= 3 , 0 , 0
       0      .1       0     547    .045       0     562      .1       0
Bank Sta=547,562
XS Rating Curve= 0 ,0
Exp/Cntr=0.3,0.1

Type RM Length L Ch R = 1 ,18050.5 ,302.2,303,303.8
XS GIS Cut Line= 3
     1888748.055      227644.919     1888928.744      228160.155
     1889109.432       228675.39
#Sta/Elev= 30
       0 1757.19    59.6 1727.64    79.4 1723.96    99.3 1713.75   119.1 1708.07
   208.5 1704.41   307.8 1704.91   337.5 1702.91   436.8 1702.68   496.4 1700.56
   536.1    1695   538.5    1695   553.5 1695.03   585.7 1696.19   595.6 1698.15
   605.6  1703.6   645.3 1741.59   655.2 1748.04     685 1754.32   694.9 1759.79
   764.4 1815.91   774.3 1822.31   784.2 1823.64   873.6 1892.96   893.4 1901.11
   923.2 1924.06   982.8  1954.1  1032.4 1972.44  1062.2 1981.38    1092 1985.69
#Mann= 3 , 0 , 0
       0      .1       0   538.5    .045       0   553.5      .1       0
Bank Sta=538.5,553.5
XS Rating Curve= 0 ,0
Exp/Cntr=0.3,0.1

Type RM Length L Ch R = 1 ,17747.3 ,320.5,318,315.5
XS GIS Cut Line= 3
     1888481.351      227738.491     1888674.792      228358.606
       1888871.3      228762.163
#Sta/Elev= 30
       0 1736.76      50 1723.42    89.9 1718.03   189.9 1714.18   399.8  1715.3
   449.7  1708.3   469.7 1706.65   545.1 1695.51   559.6    1695   560.1    1695
   609.6 1695.06   619.6 1695.98   629.6 1700.08   659.6 1716.22   669.5 1719.05
   679.5 1724.27   699.5 1727.59   739.4 1752.63   759.3 1762.41   809.2 1777.97
   839.1 1790.62     859 1797.07     879 1805.68     889 1806.23   978.8 1861.68
   988.7 1862.06  1028.6 1885.63  1048.6 1891.76  1078.5 1909.83  1098.4 1923.25
#Mann= 3 , 0 , 0
       0      .1       0   545.1    .045       0   560.1      .1       0
Bank Sta=545.1,560.1
XS Rating Curve= 0 ,0
Exp/Cntr=0.3,0.1

Type RM Length L Ch R = 1 ,17429.4 ,564.1,570.8,577.5
XS GIS Cut Line= 3
     1888183.131      227981.033     1888499.545      228702.361
     1888796.118      229414.586
#Sta/Elev= 30
       0 1804.98    29.9 1790.98   119.6 1762.83   199.4 1727.13   279.2 1703.85
     339 1699.46   384.1 1692.25   398.8 1691.42   399.1 1691.43   488.6 1696.05
   558.4 1694.43   658.1  1702.7   727.8 1730.78   827.2 1765.25   866.8 1782.63
   926.2 1799.72   965.7 1805.59  1044.8 1802.89  1064.6 1807.14  1153.6 1793.67
  1173.4  1793.7  1262.4 1777.07    1302 1780.21  1361.4 1770.57  1381.1 1770.67
  1400.9 1765.56  1440.5 1746.84  1450.4 1745.05  1509.7 1741.77  1559.2 1742.95
#Mann= 3 , 0 , 0
       0      .1       0   384.1    .045       0   399.1      .1       0
Bank Sta=384.1,399.1
XS Rating Curve= 0 ,0
Exp/Cntr=0.3,0.1

Type RM Length L Ch R = 1 ,16858.6 ,298.6,308,318.3
XS GIS Cut Line= 4
     1887771.008      228007.967     1887798.554      228356.359
     1887866.697      228929.464     1888382.713      229468.508
#Sta/Elev= 30
       0 1942.18      20 1938.28    49.9  1914.1    69.9  1904.5   139.8 1846.55
   189.7 1827.48   269.6 1805.76   329.5 1777.22   349.5 1772.31   468.9 1711.99
   528.6 1691.88   545.9 1690.14   560.9 1689.92   618.2  1696.1   677.8  1686.6
   727.6 1698.16     857  1701.1   896.8 1715.78   966.4 1716.15   996.3 1726.15
  1085.8 1768.28  1155.5 1792.85  1205.2 1803.59  1264.9 1809.14  1414.2 1795.56
  1473.8 1782.55  1533.5 1776.47  1593.2 1755.97    1643 1763.73  1672.8 1761.99
#Mann= 3 , 0 , 0
       0     .08       0   545.9    .045       0   560.9     .08       0
Bank Sta=545.9,560.9
XS Rating Curve= 0 ,0
Exp/Cntr=0.3,0.1

Type RM Length L Ch R = 1 ,16550.5 ,318.7,324.3,329
XS GIS Cut Line= 3
     1887683.269       227997.13     1887521.584      228520.259
     1887236.863      229335.949
#Sta/Elev= 30
       0 1933.04      10 1932.76    59.7 1899.04    69.7 1898.11   159.3 1831.86
   189.2 1823.47     219 1810.27   278.8 1806.02   358.4 1763.93   388.3 1752.94
     438 1718.33   487.8 1706.95     540 1689.21     555 1691.13   597.2 1698.27
   706.4 1685.42   716.4 1686.56   746.2 1699.41     776 1704.29   835.5 1721.25
   994.4 1739.57  1143.4 1762.71  1183.1 1775.83  1212.9 1791.07  1242.7 1799.92
  1272.5 1819.54  1282.4 1821.11  1361.8 1872.16  1381.7 1878.78  1411.5 1896.09
#Mann= 3 , 0 , 0
       0     .08       0     540    .045       0     555     .08       0
Bank Sta=540,555
XS Rating Curve= 0 ,0
Exp/Cntr=0.3,0.1