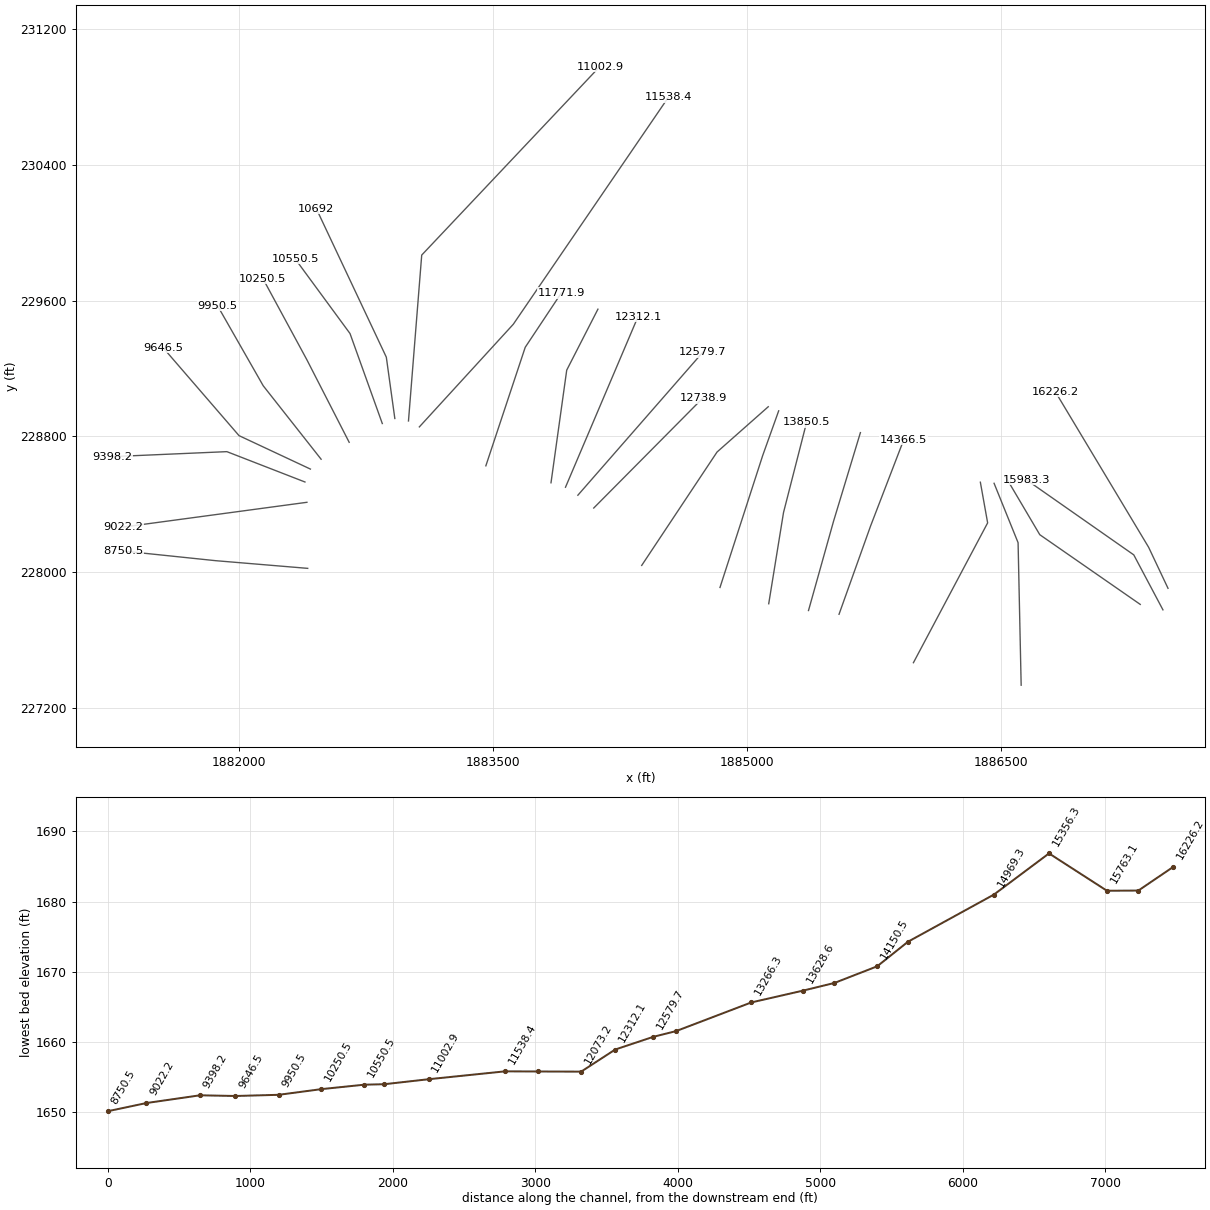
HEC-RAS study StnclCrk.prj: StnclCrk

--- StnclCrk.g01 (geometry) --- (continued)

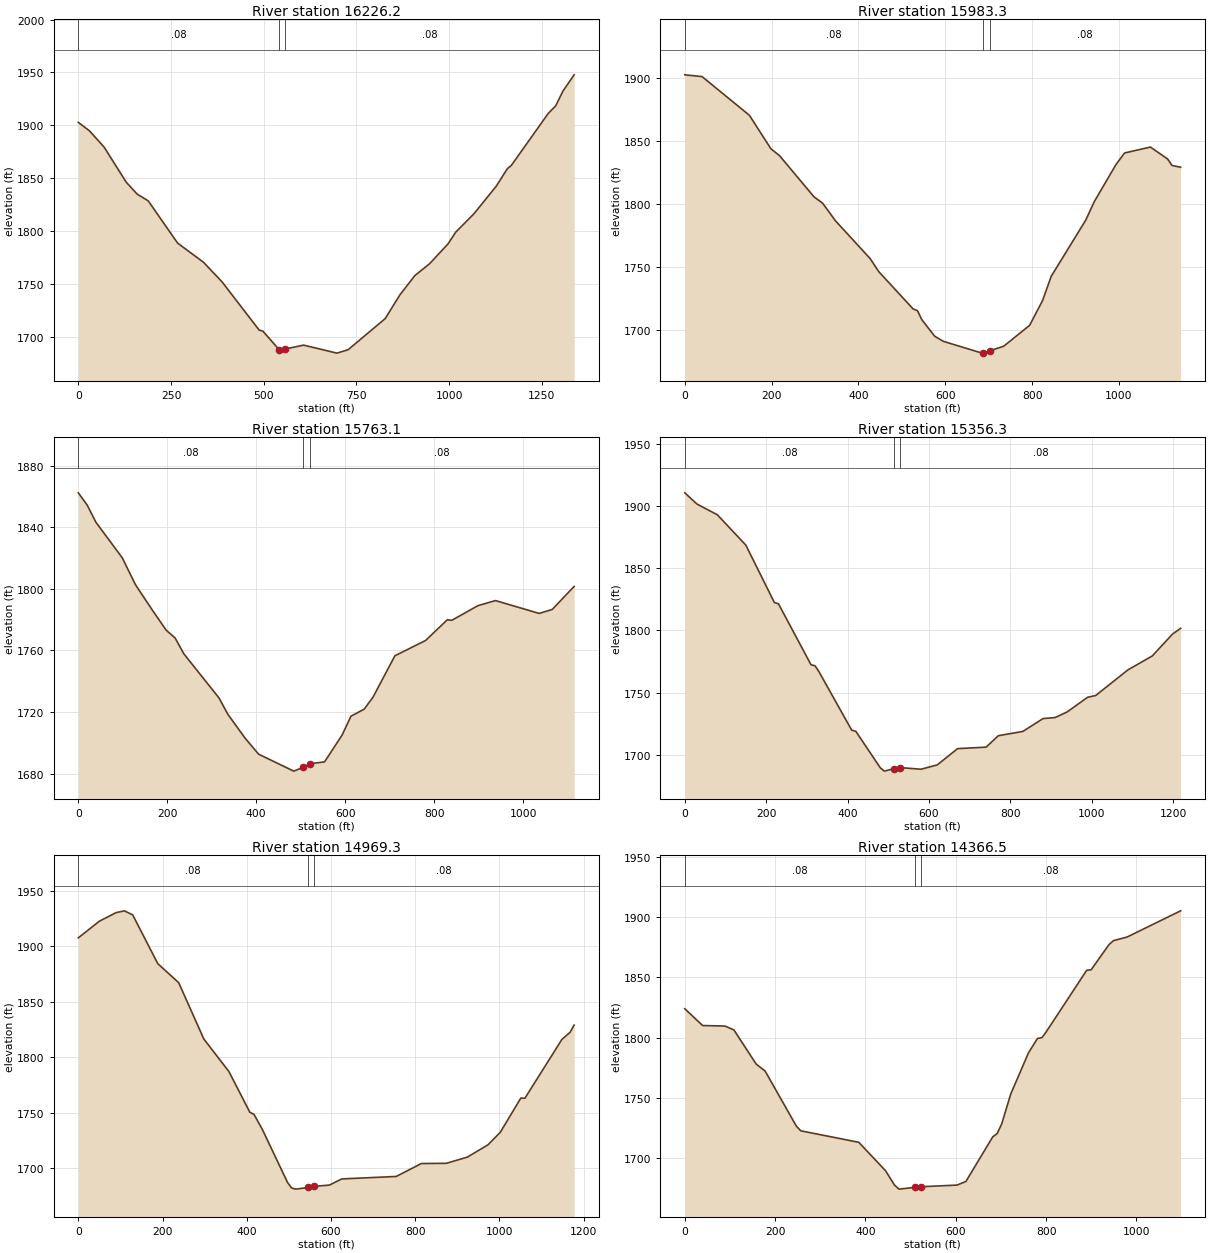
Type RM Length L Ch R = 1 ,16226.2 ,233.4,242.8,252.2
XS GIS Cut Line= 3
     1887486.109      227903.187     1887371.669      228145.164
     1886821.211      229061.844
#Sta/Elev= 30
       0 1902.85    29.7    1895    69.4 1879.59   128.9  1846.5   158.6 1835.12
   188.4 1828.79   267.7 1788.84   337.6  1770.7   387.6 1752.22   487.5 1706.71
   497.5 1705.71   541.7  1688.1   556.7 1688.72   607.4 1692.48   697.4 1684.92
   727.4 1688.13   827.3 1717.48   867.3 1740.06   907.2 1758.11   947.2 1769.38
   997.2 1788.27  1017.2 1799.02  1067.1  1816.7  1127.1 1842.72    1157 1859.27
    1167 1861.97    1267 1911.32    1287 1918.44    1307 1932.63  1336.9 1947.78
#Mann= 3 , 0 , 0
       0     .08       0   541.7    .045       0   556.7     .08       0
Bank Sta=541.7,556.7
XS Rating Curve= 0 ,0
Exp/Cntr=0.3,0.1

Type RM Length L Ch R = 1 ,15983.3 ,220.2,220.3,220.4
XS GIS Cut Line= 3
     1887456.205      227776.065     1887284.045      228100.228
     1886648.625      228544.192
#Sta/Elev= 30
       0 1902.19    39.7  1900.8   148.8 1870.13   198.4 1843.56   218.2 1838.14
   297.6 1805.48   317.4 1800.48   347.2 1786.44   426.7 1756.64   446.6 1746.26
     526  1716.6     536 1715.22   545.9 1708.16   575.7 1694.99   595.6 1690.92
     685 1681.58     688 1681.74     703  1683.5   734.7 1687.06   794.4 1703.63
   824.2 1723.28   844.1 1742.47   923.6 1786.99   943.4 1801.73   993.1 1830.94
    1013 1840.24  1072.6 1844.94  1112.4 1835.42  1122.3 1830.37  1142.2 1828.93
#Mann= 3 , 0 , 0
       0     .08       0     688    .045       0     703     .08       0
Bank Sta=688,703
XS Rating Curve= 0 ,0
Exp/Cntr=0.3,0.1

Type RM Length L Ch R = 1 ,15763.1 ,428.1,406.7,385.3
XS GIS Cut Line= 3
      1887322.24      227808.149     1886729.094      228219.307
     1886529.145      228557.713
#Sta/Elev= 30
       0 1862.51    19.8  1854.6    39.6 1843.35    98.9  1820.2   128.5 1802.75
   168.1 1785.52   197.7 1773.16   217.5 1768.16   237.3 1757.81   316.4 1729.09
   336.1 1718.54   375.7  1702.7   405.4 1692.56   484.4 1681.55   505.8 1684.07
   520.8 1686.35   553.6 1687.57   593.2 1705.07     613 1717.28   642.6 1721.82
   662.4 1729.56   711.8 1756.56   780.7 1766.49   829.8 1780.01   839.6 1779.59
   898.6 1789.15   937.9 1792.45  1036.2 1784.09  1065.6 1786.69  1114.8 1801.68
#Mann= 3 , 0 , 0
       0     .08       0   505.8    .045       0   520.8     .08       0
Bank Sta=505.8,520.8
XS Rating Curve= 0 ,0
Exp/Cntr=0.3,0.1

Type RM Length L Ch R = 1 ,15356.3 ,398.6,387.1,375.6
XS GIS Cut Line= 3
     1886619.201      227331.642     1886601.028      228172.125
     1886459.316       228522.51
#Sta/Elev= 30
       0 1910.53      30  1901.5    80.1 1892.87   150.1 1868.46   220.2 1822.33
   230.2 1821.36   310.2 1772.36   320.3 1771.51   330.3 1766.46   410.3 1719.76
   420.3 1718.89   480.4 1689.59   490.4 1686.87   514.4 1688.92   529.4 1689.72
   580.5 1688.38   620.5 1691.89   670.5 1704.95   740.6 1706.15   770.6 1715.34
   830.7 1718.76   880.5  1729.1   910.3 1729.95   940.1 1734.52   989.9 1746.21
  1009.8 1747.62  1089.3 1768.28    1149 1779.44  1198.7 1797.03  1218.6 1801.63
#Mann= 3 , 0 , 0
       0     .08       0   514.4    .045       0   529.4     .08       0
Bank Sta=514.4,529.4
XS Rating Curve= 0 ,0
Exp/Cntr=0.3,0.1

Type RM Length L Ch R = 1 ,14969.3 ,599.4,602.6,605.9
XS GIS Cut Line= 3
     1885983.168      227464.394     1886421.287      228288.957
     1886378.359      228528.866
#Sta/Elev= 30
       0 1907.66    49.7 1922.64    89.4 1930.37   109.3 1932.04   129.1 1928.38
   188.7 1884.36   238.4  1867.2     298 1816.43   357.6 1787.07   407.3 1750.35
   417.2 1748.42   437.1 1734.76   496.7 1687.07   506.6 1681.99   516.5    1681
   545.6 1682.48   560.6 1683.56     596 1684.62   625.8 1690.21   754.9 1692.42
   814.5 1704.09   874.1  1704.3   923.8 1709.87   972.7 1720.95    1002 1732.26
  1050.7  1763.1  1060.5 1762.98  1148.2    1816  1167.7 1822.47  1177.4 1828.96
#Mann= 3 , 0 , 0
       0     .08       0   545.6    .045       0   560.6     .08       0
Bank Sta=545.6,560.6
XS Rating Curve= 0 ,0
Exp/Cntr=0.3,0.1

Type RM Length L Ch R = 1 ,14366.5 ,214.5,216.1,217.2
XS GIS Cut Line= 3
      1885544.03      227750.036     1885730.348      228270.911
     1885926.036      228779.278
#Sta/Elev= 30
       0 1823.96    39.5 1810.04    88.9  1809.6   108.7 1806.41   158.1 1778.03
   177.8 1772.28     247 1726.59   256.8 1722.68   385.3 1713.14   444.5 1689.57
   464.3 1677.67   474.2 1674.29   508.7 1675.71   523.7 1676.29   602.7 1677.64
   622.5 1680.66     682 1717.74   691.8 1720.46   701.8 1728.48   721.6 1753.08
   761.2 1787.52     781 1799.34   790.9 1800.03   800.8 1805.08   889.9 1855.87
   899.8 1856.31   939.5  1877.3   949.4  1880.5   979.1 1883.41  1097.9 1905.21
#Mann= 3 , 0 , 0
       0     .08       0   508.7    .045       0   523.7     .08       0
Bank Sta=508.7,523.7
XS Rating Curve= 0 ,0
Exp/Cntr=0.3,0.1

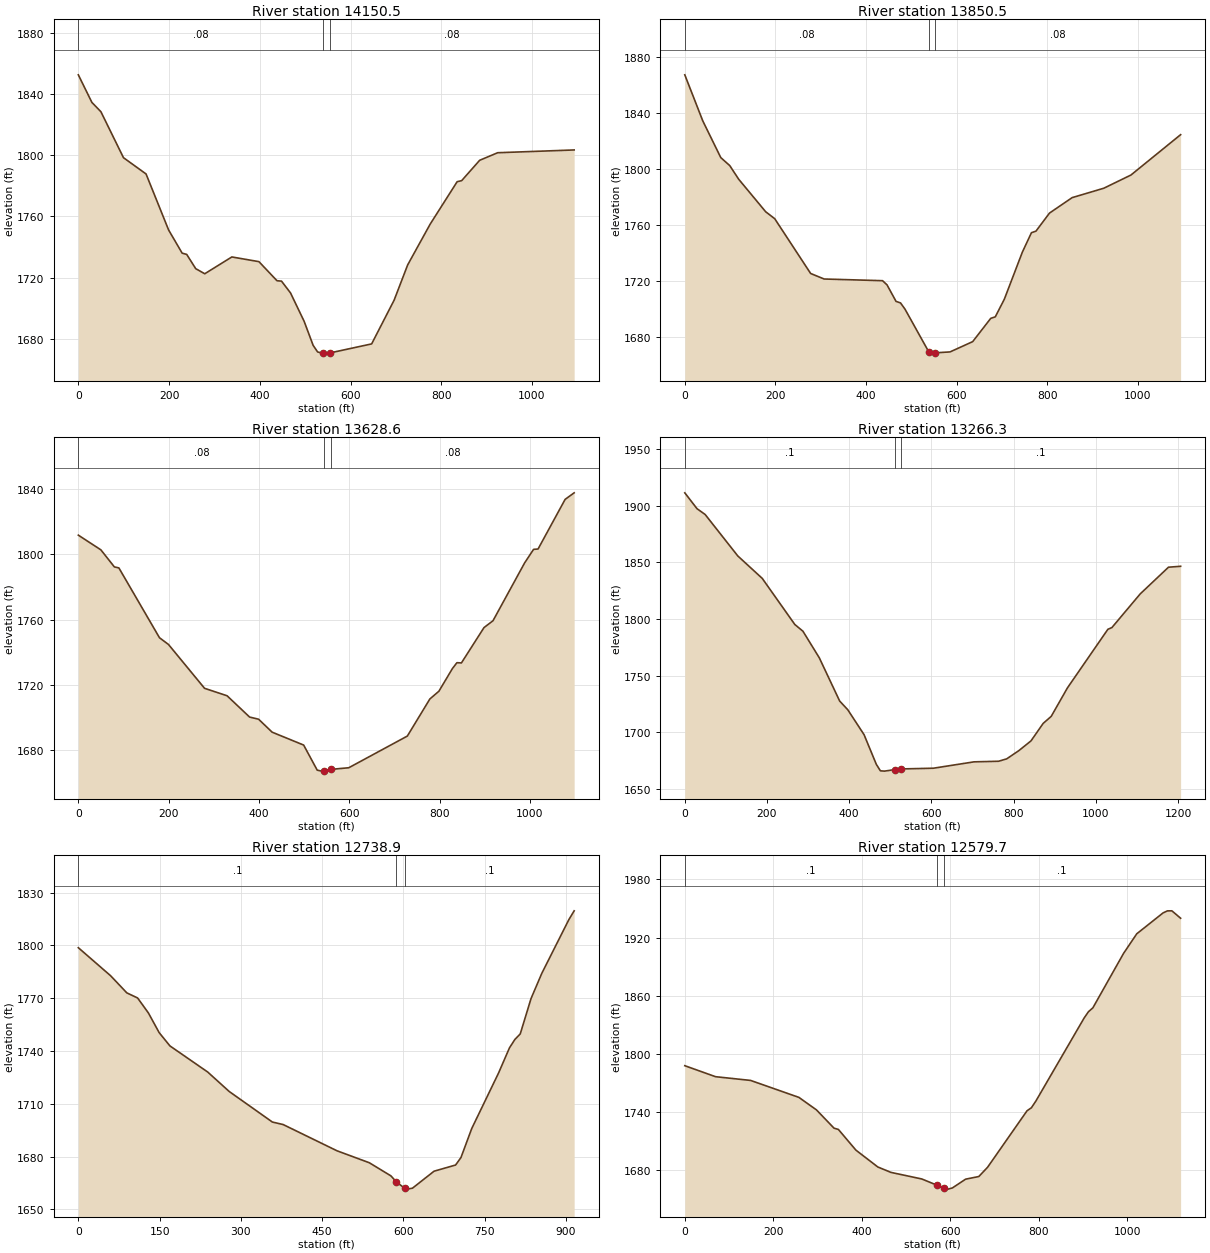
Type RM Length L Ch R = 1 ,14150.5 ,297.5,300,301
XS GIS Cut Line= 3
     1885363.785      227772.091     1885511.771      228299.135
     1885670.152      228821.251
#Sta/Elev= 30
       0 1852.49    29.9 1834.48    49.8 1828.39    99.5  1798.4   149.3 1787.76
   199.1 1751.14   228.9 1736.05   238.9 1735.25   258.8 1725.93   278.7 1722.61
   338.4 1733.58   398.1 1730.52   437.9 1718.07   447.9 1717.79   467.8 1710.07
   497.7 1691.61   517.6 1675.88   527.5 1671.56   537.5 1670.79   539.9 1670.82
   554.9 1670.93   646.6 1676.82   696.2  1705.4     726 1728.39   775.6 1755.01
   835.1 1782.72     845 1783.39   884.7 1796.69   924.4 1801.63    1093 1803.44
#Mann= 3 , 0 , 0
       0     .08       0   539.9    .045       0   554.9     .08       0
Bank Sta=539.9,554.9
XS Rating Curve= 0 ,0
Exp/Cntr=0.3,0.1

Type RM Length L Ch R = 1 ,13850.5 ,225.3,221.8,220.4
XS GIS Cut Line= 3
     1885128.891         227812.     1885216.341      228350.471
     1885352.549      228881.982
#Sta/Elev= 30
       0 1867.01    39.7 1834.14    79.4 1807.96    99.2 1802.24     119 1792.49
   178.5  1769.3   198.4 1764.37   277.7 1725.26   307.5 1721.31   436.4 1720.11
   446.3 1717.11   466.2 1705.34   476.1 1704.24     486 1699.78     538 1669.57
   545.5 1668.42     553 1668.64   585.4 1669.29   635.3 1676.62   675.2 1693.24
   685.2 1694.32   705.1 1706.85     745 1740.53     765 1754.35     775 1755.48
   804.9 1768.37   854.8 1779.38   924.6 1786.08   984.5 1795.49  1094.2  1824.3
#Mann= 3 , 0 , 0
       0     .08       0     538    .045       0     553     .08       0
Bank Sta=538,553
XS Rating Curve= 0 ,0
Exp/Cntr=0.3,0.1

Type RM Length L Ch R = 1 ,13628.6 ,368.7,362.3,356
XS GIS Cut Line= 3
     1884841.201      227908.036     1885093.449      228686.634
     1885187.722      228949.785
#Sta/Elev= 30
       0 1811.82    49.9 1802.83    79.8 1792.38    89.8 1791.76   179.7 1749.01
   199.6 1744.89   279.5 1718.04   329.4 1713.47   379.3 1700.42   399.2 1699.11
   429.2 1691.17     499 1683.28     529 1667.91     539 1667.32   545.1 1667.64
   560.1 1668.41   598.9 1669.39   728.6 1688.79   778.5 1711.51   798.5 1716.25
   828.4 1730.13   838.4 1733.71   848.4 1733.59   898.3  1755.2   918.3 1759.42
   988.2 1794.77  1008.1 1803.12  1018.1 1803.34    1078 1833.73    1098 1837.74
#Mann= 3 , 0 , 0
       0     .08       0   545.1    .045       0   560.1     .08       0
Bank Sta=545.1,560.1
XS Rating Curve= 0 ,0
Exp/Cntr=0.3,0.1

Type RM Length L Ch R = 1 ,13266.3 ,529.1,527.4,524.1
XS GIS Cut Line= 3
      1884379.12      228038.167     1884823.837      228706.855
     1885126.139      228973.933
#Sta/Elev= 30
       0 1911.49    29.7 1897.49    49.6 1892.32   128.9 1855.75   188.4 1835.92
   267.7 1795.18   287.5 1789.21   327.2 1765.78   376.8 1727.57   396.6 1719.84
   436.2 1697.83     466 1671.64   475.9 1665.91   485.8 1665.64   511.3 1666.99
   526.3 1667.57   604.8 1668.21   703.9 1673.84   763.4 1674.36   783.2 1676.47
   812.9 1683.77   842.4 1692.38   871.9 1707.78   891.6 1714.03     931 1739.17
  1029.4 1790.93  1039.2 1792.46  1108.1 1822.21  1176.9 1845.79  1206.4  1846.6
#Mann= 3 , 0 , 0
       0      .1       0   511.3    .045       0   526.3      .1       0
Bank Sta=511.3,526.3
XS Rating Curve= 0 ,0
Exp/Cntr=0.3,0.1

Type RM Length L Ch R = 1 ,12738.9 ,157.7,159.2,160.6
XS GIS Cut Line= 2
     1884095.886       228376.58     1884740.707      229025.895
#Sta/Elev= 30
       0 1798.71    59.7 1782.75    89.5 1773.05   109.4 1770.15   129.3 1761.66
   149.2 1750.45   169.1 1742.91   238.7  1728.1   278.5 1717.02   358.1 1699.68
     378 1698.25   477.4 1683.34   537.1 1676.54   576.9  1669.1   587.1 1665.64
   602.1  1662.1   606.8 1661.56   616.7  1662.1   656.5 1671.74   696.3 1675.26
   706.2 1679.51   726.1    1696   775.8 1727.66   795.7 1741.81   805.7 1746.58
   815.6 1749.74   835.5  1769.8   855.4 1784.16   905.2 1814.59   915.1 1819.66
#Mann= 3 , 0 , 0
       0      .1       0   587.1    .045       0   602.1      .1       0
Bank Sta=587.1,602.1
XS Rating Curve= 0 ,0
Exp/Cntr=0.3,0.1

Type RM Length L Ch R = 1 ,12579.7 ,260.3,267.5,274.7
XS GIS Cut Line= 2
     1884002.242      228452.183     1884740.348      229296.165
#Sta/Elev= 30
       0    1788    69.5 1776.67   148.8 1772.82     258 1755.34   297.7 1742.46
   337.4 1723.61   347.3 1722.29     387 1700.93   436.6 1683.55   466.3 1677.99
   535.8 1671.24     570 1664.86     585 1661.45   595.3 1660.75   605.2    1662
     635 1671.01   664.8 1673.73   684.6 1683.24   773.9 1741.52   783.8 1744.65
   793.8 1751.49   902.9 1837.08   912.8 1843.67   922.8 1847.68   992.2 1903.81
    1022 1923.98  1081.5 1945.52  1091.4 1947.63  1101.4 1947.67  1121.2 1940.04
#Mann= 3 , 0 , 0
       0      .1       0     570    .045       0     585      .1       0
Bank Sta=570,585
XS Rating Curve= 0 ,0
Exp/Cntr=0.3,0.1

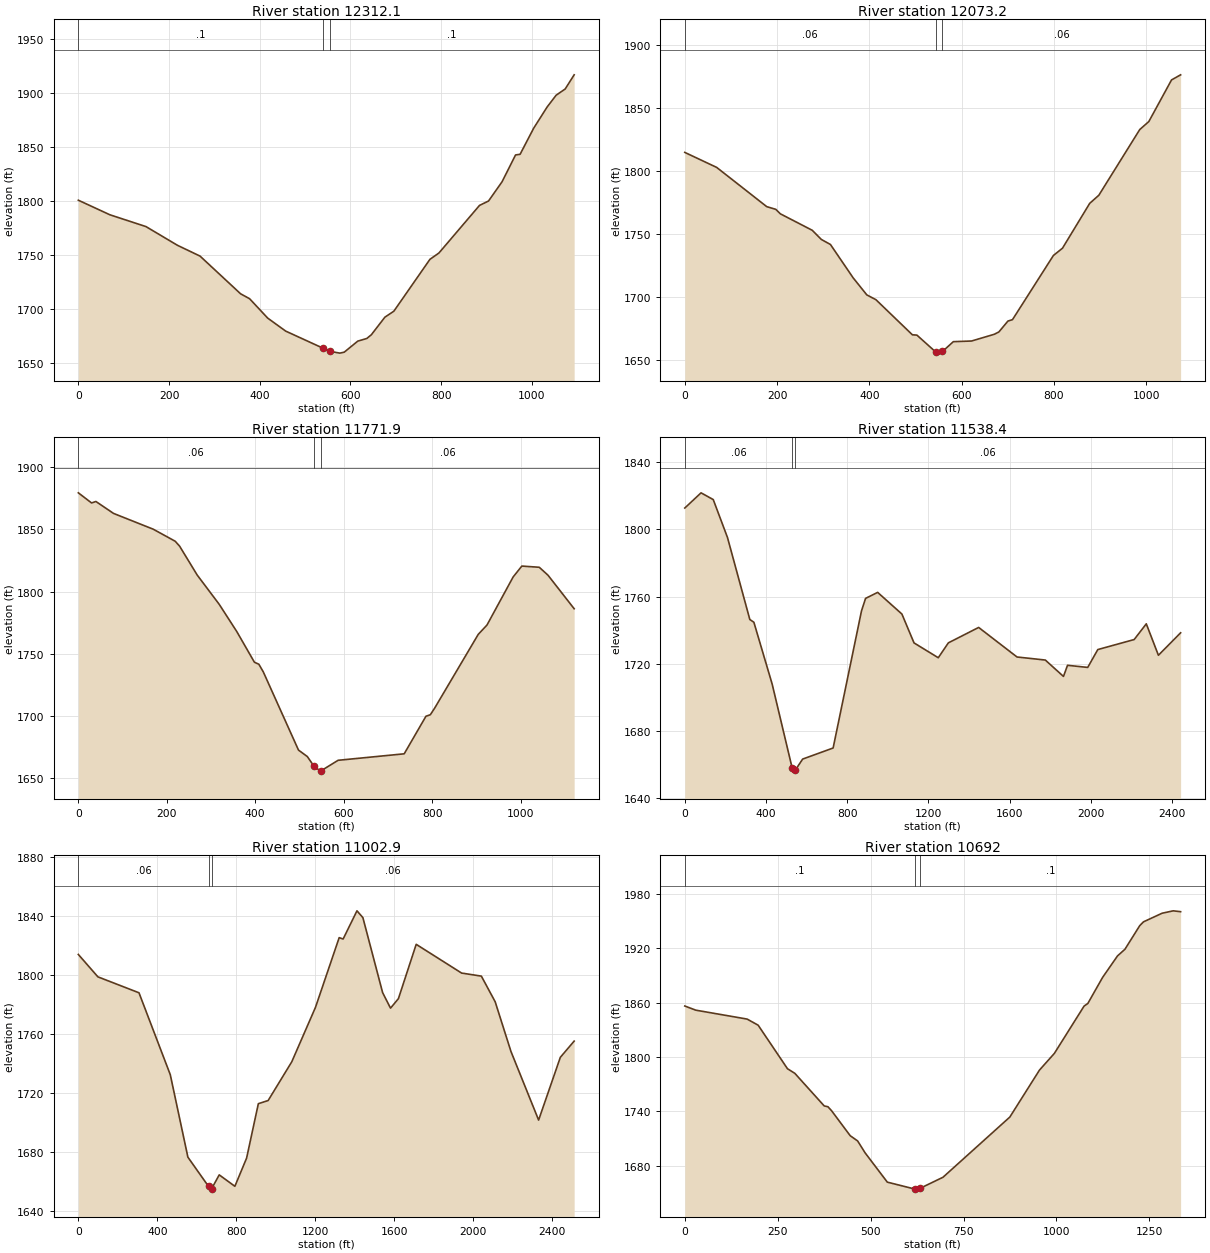
Type RM Length L Ch R = 1 ,12312.1 ,233.1,239.1,245.1
XS GIS Cut Line= 2
     1883929.168      228499.244     1884357.297      229505.279
#Sta/Elev= 30
       0 1800.69    69.6 1787.17   149.1 1776.24   218.7 1758.86   268.4 1748.87
   357.8 1713.94   377.7 1709.35   417.5 1691.42   457.2 1679.36   540.1  1663.4
   555.1 1660.59   576.5 1658.94   586.4 1659.85   616.2 1670.07   636.1 1672.53
   646.1 1675.97   675.9 1692.22   695.8 1697.84   775.3 1745.88   795.2 1751.78
   884.6 1795.86   904.5 1799.94   934.3 1817.75   964.1 1842.64   974.1 1843.23
  1003.9 1867.33  1033.7 1887.07  1053.6 1898.02  1073.5 1903.76  1093.3  1916.9
#Mann= 3 , 0 , 0
       0      .1       0   540.1    .045       0   555.1      .1       0
Bank Sta=540.1,555.1
XS Rating Curve= 0 ,0
Exp/Cntr=0.3,0.1

Type RM Length L Ch R = 1 ,12073.2 ,305.1,301,297
XS GIS Cut Line= 3
     1883843.588      228525.455     1883936.365      229189.909
       1884120.6      229549.392
#Sta/Elev= 30
       0 1814.73    69.1 1802.85   177.6 1771.78   197.3 1769.63   207.2 1766.08
   276.2 1753.07     296  1745.8   315.7 1741.82     365 1715.38   394.6 1701.89
   414.4 1698.08   493.3 1670.31   503.2 1670.04   543.6 1656.79   552.5 1655.79
   558.6 1657.09   582.1 1664.86   621.6 1665.38   670.9 1670.72   680.8 1672.54
   700.5 1681.19   710.3 1682.27     799 1733.09   818.7 1738.86   877.8 1774.41
   897.5 1780.79   986.2 1832.82  1005.9 1839.16  1055.1 1872.11  1074.8 1876.15
#Mann= 3 , 0 , 0
       0     .06       0   543.6    .045       0   558.6     .06       0
Bank Sta=543.6,558.6
XS Rating Curve= 0 ,0
Exp/Cntr=0.3,0.1

Type RM Length L Ch R = 1 ,11771.9 ,243,233.5,224
XS GIS Cut Line= 3
     1883459.007      228625.578     1883691.468      229324.715
      1883904.34      229644.655
#Sta/Elev= 30
       0 1879.31    29.9 1871.19    39.8 1872.35    79.6 1862.78   169.3 1850.11
     219 1840.44     229 1836.48   268.8 1813.27   318.6 1789.75   358.4 1767.83
   398.2 1743.24   408.2 1741.65   418.2 1735.53   497.8 1672.72   517.7 1667.53
     533  1659.7   547.6 1655.81     548  1655.9   587.4 1664.51   736.8 1669.71
     786 1699.88   795.9  1701.1   805.7 1706.41   904.3 1765.66     924 1773.13
   983.1 1811.71  1002.8 1820.49  1042.2 1819.52  1061.9 1813.17  1121.1 1786.23
#Mann= 3 , 0 , 0
       0     .06       0     533    .045       0     548     .06       0
Bank Sta=533,548
XS Rating Curve= 0 ,0
Exp/Cntr=0.3,0.1

Type RM Length L Ch R = 1 ,11538.4 ,518.4,535.4,552.4
XS GIS Cut Line= 3
     1883066.416      228855.099     1883620.822      229460.245
     1884536.252      230798.593
#Sta/Elev= 30
       0 1812.81    80.1 1821.88   140.1 1817.85   210.2 1795.24   320.3  1746.3
   340.3 1744.65   430.4 1707.73   528.5 1657.87   540.5 1655.83   543.5 1656.27
   580.5 1663.02   730.6 1669.62   870.4 1751.44   890.4 1758.89     950 1762.48
  1069.4 1749.55  1129.1 1732.33  1248.5 1723.48  1298.2 1732.36  1447.4 1741.56
  1636.4 1723.93  1775.7 1722.11  1865.2 1712.33  1885.1 1718.97  1984.6 1717.71
  2034.3 1728.36  2213.4 1734.34  2273.1 1743.72  2332.8 1724.96  2442.2 1738.36
#Mann= 3 , 0 , 0
       0     .06       0   528.5    .045       0   543.5     .06       0
Bank Sta=528.5,543.5
XS Rating Curve= 0 ,0
Exp/Cntr=0.3,0.1

Type RM Length L Ch R = 1 ,11002.9 ,300.3,310.8,321.6
XS GIS Cut Line= 3
     1883002.191      228890.134     1883080.348      229868.432
     1884131.834      230980.581
#Sta/Elev= 30
       0 1813.72    99.1 1798.54   307.3 1787.74   465.9 1732.22   555.1 1676.36
   659.8 1656.51   674.1 1654.71   674.8 1654.85   713.8 1664.37   793.1 1656.63
   852.5 1675.74     912  1712.6   961.6 1714.74  1081.4    1741  1201.5  1777.9
  1321.5  1825.1  1341.5 1824.17  1411.6 1843.27  1441.6 1838.67  1541.6 1787.84
  1581.6 1777.33  1621.6 1783.77  1711.7 1820.57  1941.7  1801.1  2041.8 1799.03
  2111.8 1781.65  2191.8 1747.96  2331.9  1701.5  2441.9 1744.02  2511.9    1755
#Mann= 3 , 0 , 0
       0     .06       0   659.8    .045       0   674.8     .06       0
Bank Sta=659.8,674.8
XS Rating Curve= 0 ,0
Exp/Cntr=0.3,0.1

Type RM Length L Ch R = 1 ,10692   ,143.7,141.6,145.9
XS GIS Cut Line= 3
      1882921.58      228904.655     1882871.399      229266.299
     1882457.994      230142.537
#Sta/Elev= 30
       0 1856.19    29.6  1851.6   167.8 1841.75   197.4    1835   276.3 1786.92
     296 1781.87   375.1 1745.86   385.1 1744.97   395.1 1740.47     445    1713
     465  1707.2     485 1694.13   544.9  1661.7   618.6 1654.11   624.8    1654
   633.6 1655.01   694.7 1667.12   874.5 1733.58   954.4 1785.51   994.4 1803.91
  1074.3 1856.13  1084.3 1858.96  1124.2 1887.85  1164.2 1911.51  1184.2 1918.86
  1224.1 1944.97  1234.1 1949.12    1284 1958.61    1314 1961.29    1334 1960.32
#Mann= 3 , 0 , 0
       0      .1       0   618.6    .045       0   633.6      .1       0
Bank Sta=618.6,633.6
XS Rating Curve= 0 ,0
Exp/Cntr=0.3,0.1

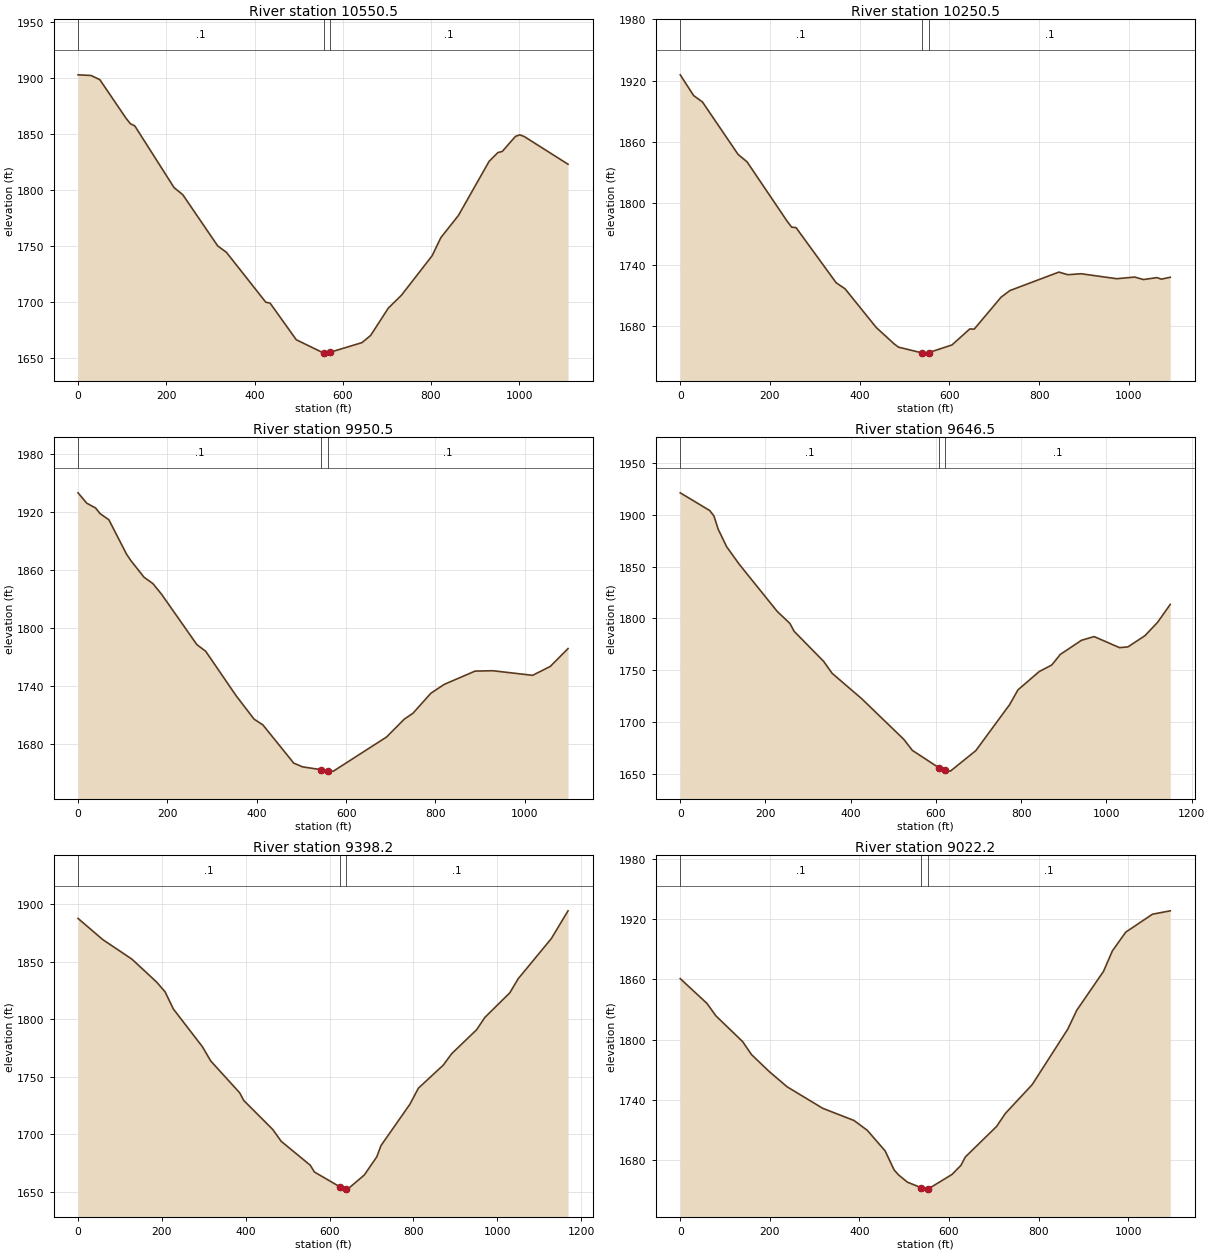
Type RM Length L Ch R = 1 ,10550.5 ,296.8,300,296.9
XS GIS Cut Line= 3
     1882847.627      228874.912     1882657.096      229405.601
     1882333.324      229845.978
#Sta/Elev= 30
       0 1903.07    29.7 1902.48    49.5 1898.68   108.8 1864.18   118.7 1859.29
   128.6 1857.36   217.6 1802.14   237.4 1795.75   316.6 1749.87   336.3 1744.18
   425.4 1699.54   435.3 1698.67   494.6 1665.89   556.4 1654.04   563.9 1653.93
   571.4 1654.73   643.4 1663.32   663.2  1669.8     703 1694.16   732.8 1705.71
   802.4  1741.1   822.2 1757.32     862 1777.16   931.6 1825.64   951.4 1833.46
   961.4  1834.5   991.2 1847.94  1001.1 1849.32  1011.1 1847.85  1110.4 1823.05
#Mann= 3 , 0 , 0
       0      .1       0   556.4    .045       0   571.4      .1       0
Bank Sta=556.4,571.4
XS Rating Curve= 0 ,0
Exp/Cntr=0.3,0.1

Type RM Length L Ch R = 1 ,10250.5 ,295.6,300,300.5
XS GIS Cut Line= 3
     1882652.069       228764.23     1882402.888      229250.019
     1882142.616      229730.188
#Sta/Elev= 30
       0 1925.65    29.8 1905.37    49.6 1899.04     129 1847.71   148.9  1840.5
   238.2 1782.43   248.2 1776.63   258.1 1776.13   347.4 1722.21   367.3 1716.26
   436.8 1678.41   476.5 1662.44   486.4 1659.16   538.5 1653.58     546  1653.3
   553.5 1653.78   605.6  1661.3   645.3 1676.96   655.2 1676.78   714.8 1707.92
   734.6 1714.51   843.9 1732.61   863.7 1730.04   893.5 1730.98     973 1726.12
  1012.7 1727.74  1032.6 1725.32  1062.4  1727.2  1072.3  1725.7  1092.1 1727.55
#Mann= 3 , 0 , 0
       0      .1       0   538.5    .045       0   553.5      .1       0
Bank Sta=538.5,553.5
XS Rating Curve= 0 ,0
Exp/Cntr=0.3,0.1

Type RM Length L Ch R = 1 ,9950.5  ,302.8,303.9,308.3
XS GIS Cut Line= 3
     1882486.372      228664.448     1882144.643      229097.617
     1881874.272      229570.809
#Sta/Elev= 30
       0 1939.72    19.7 1928.97    39.4 1924.07    49.3 1918.27      69 1911.92
   108.4 1876.56   118.2  1869.8   147.8 1852.58   167.5 1846.08   187.2 1834.92
     266 1783.05   285.7 1776.21   354.7 1729.77   394.1 1706.12   413.8 1700.17
   482.8 1660.75   502.5  1656.9   544.2 1653.97   559.2 1652.68   571.6 1652.49
   690.5 1687.68   730.1 1706.09   749.9 1712.33   789.6 1732.82   819.3 1741.95
   888.6 1755.72   928.3 1756.12  1017.4 1751.36  1057.1 1760.58  1096.7 1778.98
#Mann= 3 , 0 , 0
       0      .1       0   544.2    .045       0   559.2      .1       0
Bank Sta=544.2,559.2
XS Rating Curve= 0 ,0
Exp/Cntr=0.3,0.1

Type RM Length L Ch R = 1 ,9646.5  ,227.8,248.3,268.8
XS GIS Cut Line= 3
     1882423.225      228606.276     1882001.901      228803.466
     1881554.352      229321.236
#Sta/Elev= 30
       0 1921.18    69.3 1904.02    79.2 1898.69    89.1 1885.95   108.9 1869.09
   138.6 1852.06   227.6 1806.58   257.3 1794.99   267.2 1787.38   336.5 1758.33
   356.3 1746.83   425.6 1722.34   524.7 1682.95   544.5  1672.4     606  1655.8
     621 1653.19   633.8 1652.32   693.3 1672.05   772.7 1716.54   792.5  1730.9
   842.1 1748.47   871.8 1754.91   891.7 1765.07   941.3  1778.7     971 1782.32
  1030.6 1771.62  1050.4 1772.34  1090.1 1783.12  1119.8 1796.01  1149.6 1813.38
#Mann= 3 , 0 , 0
       0      .1       0     606    .045       0     621      .1       0
Bank Sta=606,621
XS Rating Curve= 0 ,0
Exp/Cntr=0.3,0.1

Type RM Length L Ch R = 1 ,9398.2  ,374.1,376,377.9
XS GIS Cut Line= 3
      1882391.01      228530.154     1881930.004      228709.102
      1881256.03      228679.812
#Sta/Elev= 30
       0 1887.77    59.3 1869.29   128.6 1852.37   187.9 1832.31   207.7 1823.95
   227.5    1809   296.7 1776.25   316.5 1763.92   385.7 1736.16   395.6 1729.44
   464.8  1704.2   484.6 1694.04     554 1673.23     564 1667.31   624.5 1654.49
   639.5 1652.62   643.3 1652.42     683 1664.68   712.8  1680.5   722.7 1690.19
   792.1 1726.39     812 1740.16   871.5 1760.26   891.4 1770.13   950.9 1790.96
   970.7 1801.73  1030.2  1823.1  1050.1 1835.31  1129.4 1870.31  1169.1 1894.38
#Mann= 3 , 0 , 0
       0      .1       0   624.5    .045       0   639.5      .1       0
Bank Sta=624.5,639.5
XS Rating Curve= 0 ,0
Exp/Cntr=0.3,0.1

Type RM Length L Ch R = 1 ,9022.2  ,276.7,271.8,266.4
XS GIS Cut Line= 2
      1882402.72      228410.377     1881318.468      228264.281
#Sta/Elev= 30
       0 1860.66    59.7    1836    79.6 1823.64   139.2 1798.09   159.1 1785.11
   198.9 1768.16   238.7 1753.06   318.3 1731.66   387.9  1719.6   417.7 1709.79
   457.5  1689.3   477.4 1670.51   487.4 1665.45   507.2 1658.26   538.5 1652.59
     547 1651.32   553.5 1651.48   606.7 1665.89   626.6 1674.93   636.5  1683.3
   706.2 1713.63     726 1726.67   785.7  1755.2   865.3 1810.45   885.2 1829.12
   944.9 1867.82   964.8 1888.23   994.6 1906.88  1054.3 1924.74    1094  1928.1
#Mann= 3 , 0 , 0
       0      .1       0   538.5    .045       0   553.5      .1       0
Bank Sta=538.5,553.5
XS Rating Curve= 0 ,0
Exp/Cntr=0.3,0.1

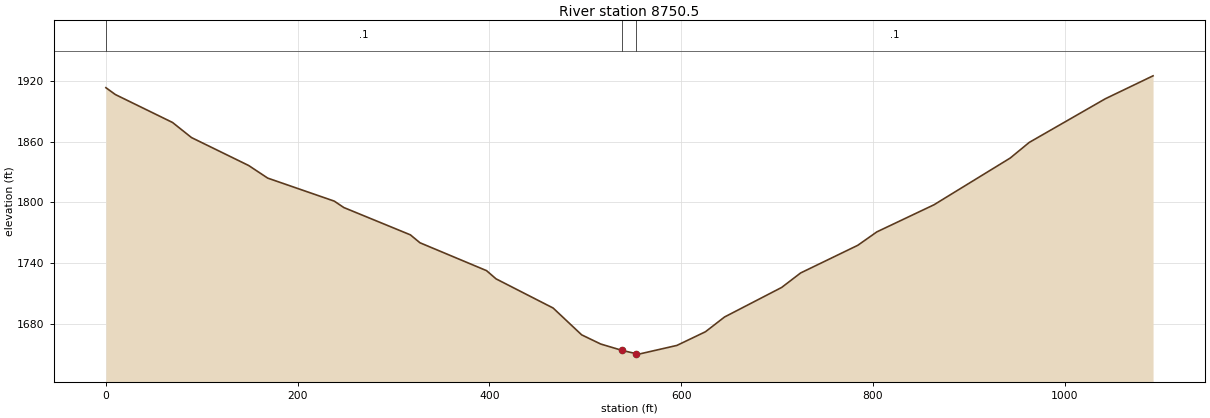
Type RM Length L Ch R = 1 ,8750.5  ,303.2,300,298
XS GIS Cut Line= 3
     1882407.337      228020.736     1881863.284      228066.094
     1881319.888      228122.708
#Sta/Elev= 30
       0 1913.28     9.9  1906.5    69.5 1878.93    89.3 1864.02   148.9 1836.44
   168.8 1823.98   238.2 1801.26   248.2 1794.91   317.6 1767.96   327.6 1760.13
     397 1732.62     407 1724.47   466.5 1695.68   496.3 1669.17   516.2 1660.11
   538.4 1653.84   553.4 1650.52   555.9 1650.15   595.6 1658.74   625.4 1672.24
   645.3 1686.81   704.9 1716.01   724.7 1730.32   784.3 1757.62   804.2 1770.88
   863.8 1797.65   943.3 1843.79   963.1  1859.2  1042.6 1902.39  1092.3    1925
#Mann= 3 , 0 , 0
       0      .1       0   538.4    .045       0   553.4      .1       0
Bank Sta=538.4,553.4
XS Rating Curve= 0 ,0
Exp/Cntr=0.3,0.1