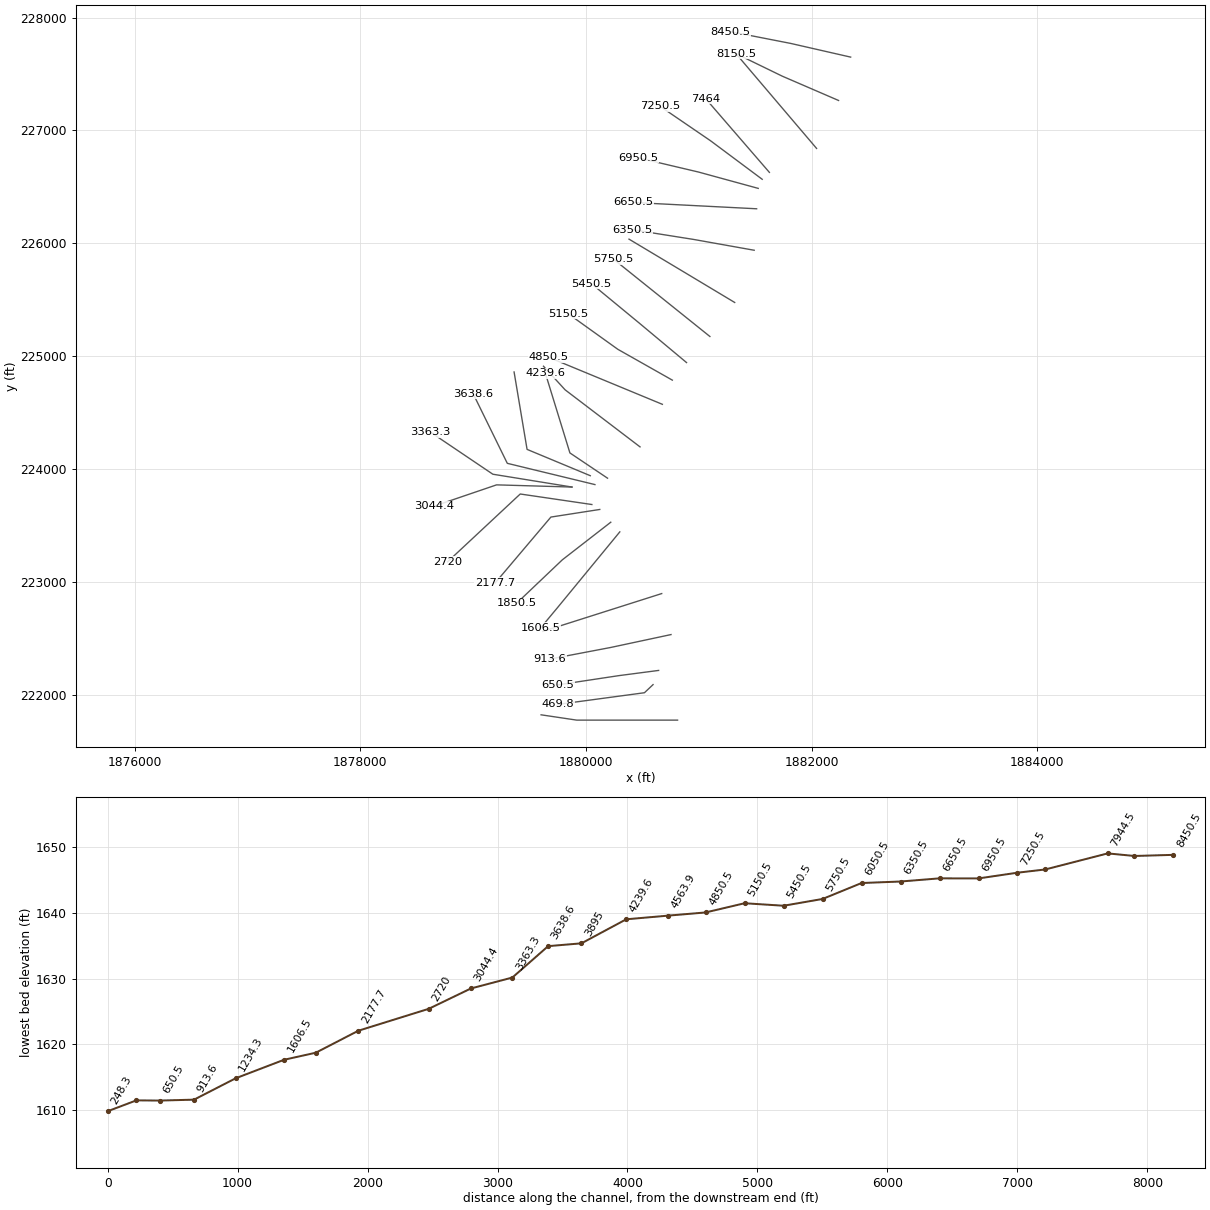
HEC-RAS study StnclCrk.prj: StnclCrk

--- StnclCrk.g01 (geometry) --- (continued)

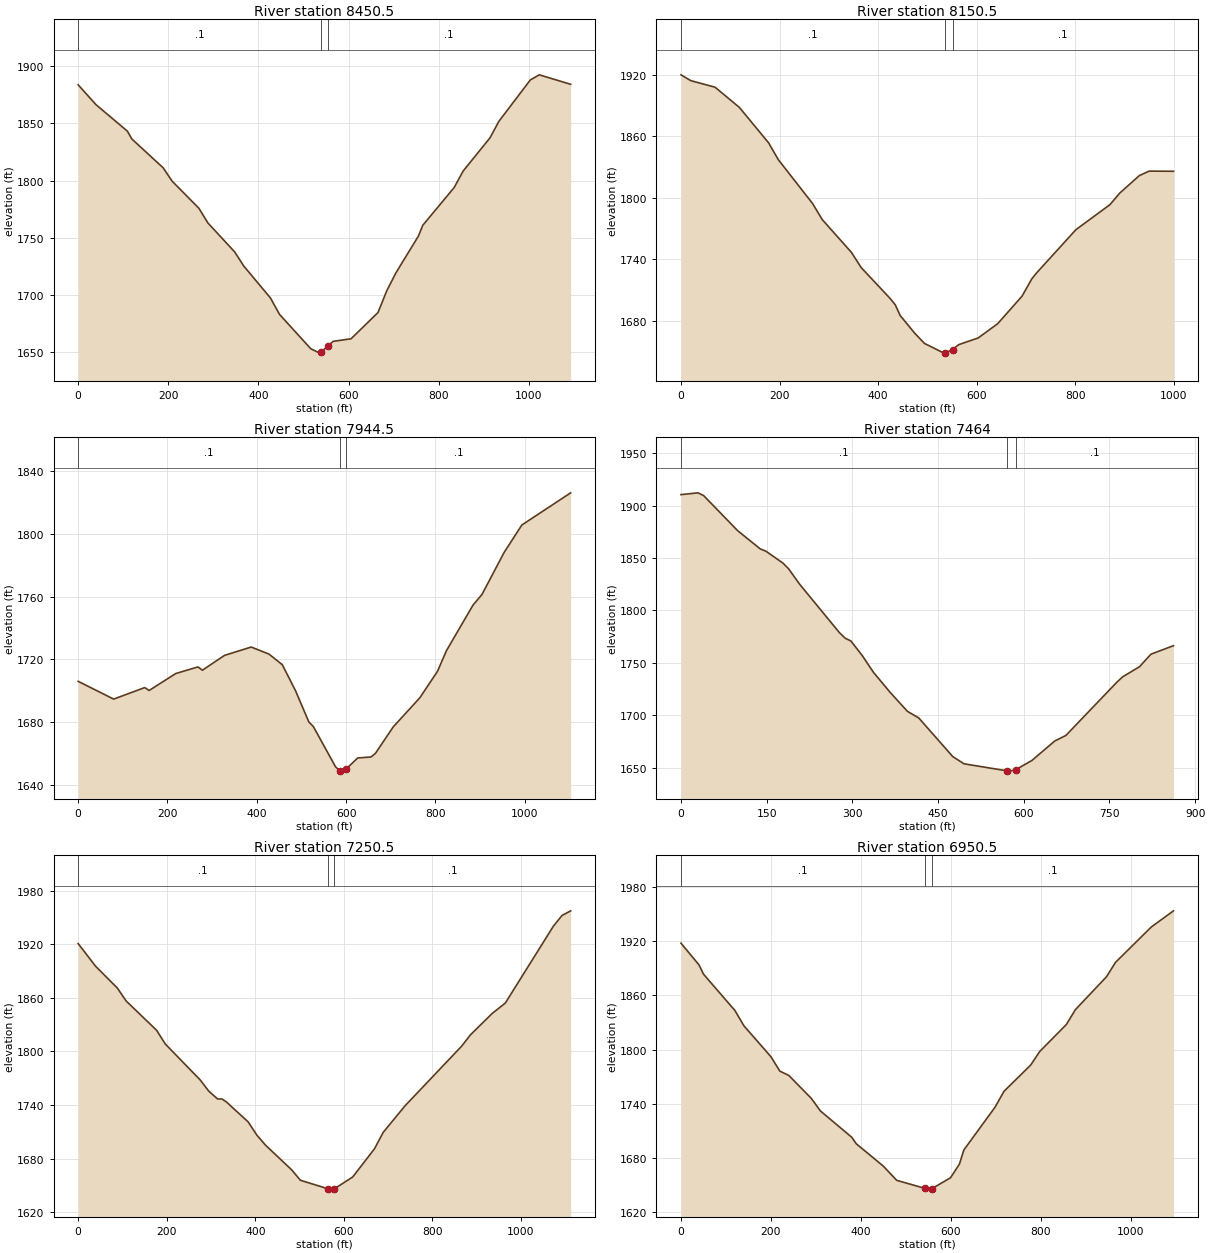
Type RM Length L Ch R = 1 ,8450.5  ,304.1,300,294.1
XS GIS Cut Line= 3
     1882346.875      227649.775     1881814.776      227771.225
     1881278.123      227876.135
#Sta/Elev= 30
       0 1883.86    39.7 1866.42   109.2 1843.25   119.1 1836.41   188.5 1811.18
   208.4 1799.49   267.9 1775.68   287.8 1762.84   347.3 1737.45   367.2  1725.2
   426.7 1697.07   446.6  1682.8     516 1652.66   535.9 1648.81   538.3 1649.46
   553.3 1654.86   565.7 1659.13   605.4 1661.39   665.1 1684.36     685 1703.79
   704.9 1719.12   754.6  1751.2   764.5  1760.8   834.1 1793.87     854 1808.29
   913.6 1837.41   933.5 1851.96  1003.1 1888.14    1023 1892.61  1092.6 1884.31
#Mann= 3 , 0 , 0
       0      .1       0   538.3    .045       0   553.3      .1       0
Bank Sta=538.3,553.3
XS Rating Curve= 0 ,0
Exp/Cntr=0.3,0.1

Type RM Length L Ch R = 1 ,8150.5  ,216.5,205.9,196.4
XS GIS Cut Line= 3
     1882239.615      227265.397      1881740.47      227480.961
     1881330.394      227680.458
#Sta/Elev= 30
       0 1919.99    19.8 1914.32    69.2 1907.92   118.6 1888.17   177.9 1853.62
   197.7 1837.16   266.9 1794.65   286.7 1778.85     346 1746.84   365.8 1732.01
   425.1 1701.64     435 1695.72   444.8  1685.4   474.5 1668.01   494.3 1658.07
   533.8 1648.64   536.2 1648.83   551.2 1652.17   563.5 1656.86   603.2 1663.43
   642.8 1677.33   692.4 1704.27   712.2 1721.16   722.2 1727.06   801.5 1768.96
   870.8 1793.46   890.7 1804.73   930.3 1821.73   950.2  1826.1   999.7 1825.96
#Mann= 3 , 0 , 0
       0      .1       0   536.2    .045       0   551.2      .1       0
Bank Sta=536.2,551.2
XS Rating Curve= 0 ,0
Exp/Cntr=0.3,0.1

Type RM Length L Ch R = 1 ,7944.5  ,480.1,480.5,480.8
XS GIS Cut Line= 2
     1882044.838      226840.392     1881330.394      227680.458
#Sta/Elev= 30
       0 1706.12    79.5 1694.82     149 1702.15     159 1700.31   218.6 1711.09
   268.2 1715.28   278.2  1713.2   327.9 1722.65   387.5 1727.91   427.2 1723.44
     457 1716.72   486.8 1700.08   516.6 1680.26   526.6 1677.38   576.2 1651.83
   585.3 1649.28   586.2 1649.03   600.3 1650.46   625.9  1657.4   655.7 1658.01
   665.6 1660.31   705.4 1677.13     765 1695.65   804.7 1712.55   824.6  1725.6
   884.2 1754.62   904.1 1761.31   953.8 1788.07   993.5 1805.51  1102.8 1825.96
#Mann= 3 , 0 , 0
       0      .1       0   585.3    .045       0   600.3      .1       0
Bank Sta=585.3,600.3
XS Rating Curve= 0 ,0
Exp/Cntr=0.3,0.1

Type RM Length L Ch R = 1 ,7464    ,208.7,213.6,219.4
XS GIS Cut Line= 2
     1881626.639      226628.003     1881062.753      227280.159
#Sta/Elev= 30
       0 1910.41    29.7 1912.12    39.6 1909.52    99.1 1876.04   138.7 1858.64
   148.6 1856.44   178.4 1845.12   188.3 1839.69   208.1 1824.62   277.5 1778.61
   287.4 1773.41   297.3  1770.8   317.1    1757   336.9 1740.82   366.6 1721.44
   396.4 1703.63   416.2 1697.32   475.7 1660.47   495.5 1653.57   570.6 1646.87
   574.8 1646.59   585.6 1647.84   614.4 1656.82     654 1675.25   673.8 1680.67
     763 1731.46     773 1736.54   802.7 1746.24   822.5 1758.14   862.1  1766.3
#Mann= 3 , 0 , 0
       0      .1       0   570.6    .045       0   585.6      .1       0
Bank Sta=570.6,585.6
XS Rating Curve= 0 ,0
Exp/Cntr=0.3,0.1

Type RM Length L Ch R = 1 ,7250.5  ,291.3,299.8,308.1
XS GIS Cut Line= 3
     1881562.786      226566.894     1881105.109      226908.216
     1880657.886      227213.701
#Sta/Elev= 30
       0  1920.7    39.4 1895.32    88.6 1870.87   108.3 1856.55   177.2 1823.72
   196.9 1808.34   275.6 1768.21   295.3 1755.52     315 1746.92   324.8 1746.92
   334.7 1743.62   383.9 1721.35   403.6 1706.54   423.3 1695.21   482.3 1667.66
     502    1656   563.4 1646.64   570.9  1646.1   578.4 1646.37   620.2  1659.7
   669.4 1691.28   689.1  1709.6   738.3 1739.24   866.4 1806.06     886 1818.56
   935.3 1842.58   964.8 1854.12  1073.2 1939.97  1092.8 1952.07  1112.5  1957.3
#Mann= 3 , 0 , 0
       0      .1       0   563.4    .045       0   578.4      .1       0
Bank Sta=563.4,578.4
XS Rating Curve= 0 ,0
Exp/Cntr=0.3,0.1

Type RM Length L Ch R = 1 ,6950.5  ,295.1,300,304.1
XS GIS Cut Line= 3
     1881527.575      226486.271     1880997.468       226631.26
     1880466.658      226756.433
#Sta/Elev= 30
       0 1917.91      40 1893.87      50 1883.62   119.9 1843.27   139.9  1826.3
   199.8 1792.13   219.8 1776.07   239.8 1771.25   289.8 1745.82   309.8    1732
   379.7 1702.71   389.7 1695.52   449.6 1670.83   479.6 1654.98   542.1 1646.12
   549.6 1645.23   557.1 1645.49   599.2 1657.83     619 1672.96   628.9 1688.65
   698.3 1736.15   718.2 1753.75   777.6 1782.83   797.5 1797.81     857 1827.87
   876.8 1844.17   946.2 1880.81     966 1896.61  1045.4 1935.77    1095 1953.78
#Mann= 3 , 0 , 0
       0      .1       0   542.1    .045       0   557.1      .1       0
Bank Sta=542.1,557.1
XS Rating Curve= 0 ,0
Exp/Cntr=0.3,0.1

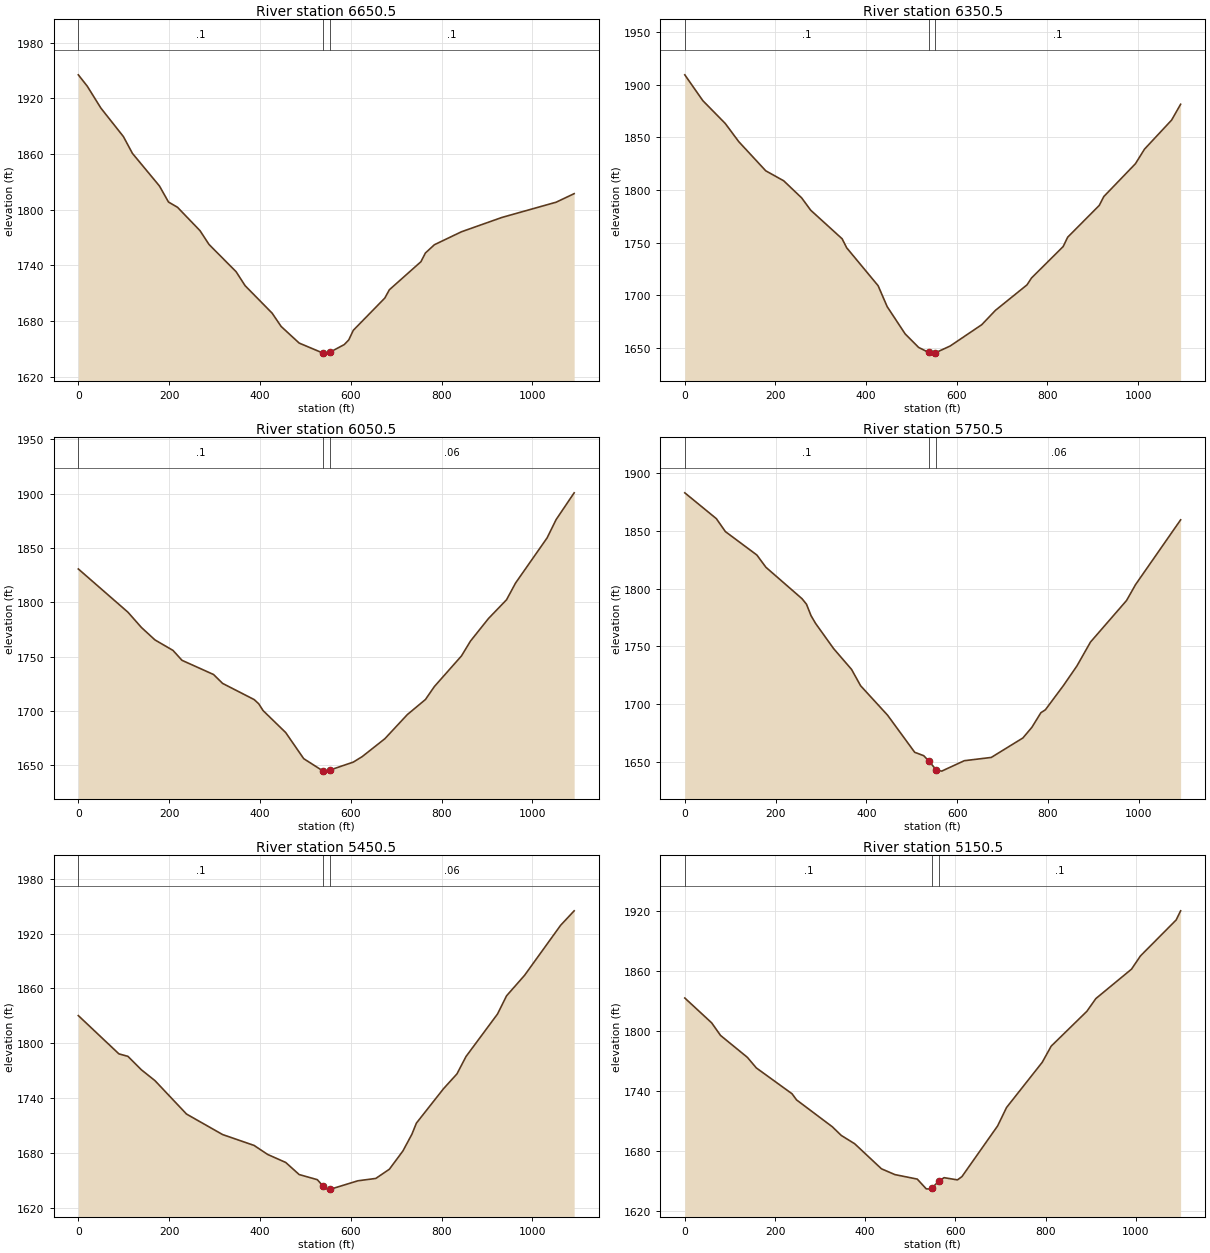
Type RM Length L Ch R = 1 ,6650.5  ,302.8,300,297.6
XS GIS Cut Line= 3
     1881513.519      226305.485     1880968.229      226333.328
     1880422.939      226361.171
#Sta/Elev= 30
       0 1945.21    19.8 1932.87    49.6 1909.41    99.3 1878.63   119.1 1860.57
   178.7 1825.38   198.6 1808.08   218.4 1802.46     268 1777.23   287.9 1762.33
   347.4 1733.06   367.3 1717.94   426.9 1688.28   446.7 1673.96   486.4 1656.07
   538.5 1645.35     546 1645.24   553.5 1646.07   585.7 1654.46   595.6 1659.48
   605.6 1669.85     675  1704.6     685 1713.52   754.5 1743.75   764.4 1753.16
   784.2 1762.08   843.8 1776.05   933.2 1791.53  1052.3 1807.91    1092 1817.13
#Mann= 3 , 0 , 0
       0      .1       0   538.5    .045       0   553.5      .1       0
Bank Sta=538.5,553.5
XS Rating Curve= 0 ,0
Exp/Cntr=0.3,0.1

Type RM Length L Ch R = 1 ,6350.5  ,308.2,300,291.4
XS GIS Cut Line= 3
     1881491.709      225937.876     1880954.615      226033.808
     1880413.094      226119.773
#Sta/Elev= 30
       0 1909.64    39.7  1885.1    89.3 1863.32     119 1846.06   178.6 1818.29
   218.2 1808.78   257.9 1792.48   277.8 1780.77   347.2 1753.54   357.1 1745.04
   426.6 1708.88   446.4 1689.07   486.1  1663.1   515.8 1650.22   538.1 1645.37
   545.6 1644.76   553.1 1645.09   585.5 1651.55   655.2 1671.83   685.2 1685.42
     755 1709.73   764.9 1716.27   834.7 1746.17   844.7 1755.08   914.4 1785.35
   924.4 1793.77   994.2 1825.03  1014.1 1838.85    1074 1866.56  1093.9 1881.63
#Mann= 3 , 0 , 0
       0      .1       0   538.1    .045       0   553.1      .1       0
Bank Sta=538.1,553.1
XS Rating Curve= 0 ,0
Exp/Cntr=0.3,0.1

Type RM Length L Ch R = 1 ,6050.5  ,303,300,296.9
XS GIS Cut Line= 3
     1881319.064      225475.039     1880850.885      225755.973
     1880382.376      226036.358
#Sta/Elev= 30
       0 1830.61   109.2 1790.84     139 1776.74   168.8 1765.29   208.5 1755.65
   228.3 1746.52   297.8 1733.46   317.7 1725.29   387.2  1710.4   397.1 1706.62
     407 1700.22   456.6 1680.07   496.4 1655.99   538.5 1644.76     546 1644.53
   553.5 1645.42   605.6 1652.84   625.4 1657.95     675 1674.31   724.7 1696.62
   764.4 1710.41   784.2 1722.41   843.8 1750.56   863.7 1764.25   903.4 1785.04
   943.1 1802.27     963  1817.7  1032.4  1859.2  1052.3 1876.08    1092 1900.69
#Mann= 3 , 0 , 0
       0      .1       0   538.5    .045       0   553.5     .06       0
Bank Sta=538.5,553.5
XS Rating Curve= 0 ,0
Exp/Cntr=0.3,0.1

Type RM Length L Ch R = 1 ,5750.5  ,300.4,300,299.7
XS GIS Cut Line= 3
     1881099.239      225173.568     1880673.331      225515.209
     1880247.423       225856.85
#Sta/Elev= 30
       0  1882.9    69.5 1860.56    89.4 1849.36   158.8 1829.06   178.7 1818.47
   258.1 1791.32     268 1786.53     278 1776.64   287.9 1769.99   327.6  1748.2
   367.3  1730.1   387.2 1715.99   446.7 1690.46   506.3 1658.42   526.2 1655.46
   538.5 1650.45   553.5 1643.27   565.8 1642.11   615.5 1651.12     675 1653.96
   744.6  1670.8   764.4    1680   784.2 1692.63   794.2  1695.2   833.9 1716.17
   863.7 1733.17   893.4 1753.74   972.9 1789.73   992.7 1803.47    1092 1859.52
#Mann= 3 , 0 , 0
       0      .1       0   538.5    .045       0   553.5     .06       0
Bank Sta=538.5,553.5
XS Rating Curve= 0 ,0
Exp/Cntr=0.3,0.1

Type RM Length L Ch R = 1 ,5450.5  ,295.9,300,301.5
XS GIS Cut Line= 3
     1880892.144      224942.412     1880472.984      225292.319
     1880051.691      225639.631
#Sta/Elev= 30
       0 1830.42    89.4 1788.66   109.2 1785.96     139 1771.24   168.8 1759.45
   238.3 1722.98   317.7 1700.63   387.2 1688.73     417 1678.91   456.7  1670.2
   486.4 1656.98   526.2 1651.42   538.5 1644.71     546  1641.4   553.5 1641.16
   555.9 1641.08   615.5 1650.15   655.2 1652.76     685 1662.78   714.8 1682.67
   734.6 1700.92   744.6 1713.13   804.1 1750.55   833.9 1766.82   853.8 1785.76
   923.2 1832.15   943.1 1851.99   982.8 1874.38  1062.2 1928.96    1092 1944.74
#Mann= 3 , 0 , 0
       0      .1       0   538.5    .045       0   553.5     .06       0
Bank Sta=538.5,553.5
XS Rating Curve= 0 ,0
Exp/Cntr=0.3,0.1

Type RM Length L Ch R = 1 ,5150.5  ,297.2,300,305.2
XS GIS Cut Line= 3
     1880766.366      224786.628     1880283.332      225059.885
     1879840.986      225376.866
#Sta/Elev= 30
       0 1832.79    59.5 1807.95    79.3  1795.3   138.7  1773.4   158.6 1762.78
   237.8 1736.91   247.8 1730.76     327  1703.9   346.9 1695.21   376.6 1686.89
     436  1661.8   465.8    1656   515.3 1651.51   535.2 1641.78   545.1 1641.46
   547.5 1642.37   562.5  1649.2   574.8 1652.93   604.4 1650.71   614.3 1653.93
   693.5 1704.74   713.3 1723.18   792.4 1768.42   812.2 1784.57   891.4  1819.5
   911.2  1832.2   990.3 1861.67  1010.1 1874.89  1089.3 1910.92  1099.2 1920.07
#Mann= 3 , 0 , 0
       0      .1       0   547.5    .045       0   562.5      .1       0
Bank Sta=547.5,562.5
XS Rating Curve= 0 ,0
Exp/Cntr=0.3,0.1

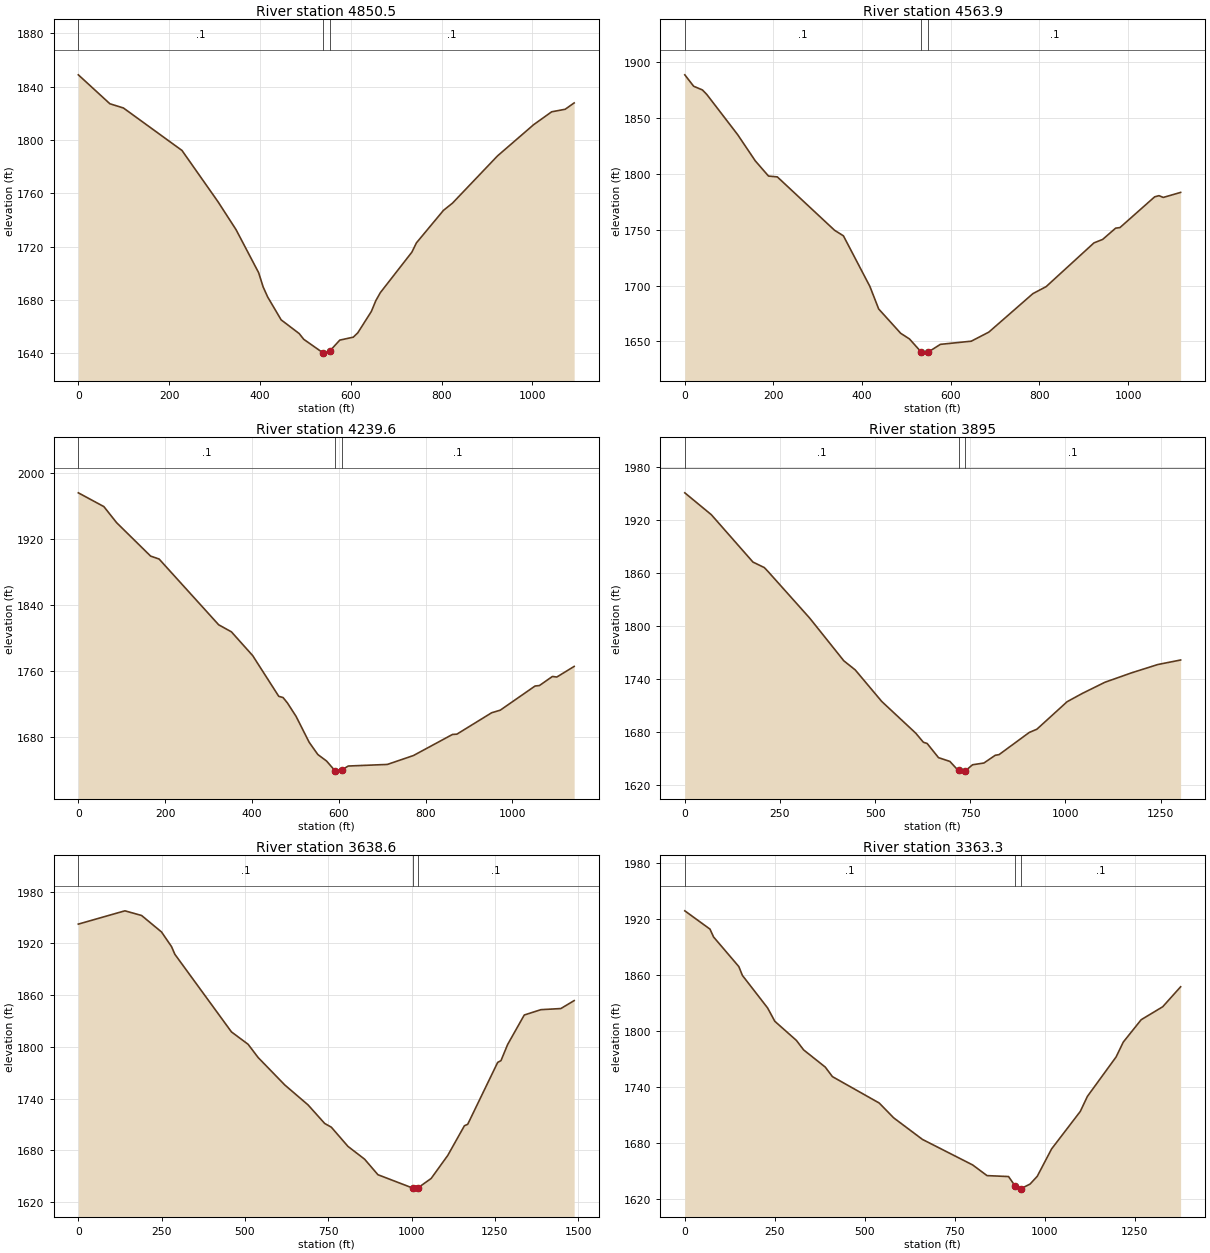
Type RM Length L Ch R = 1 ,4850.5  ,292.4,286.6,280.7
XS GIS Cut Line= 3
     1880677.891      224572.361      1880173.34      224781.035
      1879668.79      224989.709
#Sta/Elev= 30
       0 1848.76    69.5 1827.06    99.3  1823.9   228.3 1792.04   307.8  1753.5
   347.4 1732.63   397.1 1700.39     407 1689.74     417 1682.17   446.7 1665.01
   486.4 1654.74   496.4 1650.44   538.5 1640.36     546 1640.06   553.5 1641.53
   575.8 1649.81   605.6 1652.04   615.5  1655.3   645.3 1671.28   655.2  1679.4
   665.1  1685.4   734.6 1715.78   744.6 1722.74   804.1  1747.1     824 1752.52
   923.2 1787.96  1002.6 1811.33  1042.4 1821.02  1072.2 1822.93    1092 1827.69
#Mann= 3 , 0 , 0
       0      .1       0   538.5    .045       0   553.5      .1       0
Bank Sta=538.5,553.5
XS Rating Curve= 0 ,0
Exp/Cntr=0.3,0.1

Type RM Length L Ch R = 1 ,4563.9  ,338.2,324.2,310.3
XS GIS Cut Line= 3
     1880480.022      224195.021     1879815.799      224700.873
     1879624.274      224909.938
#Sta/Elev= 30
       0 1888.23    19.9 1878.05    39.8 1874.71    49.7 1870.67   119.3 1834.76
     159 1811.36   188.8 1797.78   208.7 1797.03   337.9 1749.32   357.8 1744.38
   417.5 1699.17   437.3 1679.06     487 1657.29   506.9 1652.22   533.3 1640.49
   536.7 1639.58   548.3 1640.32   576.5 1647.42   646.1 1650.24   685.8 1658.35
   785.2 1692.74     815 1698.98   922.9 1738.07   942.5 1741.16   971.8 1751.24
   981.6 1751.76  1059.8 1779.21  1069.6 1780.26  1079.3 1778.69  1118.4 1783.18
#Mann= 3 , 0 , 0
       0      .1       0   533.3    .045       0   548.3      .1       0
Bank Sta=533.3,548.3
XS Rating Curve= 0 ,0
Exp/Cntr=0.3,0.1

Type RM Length L Ch R = 1 ,4239.6  ,347.6,344.6,341.6
XS GIS Cut Line= 3
     1880191.977      223917.559     1879858.487      224141.429
     1879640.551       224849.16
#Sta/Elev= 30
       0 1976.29    58.8 1959.62    88.2 1940.11   166.5 1899.63   186.1 1896.05
   323.3 1816.37   352.7 1807.81   401.7 1778.98   461.7  1729.7   471.7 1728.15
   481.7 1721.64   501.7  1705.3   531.8 1673.96   551.8  1659.1   571.8 1651.29
   591.8 1639.15   601.8 1639.02   606.8 1640.46   621.8  1645.2   711.9 1647.13
   771.9  1657.9     862 1683.49     872  1683.8     952 1709.72   972.1 1712.92
  1052.1 1742.16  1062.1 1742.71  1092.2 1753.76  1102.2 1753.04  1142.2 1765.92
#Mann= 3 , 0 , 0
       0      .1       0   591.8    .045       0   606.8      .1       0
Bank Sta=591.8,606.8
XS Rating Curve= 0 ,0
Exp/Cntr=0.3,0.1

Type RM Length L Ch R = 1 ,3895    ,249.8,256.4,262.9
XS GIS Cut Line= 3
     1880039.153      223939.579     1879478.784      224172.883
     1879363.672       224859.07
#Sta/Elev= 30
       0 1950.35    69.7  1925.6   179.1 1871.99     209 1865.73   218.9 1861.24
   328.4 1808.45   417.9  1760.2   447.8 1749.94   517.4 1714.26     607 1678.26
   626.9 1668.04   636.8 1666.65   666.6 1650.65   696.4 1646.38   716.3 1637.17
   721.3 1637.12   736.2 1635.37   736.3  1635.4   756.1 1642.57   785.9 1644.54
   815.7  1653.3   825.7 1654.04   905.2 1679.17   925.1  1682.8  1004.6 1713.95
  1044.3 1723.28    1104 1735.97  1173.6 1746.58  1243.1 1756.04  1302.8 1761.14
#Mann= 3 , 0 , 0
       0      .1       0   721.3    .045       0   736.3      .1       0
Bank Sta=721.3,736.3
XS Rating Curve= 0 ,0
Exp/Cntr=0.3,0.1

Type RM Length L Ch R = 1 ,3638.6  ,263.6,275.4,287.2
XS GIS Cut Line= 3
     1880080.182      223860.956     1879303.536      224049.311
     1879000.237      224667.591
#Sta/Elev= 30
       0  1942.3   139.8  1957.7   189.8  1952.3   249.7 1933.14   279.7 1916.19
   289.7 1907.27   459.5 1817.27   509.5  1802.9   539.4 1787.64   619.4 1755.78
   689.3 1732.63   739.2 1711.12   759.2 1706.76   809.1  1684.5     859 1669.67
     899 1651.66    1004 1636.08  1008.8 1634.94    1019 1636.39  1058.7  1647.3
  1108.6 1674.08  1158.5 1708.43  1168.4 1710.14  1258.3 1781.91  1268.2 1783.96
  1288.2 1802.69  1338.1 1836.88    1388 1843.06  1447.9 1844.37  1487.8 1853.58
#Mann= 3 , 0 , 0
       0      .1       0    1004    .045       0    1019      .1       0
Bank Sta=1004,1019
XS Rating Curve= 0 ,0
Exp/Cntr=0.3,0.1

Type RM Length L Ch R = 1 ,3363.3  ,298,318.9,339.8
XS GIS Cut Line= 3
     1879876.757       223839.11     1879175.471      223952.701
     1878622.119      224325.968
#Sta/Elev= 30
       0 1928.84      70 1909.21      80 1900.76   150.1 1869.04   160.1 1859.53
   230.1 1824.64   250.2 1810.28   310.2 1789.76   330.2 1779.61   390.2 1761.19
   410.2 1750.92   540.3 1722.57   580.4  1706.7   660.4 1683.53   800.1  1656.1
   839.9 1644.67   899.7 1643.67     918 1633.51   929.6 1630.17     933  1630.5
   959.5  1635.6   979.4  1643.9  1019.3  1673.3    1099 1713.52  1118.9 1729.74
  1198.6 1772.03  1218.5 1787.95  1268.3 1811.99  1328.1 1825.88  1377.9 1847.32
#Mann= 3 , 0 , 0
       0      .1       0     918    .045       0     933      .1       0
Bank Sta=918,933
XS Rating Curve= 0 ,0
Exp/Cntr=0.3,0.1

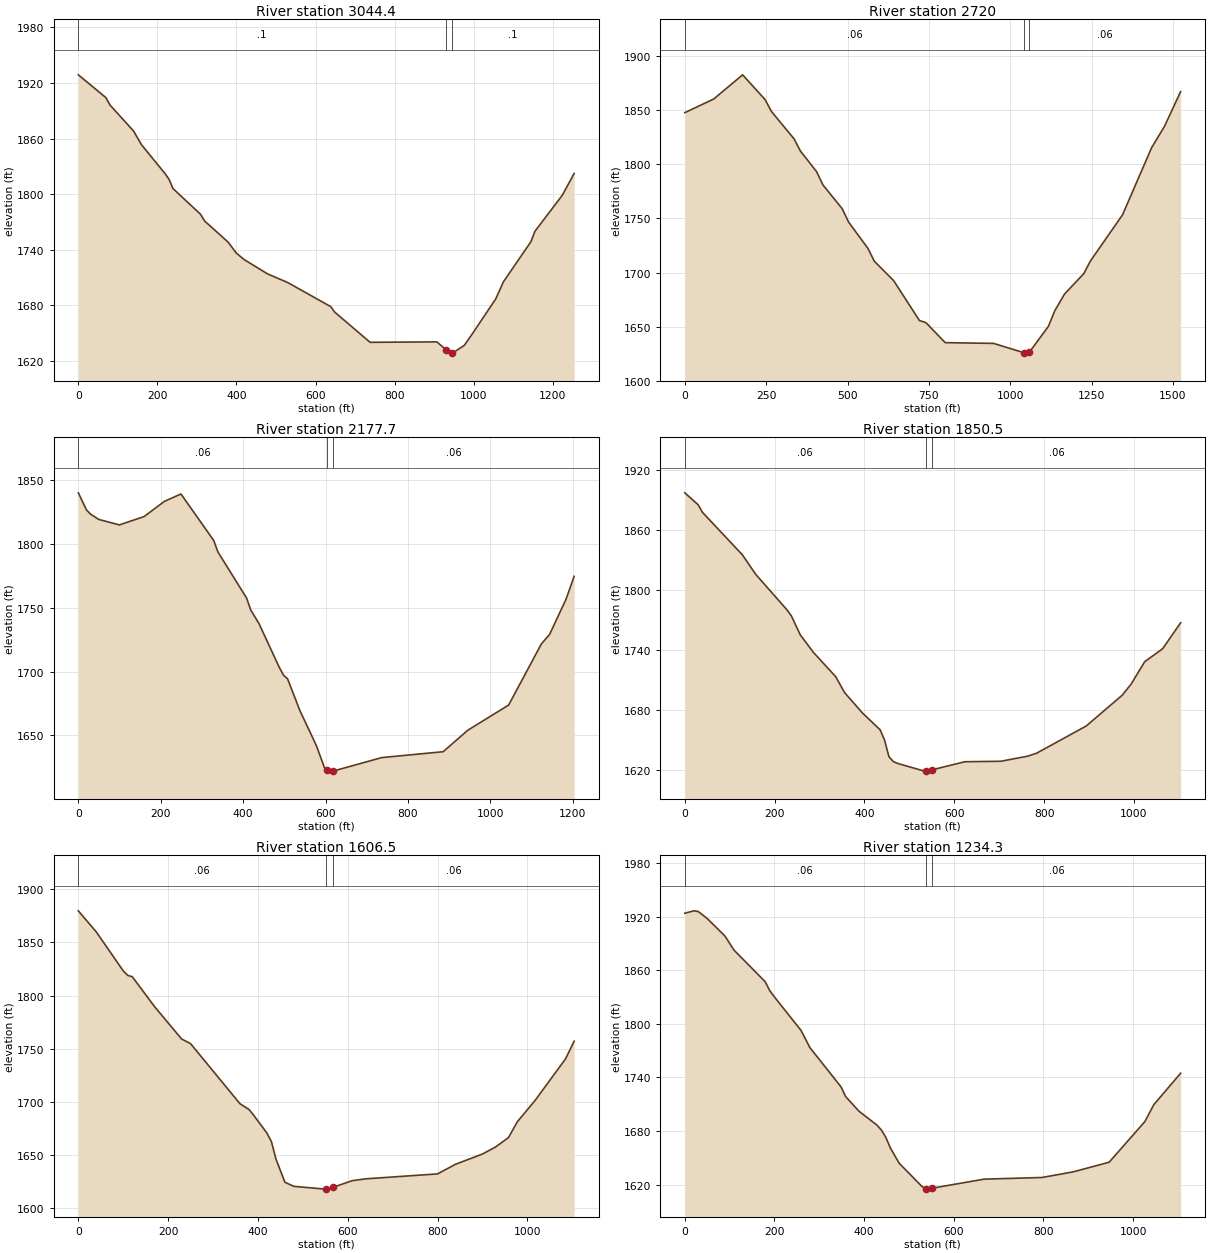
Type RM Length L Ch R = 1 ,3044.4  ,314.9,324.4,334
XS GIS Cut Line= 3
     1879876.757       223839.11      1879208.56      223858.434
     1878654.221      223669.608
#Sta/Elev= 30
       0 1928.84    69.8 1904.22    79.8 1896.41   139.7 1868.18   159.6 1853.48
   219.5 1822.18   229.5 1816.03   239.4 1806.11   309.3 1778.29   319.3 1771.14
   379.1 1748.22   399.1 1736.69     419 1729.58   478.9 1713.94   528.8 1704.87
   638.5 1678.68   648.5 1672.77     738 1640.17   906.7 1640.65   929.9 1632.26
   944.9 1628.65   946.4 1628.51   976.2  1636.9     996    1649  1055.6  1686.9
  1075.4 1705.61  1144.9 1748.86  1154.8 1759.95  1224.3 1799.01  1254.1 1822.42
#Mann= 3 , 0 , 0
       0      .1       0   929.9    .045       0   944.9      .1       0
Bank Sta=929.9,944.9
XS Rating Curve= 0 ,0
Exp/Cntr=0.3,0.1

Type RM Length L Ch R = 1 ,2720    ,537.8,541.7,545.4
XS GIS Cut Line= 3
     1880053.078      223684.212     1879418.121      223777.453
     1878773.348       223175.77
#Sta/Elev= 30
       0 1847.87    88.9  1860.5   177.7 1882.88   246.8 1859.98   266.6 1848.82
   335.7 1823.69   355.4 1812.35   404.8 1793.41   424.6    1781   483.8    1759
   503.5  1746.6   562.8 1722.33   582.5 1710.41   641.8  1692.5     721 1655.59
   740.9 1653.66   800.3 1635.12     949 1634.43  1043.3 1625.69    1048 1625.42
  1058.3 1626.03  1117.4 1650.21  1137.2 1664.75    1167 1680.08  1226.4 1699.06
  1246.2 1710.52  1345.3 1753.41  1434.5 1815.44  1474.1 1835.19  1523.7 1867.37
#Mann= 3 , 0 , 0
       0     .06       0  1043.3    .045       0  1058.3     .06       0
Bank Sta=1043.3,1058.3
XS Rating Curve= 0 ,0
Exp/Cntr=0.3,0.1

Type RM Length L Ch R = 1 ,2177.7  ,332,327.4,324.9
XS GIS Cut Line= 3
      1880123.19      223640.446      1879689.98      223572.997
     1879195.692      222988.838
#Sta/Elev= 30
       0 1839.75    19.9 1826.32    29.9 1823.04    49.8 1818.92    99.6 1814.67
   159.4 1821.14   209.2 1833.12   249.1 1838.84   328.8 1802.43   338.8 1793.53
   408.5 1757.43   418.5 1748.14   438.4  1737.6   488.1 1703.05   498.1 1697.13
     508 1694.24   537.8 1669.46   577.6 1642.24   597.4 1624.89   604.4 1622.97
   617.3 1622.09   619.4 1622.19   736.6 1632.68   885.6 1637.27   945.3 1654.03
  1044.6 1673.78  1124.2 1721.68    1144    1729  1183.8 1756.44  1203.6 1774.46
#Mann= 3 , 0 , 0
       0     .06       0   604.4    .045       0   619.4     .06       0
Bank Sta=604.4,619.4
XS Rating Curve= 0 ,0
Exp/Cntr=0.3,0.1

Type RM Length L Ch R = 1 ,1850.5  ,238.9,243.9,246.6
XS GIS Cut Line= 3
     1880220.739      223527.379     1879791.451      223194.147
      1879385.23      222807.981
#Sta/Elev= 30
       0 1896.88    29.6 1885.04    39.5  1877.3   128.4 1834.82   158.1 1815.31
   227.3 1780.05   237.1 1774.07   256.9 1755.08   286.5 1737.33     336 1713.12
   355.7  1697.3   395.2 1677.02   434.8 1660.09   444.6 1650.05   454.5  1633.2
   464.4 1628.27   474.3 1626.38   533.6 1618.75   535.9  1618.8   550.9  1620.1
   623.5 1628.13   703.6 1628.61   763.6 1633.71   783.6 1636.72   893.8 1663.87
   973.8  1694.6   993.8 1705.76  1023.9  1728.1  1063.9  1741.1  1103.9 1767.04
#Mann= 3 , 0 , 0
       0     .06       0   535.9    .045       0   550.9     .06       0
Bank Sta=535.9,550.9
XS Rating Curve= 0 ,0
Exp/Cntr=0.3,0.1

Type RM Length L Ch R = 1 ,1606.5  ,385.4,372.2,358.9
XS GIS Cut Line= 3
     1880300.694      223441.686     1879741.655      222761.915
     1879598.073      222589.802
#Sta/Elev= 30
       0 1879.76      40  1859.9     100 1823.23     110 1818.97     120 1817.79
     170 1789.45     230 1759.08     250 1754.67     360 1698.12     380  1692.7
     390 1687.58   420.1 1670.42   430.1 1662.39   440.1 1646.15   460.1 1624.15
   480.1 1620.29   550.1 1617.68   551.3 1617.76   566.3 1619.29   610.1 1625.64
   640.1 1627.38   800.1 1632.02   840.1  1641.1   899.6 1650.64   928.8 1657.23
   958.1 1666.27   977.6 1681.01  1016.6 1700.81  1084.8 1740.16  1104.3 1756.94
#Mann= 3 , 0 , 0
       0     .06       0   551.3    .045       0   566.3     .06       0
Bank Sta=551.3,566.3
XS Rating Curve= 0 ,0
Exp/Cntr=0.3,0.1

Type RM Length L Ch R = 1 ,1234.3  ,322.9,320.6,318.1
XS GIS Cut Line= 2
     1880672.097      222894.845     1879618.083      222559.706
#Sta/Elev= 30
       0 1924.08    19.9 1926.78    29.9 1926.06    49.8 1918.29    89.7 1898.47
   109.6 1882.86   179.4 1847.28   189.3 1837.56   199.3 1830.68   259.1 1792.87
     279 1773.54   348.7 1729.36   358.7 1718.67   388.6 1702.17   428.5 1686.67
   438.4 1681.17   448.4 1672.94   458.4 1661.14   478.3 1643.88   528.1 1618.29
   537.5 1615.08   538.1 1614.87   552.5 1615.99   667.6 1626.05   797.1 1627.92
   866.9 1634.28   946.6 1645.03  1026.3 1690.61  1046.2 1709.54    1106 1744.77
#Mann= 3 , 0 , 0
       0     .06       0   537.5    .045       0   552.5     .06       0
Bank Sta=537.5,552.5
XS Rating Curve= 0 ,0
Exp/Cntr=0.3,0.1

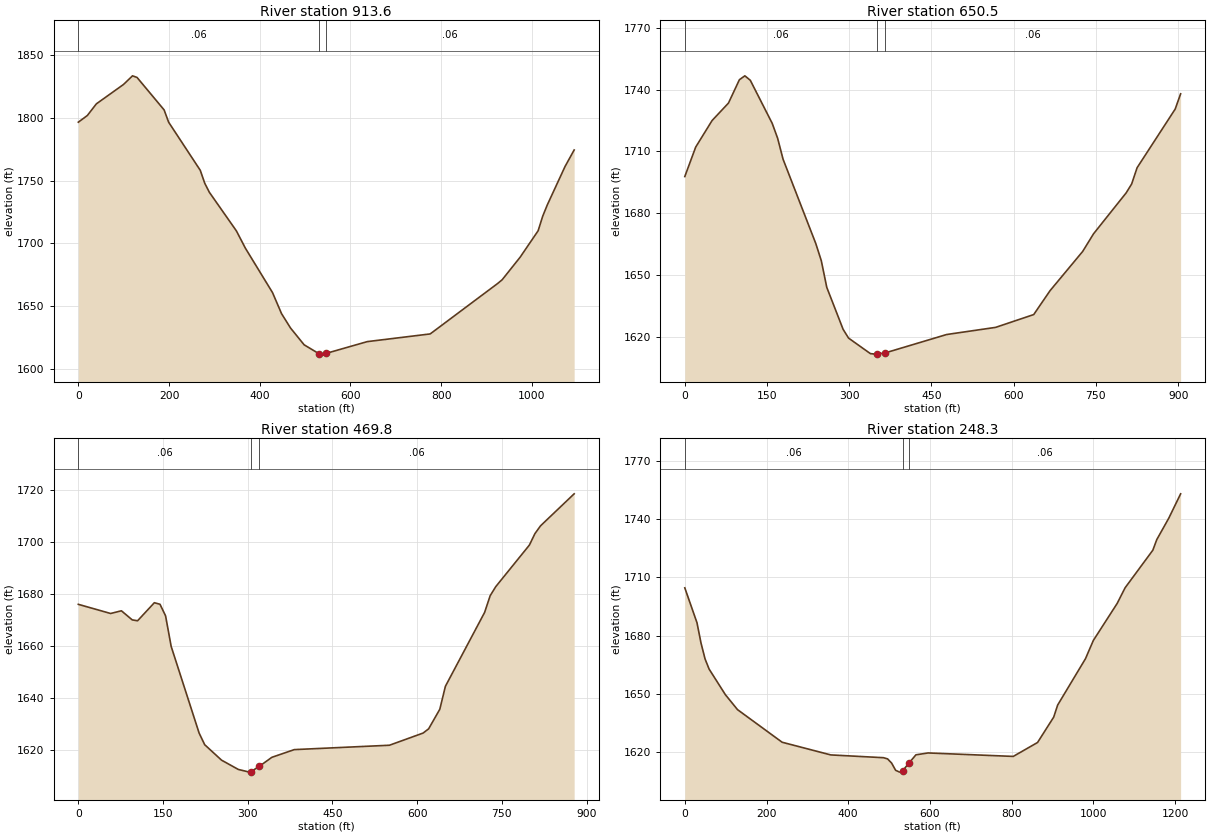
Type RM Length L Ch R = 1 ,913.6   ,265.1,263,261.7
XS GIS Cut Line= 3
     1880754.709      222531.497     1880219.006      222416.998
     1879682.957      222314.917
#Sta/Elev= 30
       0 1796.74    19.9 1802.08    39.8 1811.38    99.6 1826.83   119.5 1833.74
   129.5 1832.44   189.2 1806.52   199.2 1796.71   268.9 1758.35   278.9 1747.94
   288.8 1740.88   348.6 1709.98   368.5 1696.12   428.3 1660.71   448.2 1643.91
   468.1  1632.4     498 1619.05   530.9 1611.92   537.8 1611.62   545.9 1612.15
   637.1 1621.59     776 1627.74   924.8    1668   934.7 1670.96   974.4 1688.99
  1014.1 1710.11    1024 1721.55    1034  1730.5  1073.6 1761.51  1093.5 1774.56
#Mann= 3 , 0 , 0
       0     .06       0   530.9    .045       0   545.9     .06       0
Bank Sta=530.9,545.9
XS Rating Curve= 0 ,0
Exp/Cntr=0.3,0.1

Type RM Length L Ch R = 1 ,650.5   ,180.5,180.6,180.3
XS GIS Cut Line= 3
     1880644.855      222213.705     1880289.343      222167.112
     1879749.489      222085.494
#Sta/Elev= 30
       0 1697.77    19.9  1712.1    49.8    1725    79.7 1733.49    99.6 1744.83
   109.6 1746.72   119.5 1744.55   159.4 1723.66   169.3 1716.42   179.3 1706.17
     239 1665.19     249  1656.9     259 1643.93   288.8 1623.53   298.8 1619.26
   338.6 1611.72   348.6 1611.48   351.1 1611.53   366.1 1612.12   477.7 1621.01
     567 1624.48   636.5  1630.7   666.3 1642.31   725.8 1661.37   745.7 1669.97
   805.3 1689.89   815.2 1694.18   825.1 1702.06   894.6 1730.57   904.5 1737.98
#Mann= 3 , 0 , 0
       0     .06       0   351.1    .045       0   366.1     .06       0
Bank Sta=351.1,366.1
XS Rating Curve= 0 ,0
Exp/Cntr=0.3,0.1

Type RM Length L Ch R = 1 ,469.8   ,224.4,221.4,218.4
XS GIS Cut Line= 3
     1880595.426      222087.886     1880519.036      222015.989
     1879752.889      221912.638
#Sta/Elev= 30
       0 1675.98    57.2 1672.46    76.3  1673.5    95.4 1670.01   104.9 1669.66
   134.6  1676.6   144.6 1676.01   154.5 1671.55   164.4 1659.81   213.9 1626.51
   223.8 1622.04   253.6 1616.11   283.3 1612.54   303.1 1611.51   305.1 1611.63
   320.1 1613.68   342.8 1617.21   382.4 1620.16   550.9 1621.84   610.4 1626.51
   620.3 1628.14   640.1 1635.67     650 1644.49   719.4 1672.86   729.3 1679.31
   739.2 1682.78   798.7 1698.74   808.6 1703.17   818.5 1706.15     878 1718.44
#Mann= 3 , 0 , 0
       0     .06       0   305.1    .045       0   320.1     .06       0
Bank Sta=305.1,320.1
XS Rating Curve= 0 ,0
Exp/Cntr=0.3,0.1

Type RM Length L Ch R = 1 ,248.3   ,243.4,248.3,253.2
XS GIS Cut Line= 3
     1880812.801      221773.058     1879919.712      221773.058
     1879602.918       221820.24
#Sta/Elev= 30
       0 1704.62    29.8  1686.7    39.7 1676.22    49.6 1668.06    59.5 1662.85
    99.2 1649.72     129    1642   238.2 1625.23   357.2 1618.71   486.2 1617.28
   496.2 1616.67   506.1 1614.52     516 1610.79   525.9 1609.86   532.9 1610.51
   547.9 1614.34   565.6 1618.75   595.4 1619.72   803.8 1617.94   863.3  1625.1
   902.8 1638.15   912.5 1644.36   980.4 1668.12   999.8 1677.57  1058.1  1696.6
  1077.5 1704.65  1145.4 1723.98  1155.1 1729.46  1184.3 1740.39  1213.4 1752.97
#Mann= 3 , 0 , 0
       0     .06       0   532.9    .045       0   547.9     .06       0
Bank Sta=532.9,547.9
XS Rating Curve= 0 ,0
Exp/Cntr=0.3,0.1

Chan Stop Cuts=-1
Use User Specified Reach Order=0
Composite Channel Slope=5